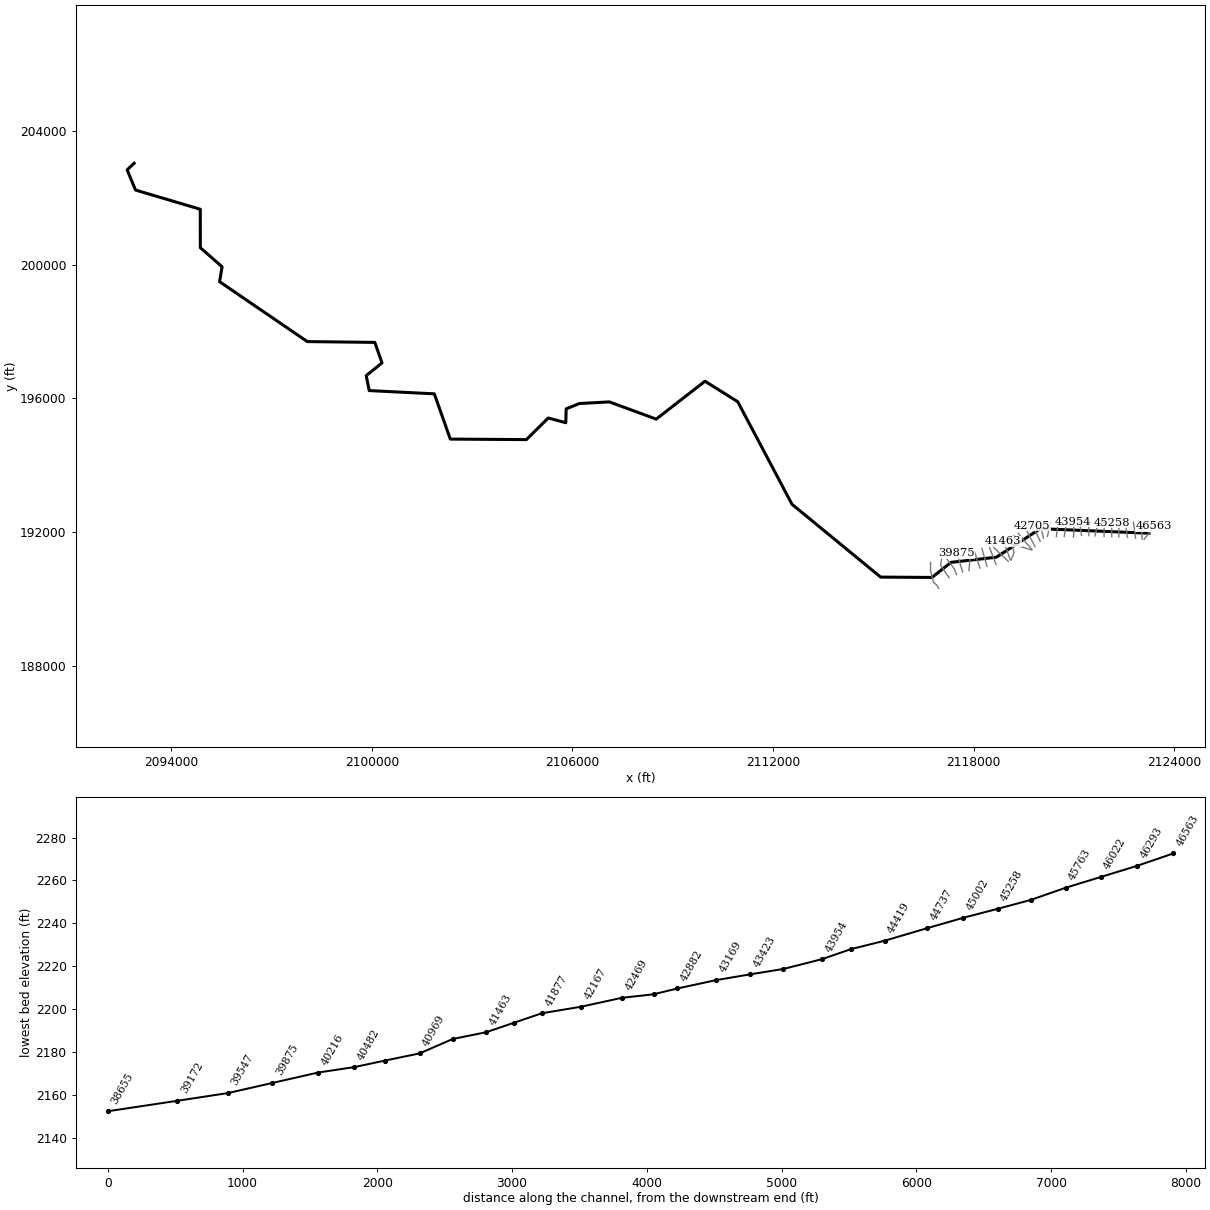
--- TRKYCK.prj (project) ---

Proj Title=TRKYCK
Current Plan=p01
Default Exp/Contr=0,0
English Units
Geom File=g01
Flow File=f01
Plan File=p01
Background Map Layer=Inundation Boundary (01pct Value_0)
Background Map Layer=Inundation Boundary (01pct Value_0)
BEGIN DESCRIPTION:
Stream Name: Turkey Creek
Flood Zone: Approximate
Monroe County, West Virginia
HEC-RAS Version: 5.0.7
Vertical Datum: NAVD88
Projection: NAD 1983 StatePlane West Virginia S FIPS 4702 (US Feet)
LiDAR: 2016, 1-meter
Land Use: 2016 NLCD
Hydrologic Method:
SIR2010-5033 regression equations
END DESCRIPTION:
DSS File=dss
DSS Export Rating Curves= 0
DSS Export Rating Curve Sorted= 0
DSS Export Volume Flow Curves= 0
DXF OffsetX= 0
DXF OffsetY= 0
DXF ScaleX= 0
DXF ScaleY= 0

--- TRKYCK.p01 (plan) ---

Plan Title=Floodplain
Program Version=5.07
Short Identifier=Floodplain
Geom File=g01
Flow File=f01
Subcritical Flow
K Sum by GR= 0
Std Step Tol= 0.01
Critical Tol= 0.01
Num of Std Step Trials= 20
Max Error Tol= 0.3
Flow Tol Ratio= 0.001
Split Flow NTrial= 30
Split Flow Tol= 0.02
Split Flow Ratio= 0.02
Log Output Level= 0
Friction Slope Method= 1
Unsteady Friction Slope Method= 2
Unsteady Bridges Friction Slope Method= 1
Parabolic Critical Depth
Global Vel Dist= 0 , 0 , 0
Global Log Level= 0
CheckData=True
Encroach Param=-1 ,0,0, 0
Computation Interval=0.1SEC
Output Interval=1MIN
Instantaneous Interval=Max Profile
Mapping Interval=1HOUR
Computation Time Step Use Courant=        0
Computation Time Step Use Time Series=    0
Computation Time Step Count To Double=0
Computation Time Step Max Doubling=0
Computation Time Step Max Halving=0
Computation Time Step Residence Courant=0
Run HTab= 0
Run UNet= 0
Run Sediment= 0
Run PostProcess= 0
Run WQNet= 0
Run RASMapper=-1
UNET Theta= 0
UNET Theta Warmup= 0
UNET ZTol= 0
UNET ZSATol= 0
UNET MxIter= 0
UNET Max Iter WO Improvement= 0
UNET MaxInSteps= 0
UNET DtIC= 0
UNET DtMin= 0
UNET MaxCRTS= 0
UNET WFStab= 0
UNET SFStab= 0
UNET WFX= 1
UNET SFX= 1
UNET 1D Methodology=Finite Difference
UNET DSS MLevel= 1
UNET Pardiso=0
UNET DZMax Abort= 0
UNET Use Existing IB Tables= 0
UNET Froude Reduction=False
UNET Froude Limit= 0
UNET Froude Power= 0
UNET D1 Cores= 0
UNET D2 Coriolis=0
UNET D2 Cores= 0
UNET D2 Theta= 1
UNET D2 Theta Warmup= 1
UNET D2 Z Tol= 0.01
UNET D2 Volume Tol= 0.01
UNET D2 Max Iterations= 20
UNET D2 Equation= 0
UNET D2 RampUpFraction=0.1
UNET D2 TimeSlices= 1
UNET D2 BCVolumeCheck=0
UNET D1D2 MaxIter= 0
UNET D1D2 ZTol=0.01
UNET D1D2 QTol=0.1
UNET D1D2 MinQTol=1
DSS File=dss
Write IC File= 0
Write IC File at Fixed DateTime=0
Write IC File at Sim End=0
Echo Input=False
Echo Parameters=False
Echo Output=False
Write Detailed= 0
HDF Write Warmup=0
HDF Write Time Slices=0
HDF Flush=0
HDF Face Node Velocities=0
HDF Compression= 1
HDF Chunk Size= 1
HDF Spatial Parts= 1
HDF Use Max Rows=0
HDF Fixed Rows= 1
Calibration Method= 0
Calibration Iterations= 20
Calibration Max Change=0.05
Calibration Tolerance=0.2
Calibration Maximum=1.5
Calibration Minimum=0.5
Calibration Optimization Method= 1
WQ AD Non Conservative
WQ ULTIMATE=-1
WQ Max Comp Step=1HOUR
WQ Output Interval=15MIN
WQ Output Selected Increments= 0
WQ Output face flow=0
WQ Output face velocity=0
WQ Output face area=0
WQ Output face dispersion=0
WQ Output cell volume=0
WQ Output cell surface area=0
WQ Output cell continuity=0
WQ Output cumulative cell continuity=0
WQ Output face conc=0
WQ Output face dconc_dx=0
WQ Output face courant=0
WQ Output face peclet=0
WQ Output face adv mass=0
WQ Output face disp mass=0
WQ Output cell mass=0
WQ Output cell source sink temp=0
WQ Output nsm pathways=0
WQ Output nsm derived pathways=0
WQ Output MaxMinRange=-1
WQ Daily Max Min Mean=-1
WQ Daily Range=0
WQ Daily Time=0
WQ Create Restart=0
WQ Fixed Restart=0
WQ System Summary=0
WQ Write To DSS=0
WQ Use Fixed Temperature=0
Sorting and Armoring Iterations= 10
XS Update Threshold= 0.02
Bed Roughness Predictor= 0
Hydraulics Update Threshold= 0.02
Energy Slope Method= 1
Volume Change Method= 1
Sediment Retention Method= 0
XS Weighting Method= 0
Number of US Weighted Cross Sections= 1
Number of DS Weighted Cross Sections= 1
Upstream XS Weight=0
Main XS Weight=1
Downstream XS Weight=0
Number of DS XS's Weighted with US Boundary= 1
Upstream Boundary Weight= 1
Weight of XSs Associated with US Boundary= 0
Number of US XS's Weighted with DS Boundary= 1
Downstream Boundary Weight= 0.5
Weight of XSs Associated with DS Boundary= 0.5
Percentile Method= 0
Sediment Output Level= 3
Mass or Volume Output= 0
Output Increment Type= 1
Profile and TS Output Increment= 1
XS Output Flag= 0
XS Output Increment= 10
Write Gradation File= 0
Read Gradation Hotstart= 0
Write HDF5 File= 1
Write Binary Output= 1
Write DSS Sediment File= 0
SV Curve= 0
Specific Gage Flag= 0

--- TRKYCK.f01 (steady flow) ---

Flow Title=Flow
Program Version=5.07
Number of Profiles= 6
Profile Names=01pct,10pct,04pct,02pct,0_2pct,01plus
River Rch & RM=TRKYCK,Main            ,46563
     402     209     280     339     565     594
River Rch & RM=TRKYCK,Main            ,46022
     529     279     371     448     740     782
River Rch & RM=TRKYCK,Main            ,45763
     553     292     388     468     773     818
River Rch & RM=TRKYCK,Main            ,43954
     649     345     457     550     905     960
River Rch & RM=TRKYCK,Main            ,43669
     712     379     502     604     990    1050
River Rch & RM=TRKYCK,Main            ,42167
    1210     660     865    1030    1670    1790
River Rch & RM=TRKYCK,Main            ,41215
    1280     700     917    1090    1770    1900
River Rch & RM=TRKYCK,Main            ,37255
    1410     769    1010    1200    1930    2080
River Rch & RM=TRKYCK,Main            ,34380
    1540     847    1110    1320    2110    2280
River Rch & RM=TRKYCK,Main            ,32219
    1610     888    1160    1380    2210    2390
River Rch & RM=TRKYCK,Main            ,29068
    1790     991    1290    1530    2450    2650
River Rch & RM=TRKYCK,Main            ,20840
    1940    1080    1400    1660    2650    2880
River Rch & RM=TRKYCK,Main            ,19481
    2110    1170    1520    1810    2880    3120
River Rch & RM=TRKYCK,Main            ,17992
    2200    1220    1590    1880    2990    3250
River Rch & RM=TRKYCK,Main            ,16447
    2430    1360    1760    2090    3310    3600
River Rch & RM=TRKYCK,Main            ,13727
    2690    1510    1950    2310    3660    3980
Boundary for River Rch & Prof#=TRKYCK,Main            , 1
Up Type= 0
Dn Type= 3
Dn Slope=0.006
Boundary for River Rch & Prof#=TRKYCK,Main            , 2
Up Type= 0
Dn Type= 3
Dn Slope=0.006
Boundary for River Rch & Prof#=TRKYCK,Main            , 3
Up Type= 0
Dn Type= 3
Dn Slope=0.006
Boundary for River Rch & Prof#=TRKYCK,Main            , 4
Up Type= 0
Dn Type= 3
Dn Slope=0.006
Boundary for River Rch & Prof#=TRKYCK,Main            , 5
Up Type= 0
Dn Type= 3
Dn Slope=0.006
Boundary for River Rch & Prof#=TRKYCK,Main            , 6
Up Type= 0
Dn Type= 3
Dn Slope=0.006
DSS Import GetInterval= 0
DSS Import GetPeak= 0
DSS Import FillOption= 0

--- TRKYCK.g01 (geometry) ---

Geom Title=Geometry
Program Version=5.07

River Reach=TRKYCK          ,Main
Reach XY= 30
     2123244.238      191963.425     2119996.185      192100.359
     2118680.994      191246.106     2117325.525      191092.287
     2116752.609      190640.203     2115219.276       190650.62
     2112568.552      192830.597     2110945.202      195901.083
     2109966.078      196514.451     2108506.356      195380.423
      2107107.05      195895.701     2106208.439       195847.09
     2105813.697      195686.852     2105802.189      195272.784
     2105276.495      195413.062     2104625.106      194766.534
     2102348.876      194782.391     2101870.555      196137.373
     2099922.893      196234.453     2099833.439      196682.506
     2100305.662      197062.367     2100091.041      197677.303
     2098072.487       197701.14     2095448.182      199494.196
     2095522.328      199941.534     2094873.023      200511.673
     2094870.614      201662.791     2092933.808      202238.138
     2092683.287      202841.263     2092892.076      203039.989

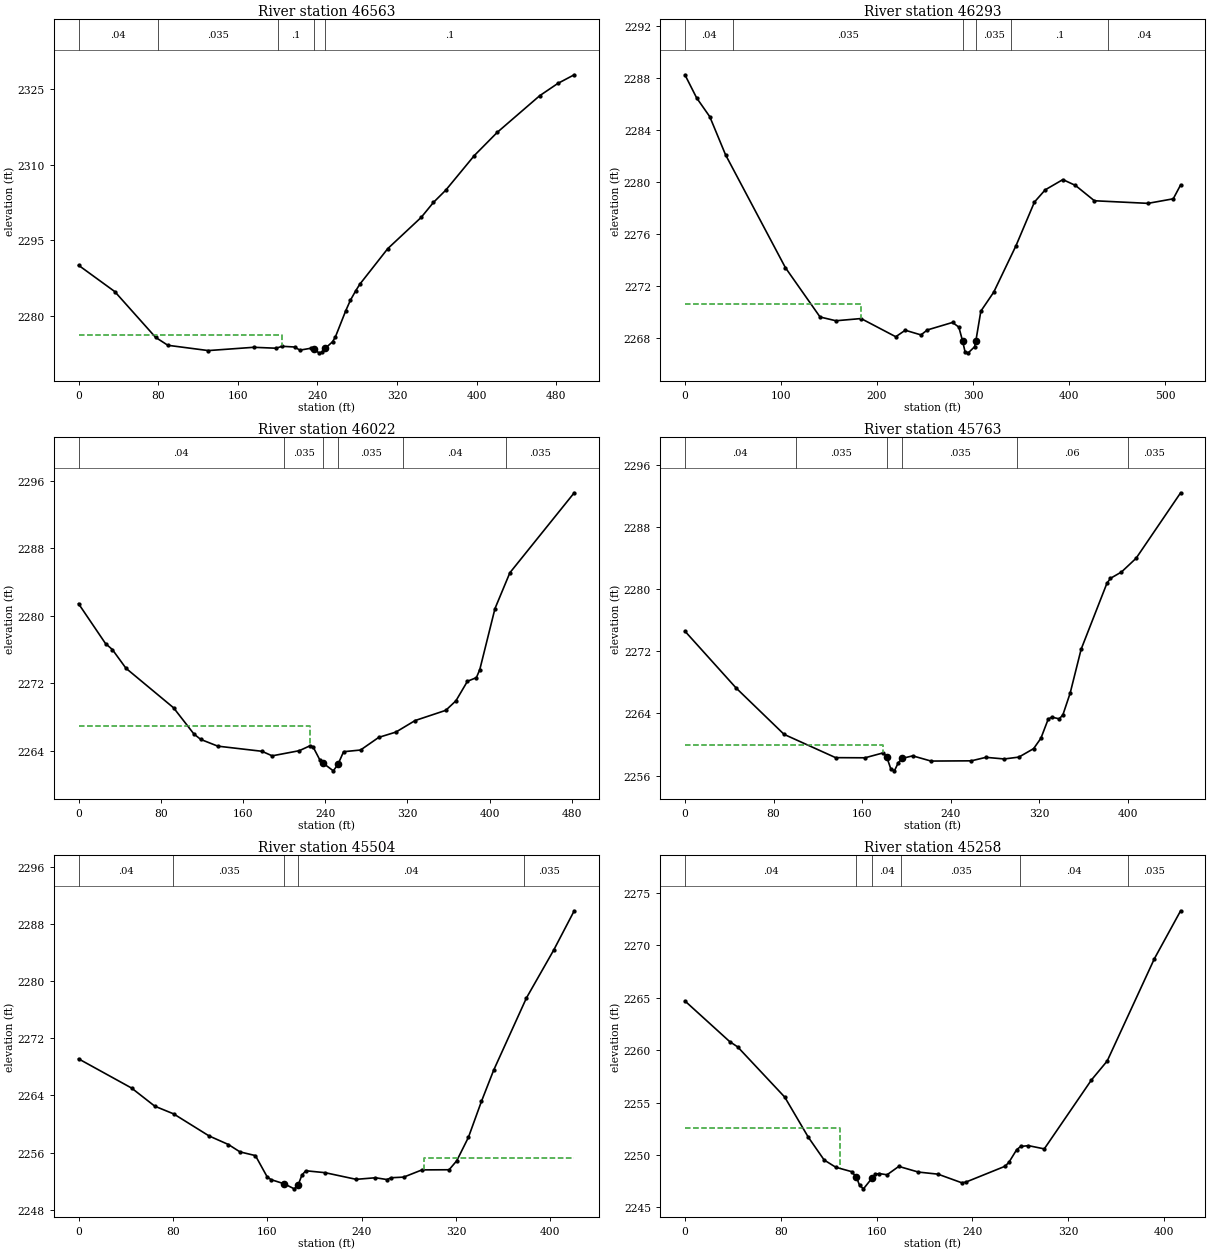
Type RM Length L Ch R = 1 ,46563   ,260.2,269.4,267.2
XS GIS Cut Line= 2
     2123097.716      191775.2412123397.40232586 192173.24030257
#Sta/Elev= 30
       0 2290.04    36.4 2284.81    77.5  2275.7    89.8 2274.13   130.4 2273.08
     176 2273.73   198.4 2273.55   204.8 2273.93   217.1 2273.79   222.5 2273.17
   233.5 2273.54   236.22273.318   241.8 2272.63   244.4 2272.73   248.22273.569
   255.3 2274.83   258.2 2275.81   268.6 2281.01   273.3  2283.1   278.7    2285
   282.8 2286.29   310.8 2293.34   344.4 2299.55   356.7 2302.52   369.1 2304.96
   397.8 2311.84   420.9 2316.46   463.5 2323.73   481.8 2326.18   498.2 2327.89
#Mann= 5 ,-1 , 0
       0     .04       0      80    .035       0     200      .1       0
   236.2    .045       0   248.2      .1       0
#XS Ineff= 2 , 0
          204.24 2276.21
Permanent Ineff=
       F       F
Bank Sta=236.2,248.2
XS Rating Curve= 0 ,0
Exp/Cntr=0.3,0.1

Type RM Length L Ch R = 1 ,46293   ,242.9,270.7,246.1
XS GIS Cut Line= 2
2123037.85144471191791.594495429     2123022.669      192307.485
#Sta/Elev= 30
       0 2288.25    12.2 2286.47    25.9 2285.02    42.3 2282.09   104.6  2273.4
   140.7  2269.6   157.2 2269.31   183.4 2269.48   219.5 2268.08   229.4 2268.58
   245.8 2268.22   252.3  2268.6   278.6 2269.18   285.2 2268.82     2892267.775
   291.7 2266.91     295 2266.84   301.6 2267.31   302.92267.756   308.1 2270.05
   321.5 2271.51   344.7 2275.09   363.9 2278.45   375.1 2279.39   393.5 2280.18
   406.6 2279.73   426.3 2278.55   482.1 2278.35   508.4  2278.7   516.1 2279.77
#Mann= 6 ,-1 , 0
       0     .04       0      50    .035       0     289    .045       0
   302.9    .035       0     340      .1       0     440     .04       0
#XS Ineff= 2 , 0
          183.09 2270.61
Permanent Ineff=
       F       F
Bank Sta=289,302.9
XS Rating Curve= 0 ,0
Exp/Cntr=0.3,0.1

Type RM Length L Ch R = 1 ,46022   ,253.8,259.9,248.7
XS GIS Cut Line= 3
     2122843.717      191817.575     2122812.732      192061.503
     2122779.301      192295.517
#Sta/Elev= 30
       0 2281.45    26.3 2276.71    32.9 2276.01    46.2 2273.78    92.5 2269.09
   112.3 2265.98   118.9 2265.34   135.5 2264.54   178.5 2263.93   188.4 2263.39
   214.8    2264   224.8 2264.56   228.1 2264.48   234.7 2262.93   238.32262.492
   247.9 2261.61   252.42262.367   257.9 2263.88   274.4 2264.08   292.1 2265.58
   308.8 2266.21   327.5 2267.58   357.3 2268.79   367.2 2269.92   378.4 2272.24
   387.1 2272.67   390.4 2273.62   405.2 2280.87   419.7 2285.12   482.3 2294.61
#Mann= 6 ,-1 , 0
       0     .04       0     200    .035       0   238.3    .045       0
   252.4    .035       0  315.89     .04       0  415.89    .035       0
#XS Ineff= 2 , 0
          224.85 2266.95
Permanent Ineff=
       F       F
Bank Sta=238.3,252.4
XS Rating Curve= 0 ,0
Exp/Cntr=0.3,0.1

Type RM Length L Ch R = 1 ,45763   ,249,258.8,244
XS GIS Cut Line= 3
     2122601.376      191840.543     2122572.465      192027.977
     2122541.633      192283.828
#Sta/Elev= 30
       0 2274.61    46.3 2267.27    89.5 2261.31     136 2258.31   162.5 2258.29
   179.1 2258.93   182.12258.418   185.8 2256.87   189.1 2256.61   192.4 2257.61
   196.2 2258.22   205.6 2258.54   222.1 2257.87   258.5  2257.9   271.7 2258.35
   288.2 2258.14   301.4 2258.38   314.7 2259.47   321.3 2260.81   327.9 2263.28
   331.2 2263.53   337.8 2263.31   341.1 2263.81   347.7 2266.63   357.6 2272.28
   380.8 2280.75     384 2281.41     394 2282.23   407.2    2284   447.4 2292.44
#Mann= 6 ,-1 , 0
       0     .04       0     100    .035       0   182.1    .045       0
   196.2    .035       0  299.65     .06       0  399.65    .035       0
#XS Ineff= 2 , 0
          178.97 2259.89
Permanent Ineff=
       F       F
Bank Sta=182.1,196.2
XS Rating Curve= 0 ,0
Exp/Cntr=0.3,0.1

Type RM Length L Ch R = 1 ,45504   ,241.6,245.8,242.5
XS GIS Cut Line= 3
2122341.43276651 191854.43850254     2122344.887       192032.13
     2122352.823      192274.542
#Sta/Elev= 30
       0 2269.11      45 2265.02    64.7 2262.48    80.6 2261.41   110.7 2258.32
   127.1 2257.12   136.9 2256.09     150 2255.57   159.9 2252.61   163.2 2252.21
   174.52251.618   182.9 2250.92   186.1  2251.4   189.4 2252.84   192.7 2253.45
   209.1 2253.18   235.4 2252.25   251.8 2252.47   261.6 2252.22   264.9 2252.47
   275.7 2252.56   291.2 2253.57   314.2 2253.59   320.7 2254.85   330.6 2258.13
   341.6 2263.14     352 2267.52   379.8 2277.63   402.9 2284.32   420.3 2289.82
#Mann= 5 ,-1 , 0
       0     .04       0      80    .035       0   174.5    .045       0
   186.1     .04       0  377.73    .035       0
#XS Ineff= 2 , 0
                          292.83         2255.26
Permanent Ineff=
       F       F
Bank Sta=174.5,186.1
XS Rating Curve= 0 ,0
Exp/Cntr=0.3,0.1

Type RM Length L Ch R = 1 ,45258   ,252.7,255.9,252.8
XS GIS Cut Line= 2
     2122132.436      191858.775     2122132.396      192272.502
#Sta/Elev= 30
       0 2264.69    37.4 2260.81      44 2260.31    83.3 2255.52     103 2251.69
   116.2 2249.52   125.9 2248.83   139.1 2248.41   143.12247.892   145.7 2247.12
     149 2246.77   156.42247.827   158.8 2248.15   162.1 2248.23   168.7 2248.11
   178.5 2248.91   194.8 2248.37   211.2 2248.17     231 2247.35   234.4 2247.41
   267.1 2248.92   270.4  2249.3   276.9 2250.51   280.2 2250.81   286.7 2250.89
   299.9 2250.58   339.3 2257.16   352.4 2258.96   391.8 2268.72   413.7 2273.29
#Mann= 6 ,-1 , 0
       0     .04       0   143.1    .045       0   156.4     .04       0
     180    .035       0     280     .04       0     370    .035       0
#XS Ineff= 2 , 0
          129.66  2252.6
Permanent Ineff=
       F       F
Bank Sta=143.1,156.4
XS Rating Curve= 0 ,0
Exp/Cntr=0.3,0.1

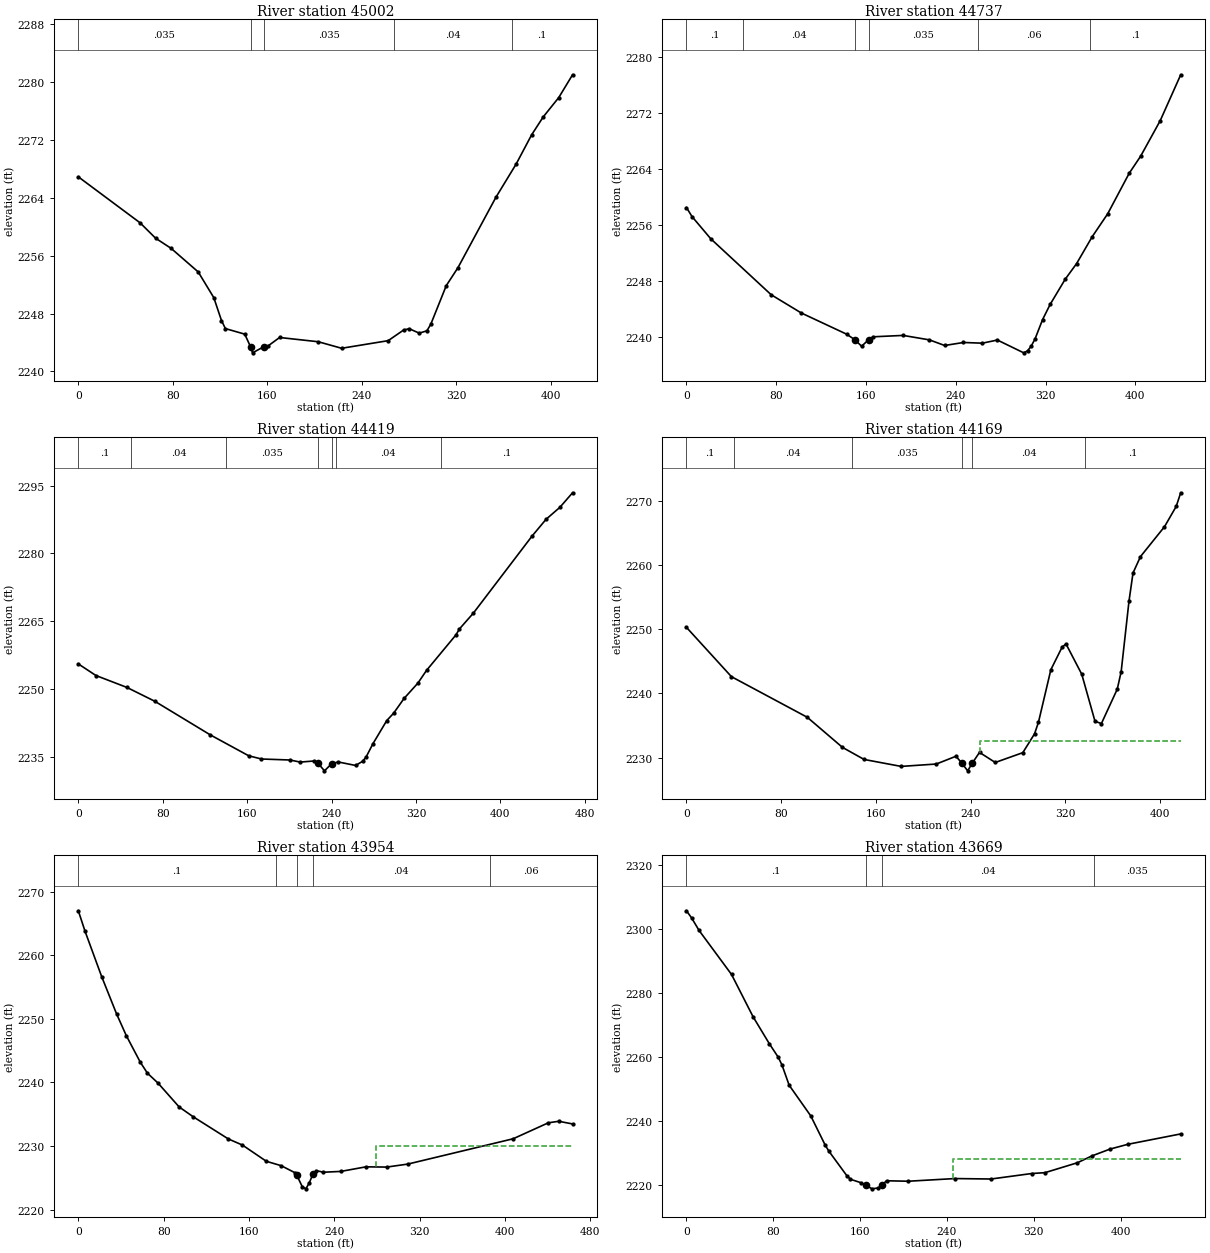
Type RM Length L Ch R = 1 ,45002   ,260.4,264.8,240.9
XS GIS Cut Line= 3
     2121902.221      191866.836     2121902.221      192023.797
     2121906.562      192285.236
#Sta/Elev= 30
       0 2266.87    52.3 2260.52    65.4  2258.4    78.6 2256.99   101.5 2253.74
   114.7 2250.19   121.2 2247.03   124.5 2245.92   140.9 2245.15   145.82243.407
   147.5 2242.57     157 2243.41   160.6 2243.52   170.4 2244.69   203.2  2244.1
   222.9  2243.2   262.3 2244.25   275.4 2245.72   280.1  2245.9   288.6 2245.29
   295.1 2245.61   298.4 2246.52   311.5 2251.85   321.4 2254.33   353.5 2264.04
   370.6 2268.62   383.8 2272.68   393.6 2275.15   406.7 2277.81   418.4 2280.96
#Mann= 5 ,-1 , 0
       0    .035       0   145.8    .045       0     157    .035       0
  266.96     .04       0  366.96      .1       0
Bank Sta=145.8,157
XS Rating Curve= 0 ,0
Exp/Cntr=0.3,0.1

Type RM Length L Ch R = 1 ,44737   ,249.9,318.6,258.8
XS GIS Cut Line= 2
      2121630.69      191884.811     2121725.791      192314.886
#Sta/Elev= 30
       0 2258.54     4.9 2257.26    21.7 2254.07    75.5 2246.08   102.4 2243.47
   142.7 2240.45   150.12239.651   156.1 2238.72   162.32239.656   166.2 2240.07
   193.1 2240.27   216.6 2239.63   230.1 2238.83   246.9 2239.26   263.7 2239.16
   277.1 2239.61   300.6 2237.78     304 2238.07   307.3 2238.75   310.7 2239.78
   317.4 2242.53   324.1 2244.69   337.6 2248.31   347.7 2250.53   361.6 2254.37
   375.4 2257.64   394.6 2263.44   404.8 2265.88   422.2 2270.94   440.5 2277.51
#Mann= 6 ,-1 , 0
       0      .1       0      50     .04       0   150.1    .045       0
   162.3    .035       0     260     .06       0     360      .1       0
Bank Sta=150.1,162.3
XS Rating Curve= 0 ,0
Exp/Cntr=0.3,0.1

Type RM Length L Ch R = 1 ,44419   ,249,250,251.3
XS GIS Cut Line= 3
2121449.10529444191892.601492381     2121445.141      192126.314
     2121445.141      192360.918
#Sta/Elev= 30
       0 2255.54    16.7 2252.97    46.2 2250.32    72.5 2247.27     125 2239.84
   161.5  2235.2   173.6 2234.49   200.5 2234.27   210.3 2233.81   223.4 2234.05
   227.32233.512   233.3 2231.87   240.22233.474   246.4 2233.83   262.8 2233.06
   269.4 2233.98   272.7 2234.91   279.2 2237.86   292.3 2242.99   298.9 2244.65
   308.7 2247.89   321.9 2251.31     330  2254.1     358 2261.99   361.2 2263.28
   374.4 2266.78   430.1 2283.86   443.3 2287.55   456.4  2290.2   468.4 2293.42
#Mann= 7 ,-1 , 0
       0      .1       0      50     .04       0     140    .035       0
   227.3    .045       0   240.2    .035       0  243.75     .04       0
  343.75      .1       0
Bank Sta=227.3,240.2
XS Rating Curve= 0 ,0
Exp/Cntr=0.3,0.1

Type RM Length L Ch R = 1 ,44169   ,215.1,214.3,212.4
XS GIS Cut Line= 3
     2121226.965      191896.522     2121198.737      192131.466
     2121169.251      192310.059
#Sta/Elev= 30
       0 2250.27      38  2242.6   102.1 2236.28   131.8  2231.6   150.1 2229.72
   181.4 2228.64   211.1 2229.01   227.7 2230.22   232.5 2229.19   237.6 2227.95
   241.4 2229.12   247.6 2230.82   260.9 2229.25   284.2 2230.78   294.1 2233.71
   297.4  2235.5   307.9 2243.69   317.4  2247.2   320.7 2247.69     334 2242.98
   345.2 2235.65   350.6 2235.31     364 2240.66   367.3 2243.39   373.9 2254.34
   377.3 2258.73   383.6 2261.28   403.9 2265.93   413.8 2269.09   417.6 2271.21
#Mann= 6 ,-1 , 0
       0      .1       0      40     .04       0     140    .035       0
   232.5    .045       0   241.4     .04       0  336.63      .1       0
#XS Ineff= 2 , 0
                          247.77         2232.64
Permanent Ineff=
       F       F
Bank Sta=232.5,241.4
XS Rating Curve= 0 ,0
Exp/Cntr=0.3,0.1

Type RM Length L Ch R = 1 ,43954   ,288.2,285.7,282.6
XS GIS Cut Line= 3
     2120985.998      191851.451     2121004.213      192016.012
     2120976.206      192312.555
#Sta/Elev= 30
       0 2266.99     6.2 2263.82    21.9 2256.64    35.9 2250.77      45 2247.36
    58.2 2243.16    64.8 2241.46    74.7 2239.91    94.5 2236.16   107.7 2234.61
   140.7 2231.12   153.9 2230.16   176.3 2227.61   190.2 2226.92   203.4 2225.79
   204.82225.425     210 2223.61   213.3 2223.28   216.6 2224.22   219.9 2225.59
   223.2 2226.14   229.8 2225.89   246.2 2226.02   269.7 2226.74   289.1  2226.7
   308.9 2227.17   407.7 2231.15   440.7 2233.66   450.5  2233.9   463.4 2233.48
#Mann= 5 ,-1 , 0
       0      .1       0  185.57     .04       0   204.8    .045       0
   219.9     .04       0  385.57     .06       0
#XS Ineff= 2 , 0
                          279.18         2229.98
Permanent Ineff=
       F       F
Bank Sta=204.8,219.9
XS Rating Curve= 0 ,0
Exp/Cntr=0.3,0.1

Type RM Length L Ch R = 1 ,43669   ,244.8,245.7,245.5
XS GIS Cut Line= 3
2120711.53073603 191865.06775127     2120738.717       192037.96
     2120780.877      192315.081
#Sta/Elev= 30
       0 2305.81     4.9 2303.48    11.6 2299.65    41.5 2285.87    61.4 2272.59
    76.3 2264.19    84.6 2259.91      88  2257.5    94.6 2251.17   114.5 2241.57
   127.8 2232.41   131.1 2230.56   147.7 2222.85   151.1 2221.71     161 2220.61
   165.42219.805     171 2218.72   176.8 2219.01   179.82219.822   184.3 2221.25
   204.2  2221.1   247.3 2221.94   280.6  2221.8   317.9 2223.51   330.3 2223.79
   360.2  2226.9   373.4 2229.02   390.1 2231.16   406.6 2232.67   455.3 2235.92
#Mann= 4 ,-1 , 0
       0      .1       0   165.4    .045       0   179.8     .04       0
  375.02    .035       0
#XS Ineff= 2 , 0
                          245.66         2227.94
Permanent Ineff=
       F       F
Bank Sta=165.4,179.8
XS Rating Curve= 0 ,0
Exp/Cntr=0.3,0.1

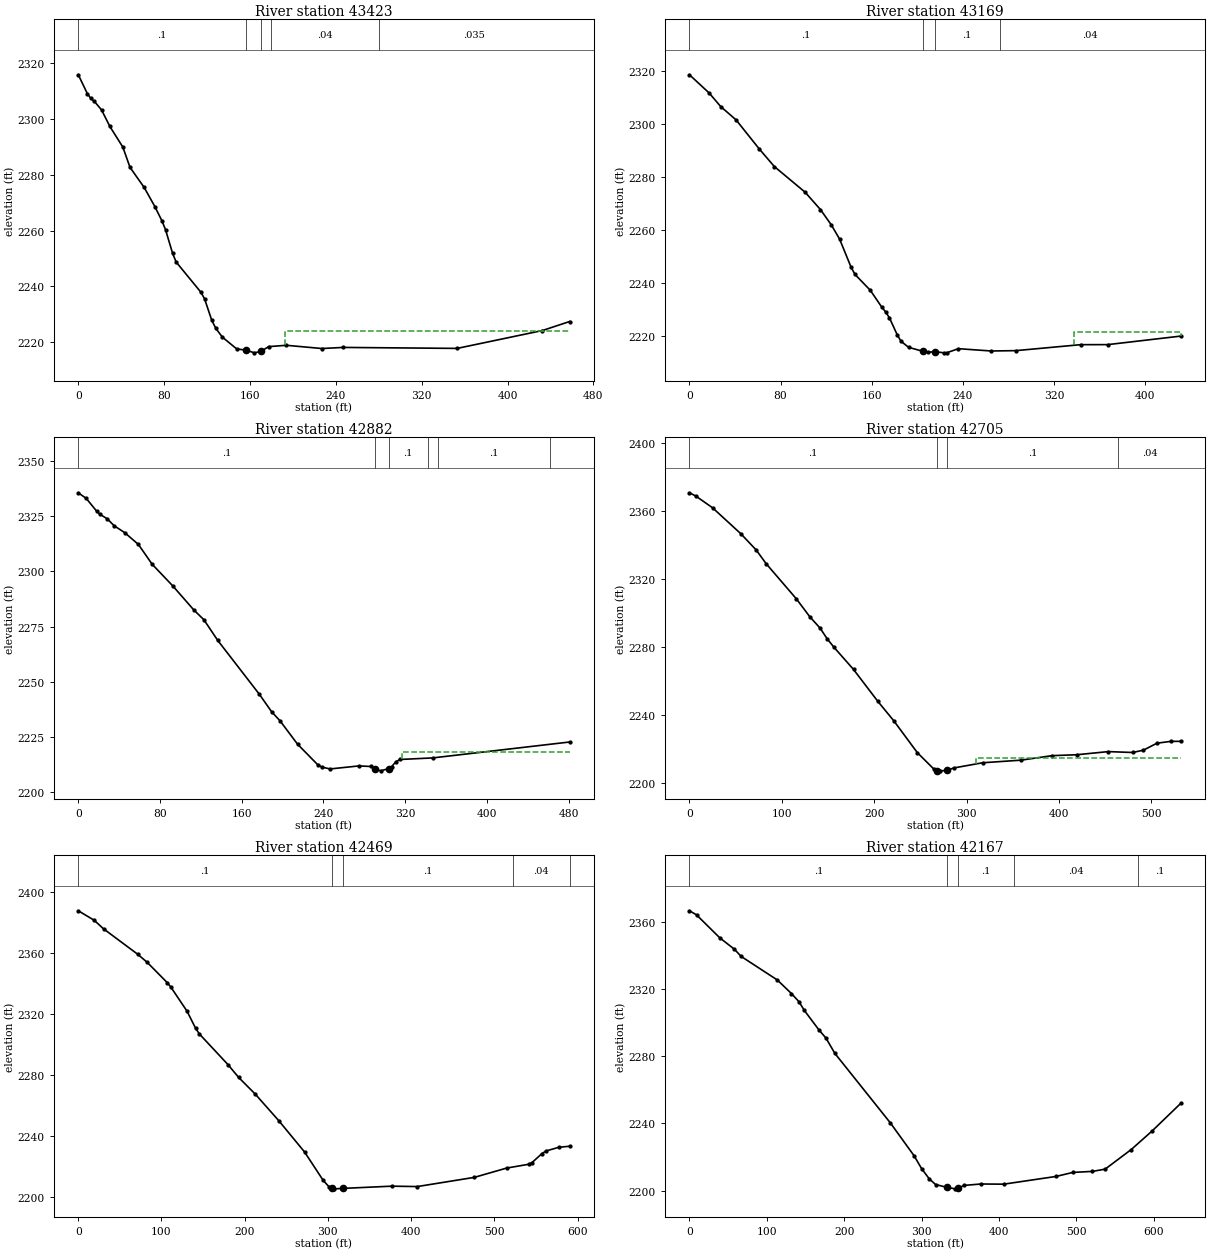
Type RM Length L Ch R = 1 ,43423   ,253.9,253.9,252.2
XS GIS Cut Line= 2
2120473.71552286191861.616487302     2120537.633      192315.075
#Sta/Elev= 30
       0 2315.86     8.4 2309.13    11.7 2307.36    14.9 2306.35    21.7 2303.25
    29.4 2297.35    41.5 2289.95    48.2 2282.67    61.4 2275.48    71.4 2268.59
      78 2263.47    81.3 2260.33    87.9 2251.83    91.2 2248.75   114.4 2237.87
   117.7 2235.51   124.4 2227.85   128.2 2224.95   134.3 2221.83   147.6 2217.63
   156.4 2217.17   164.1 2216.22   170.22216.748   177.4 2218.45     194 2218.92
   226.9 2217.77     247 2218.16     353 2217.81   432.5 2224.22   457.9 2227.45
#Mann= 5 ,-1 , 0
       0      .1       0   156.4    .045       0   170.2      .1       0
     180     .04       0     280    .035       0
#XS Ineff= 2 , 0
                          193.03         2223.95
Permanent Ineff=
       F       F
Bank Sta=156.4,170.2
XS Rating Curve= 0 ,0
Exp/Cntr=0.3,0.1

Type RM Length L Ch R = 1 ,43169   ,274,286.7,291.8
XS GIS Cut Line= 3
2120208.02322333191872.786517777     2120256.031      192079.552
     2120302.294      192293.795
#Sta/Elev= 30
       0 2318.58    17.3 2311.69    27.4 2306.59    40.9 2301.54    61.1 2290.65
    74.5 2283.91   101.5 2274.22     115 2267.65   124.5 2261.88   131.8  2256.5
   141.9 2245.86   145.3 2243.15   158.8 2237.13   168.7 2230.86   172.2 2228.99
   175.6 2226.71   182.3 2220.41   185.7 2217.89   192.4 2215.59   204.82214.118
   209.3  2213.7   215.52213.969   223.5 2213.51   226.2 2213.58   236.1 2215.08
   264.9 2214.21   286.5 2214.34   343.5  2216.6   367.1 2216.61   431.4 2219.84
#Mann= 4 ,-1 , 0
       0      .1       0   204.8    .045       0   215.5      .1       0
  272.27     .04       0
#XS Ineff= 2 , 0
                          337.91         2221.55
Permanent Ineff=
       F       F
Bank Sta=204.8,215.5
XS Rating Curve= 0 ,0
Exp/Cntr=0.3,0.1

Type RM Length L Ch R = 1 ,42882   ,176.5,177.5,173.9
XS GIS Cut Line= 4
     2120090.071      191819.419     2120039.315      192025.346
     2119888.805      192240.027     2119889.992      192246.626
#Sta/Elev= 30
       0 2335.64     7.8 2333.07    18.2 2327.17    21.3 2325.86    28.4 2323.82
    35.1 2320.69    45.3 2317.62    58.8 2312.25    72.3 2303.25    92.6 2293.38
   112.9 2282.63     123 2278.07   136.5 2268.73   177.1 2244.41   189.4 2236.31
   197.3  2232.4   214.6 2221.72   234.7 2212.24   238.7 2211.26   246.7  2210.5
   274.7 2211.86   286.4  2211.6   290.62210.552     296 2209.63   303.82210.653
   306.8 2211.57   310.8 2213.73   314.9 2214.78   346.9 2215.49     481  2222.7
#Mann= 6 ,-1 , 0
       0      .1       0   290.6    .045       0   303.8      .1       0
  342.09     .04       0  352.09      .1       0  462.09     .04       0
#XS Ineff= 2 , 0
                          317.05         2217.99
Permanent Ineff=
       F       F
Bank Sta=290.6,303.8
XS Rating Curve= 0 ,0
Exp/Cntr=0.3,0.1

Type RM Length L Ch R = 1 ,42705   ,236,235.7,234.6
XS GIS Cut Line= 3
     2119992.508      191722.747     2119874.537        191970.3
      2119746.95      192194.172
#Sta/Elev= 30
       0 2370.73     6.8 2368.83      25 2361.89    55.6  2346.6    72.2 2337.04
    83.1  2328.9   115.8 2308.18   130.3 2297.65   141.3 2291.06   149.1 2284.66
   156.5 2279.65   177.6 2266.62   203.8  2247.9   221.2 2236.36   246.6 2217.65
   264.8  2207.8   267.72207.087   271.7 2206.89   278.92207.137     286 2208.57
   317.3 2211.65   358.9 2213.18   392.5 2215.84   419.3 2216.38   453.3 2218.22
   479.7  2217.7   491.4 2219.08   506.1 2223.19   521.2 2224.26   531.9 2224.27
#Mann= 4 ,-1 , 0
       0      .1       0   267.7    .045       0   278.9      .1       0
  464.23     .04       0
#XS Ineff= 2 , 0
                          310.42         2214.62
Permanent Ineff=
       F       F
Bank Sta=267.7,278.9
XS Rating Curve= 0 ,0
Exp/Cntr=0.3,0.1

Type RM Length L Ch R = 1 ,42469   ,292.7,302.2,296.8
XS GIS Cut Line= 3
     2119835.967      191567.635     2119698.073      191825.616
     2119570.531      192095.017
#Sta/Elev= 30
       0 2387.58    19.1 2381.36    30.3 2375.76    71.2 2359.15    82.8 2353.78
   107.1 2340.35   111.5 2337.33   130.7 2321.73     141 2310.52   145.6 2306.76
   179.8 2286.77   192.8 2278.26   212.6 2267.42   240.8 2250.04   271.9 2229.45
   294.4 2210.75   301.1 2206.75   304.92205.526   307.7 2205.25   318.72205.557
   376.8    2207   407.4 2206.74   475.9 2212.76   514.8 2218.86   541.2 2221.35
   545.4  2222.5   557.3 2228.39   562.3  2230.1   577.5 2232.49   590.6 2233.19
#Mann= 5 ,-1 , 0
       0      .1       0   304.9    .045       0   318.7      .1       0
  522.52     .04       0  590.59      .1       0
Bank Sta=304.9,318.7
XS Rating Curve= 0 ,0
Exp/Cntr=0.3,0.1

Type RM Length L Ch R = 1 ,42167   ,290.3,289.9,281.7
XS GIS Cut Line= 3
     2119746.165      191478.653     2119520.986      191732.982
     2119334.485      191962.349
#Sta/Elev= 30
       0 2366.53     9.1 2364.11    39.3 2350.39    58.1 2343.65    66.9 2339.35
   113.7 2325.32   131.9 2317.26   141.6 2312.42   148.5 2307.25   167.7 2295.47
   176.4 2290.85     188 2281.67   259.7 2240.35   290.4 2220.78   300.1 2213.15
     310 2207.04   318.2 2203.66   333.22201.942   343.8 2201.09   347.62201.558
   355.3 2203.14   376.7 2203.97   406.3 2203.87   473.9 2208.46   495.7 2210.86
     521 2211.47   537.4 2212.81   571.2 2224.49     598 2235.45   635.3    2252
#Mann= 5 ,-1 , 0
       0      .1       0   333.2    .045       0   347.6      .1       0
  419.69     .04       0  579.69      .1       0
Bank Sta=333.2,347.6
XS Rating Curve= 0 ,0
Exp/Cntr=0.3,0.1

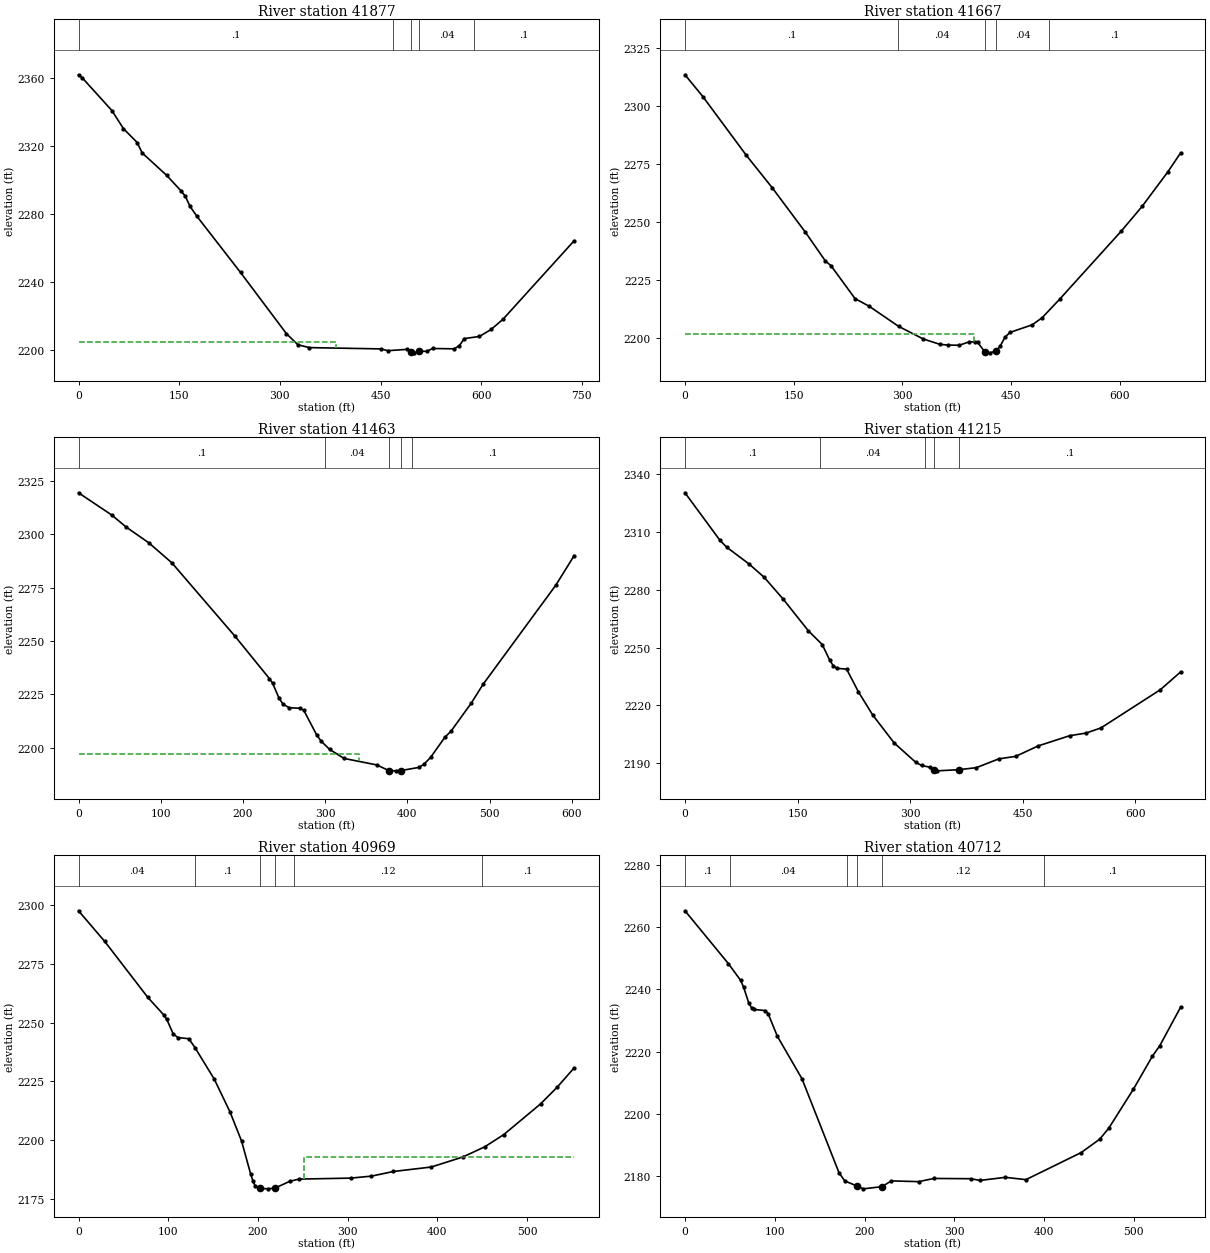
Type RM Length L Ch R = 1 ,41877   ,211.8,210.1,206.5
XS GIS Cut Line= 3
     2119732.786      191465.3972119349.85824365191578.302512698
2119211.44601016      191888.031
#Sta/Elev= 30
       0 2361.83     5.4 2360.13    49.9 2340.68    66.9 2330.13    87.4 2321.94
    94.8 2315.83   131.2 2302.65   152.9 2293.39   159.3  2290.2   166.1 2284.34
   176.6 2278.39   241.4  2245.4   309.8 2209.36   326.9 2202.81     344 2201.15
   450.7 2200.39   460.7 2199.34   488.7 2200.09   495.62198.651   499.5 2198.07
   507.72199.049   518.6 2198.94   527.7 2200.63     560 2200.43   567.5 2202.38
   574.9 2206.47   597.3 2207.72   614.7 2211.84   632.4 2217.82   738.5  2264.1
#Mann= 5 ,-1 , 0
       0      .1       0  469.23     .04       0   495.6    .045       0
   507.7     .04       0  589.23      .1       0
#XS Ineff= 2 , 0
          383.26 2204.62
Permanent Ineff=
       F       F
Bank Sta=495.6,507.7
XS Rating Curve= 0 ,0
Exp/Cntr=0.3,0.1

Type RM Length L Ch R = 1 ,41667   ,202.2,203.8,204.2
XS GIS Cut Line= 4
      2119123.42      191171.289 2119211.4987919191388.954121749
     2119145.588      191616.9852119076.16652794191817.514761428
#Sta/Elev= 30
       0 2313.49    24.6 2304.12    84.8 2278.71   120.2 2264.88   166.2 2245.63
   193.9 2233.18   201.6 2231.17   234.8 2216.98   254.6 2213.62   294.9 2205.01
   329.1 2199.54   352.1 2197.24   362.7 2196.94   378.6 2196.84   391.9 2198.27
   400.8 2198.34   404.2 2198.07   413.72194.134     421 2193.58   429.72194.409
     435 2196.36   441.8 2200.27   448.6 2202.37   479.5 2205.66   493.4 2208.79
   517.7 2216.83   602.4 2246.06   631.3 2256.76     667 2271.74   684.4 2279.82
#Mann= 5 ,-1 , 0
       0      .1       0  294.81     .04       0   413.7    .045       0
   429.7     .04       0  502.18      .1       0
#XS Ineff= 2 , 0
          398.96 2201.65
Permanent Ineff=
       F       F
Bank Sta=413.7,429.7
XS Rating Curve= 0 ,0
Exp/Cntr=0.3,0.1

Type RM Length L Ch R = 1 ,41463   ,241.8,248.3,253.9
XS GIS Cut Line= 3
     2119099.626      191162.695     2118968.707      191525.063
     2118886.795      191726.694
#Sta/Elev= 30
       0 2319.35    40.4 2308.94    57.8 2303.36    85.7 2295.87   113.6 2286.54
   190.4 2252.18   232.2 2232.38   236.1  2230.2   243.8 2223.32   248.9 2220.32
   256.6 2218.72   269.4  2218.5   274.1 2217.47   289.9 2205.85   295.2 2203.07
   305.3 2199.28   322.9 2195.01   362.8 2191.97   377.32189.351   385.7  2189.2
   391.8 2189.31     414  2190.8     420 2192.24   428.2 2195.46   445.9 2205.05
     453  2207.7   477.8 2220.93     492 2229.65   580.5 2276.05   602.9 2289.94
#Mann= 5 ,-1 , 0
       0      .1       0     300     .04       0   377.3    .045       0
   391.8     .04       0  405.29      .1       0
#XS Ineff= 2 , 0
          341.73 2197.13
Permanent Ineff=
       F       F
Bank Sta=377.3,391.8
XS Rating Curve= 0 ,0
Exp/Cntr=0.3,0.1

Type RM Length L Ch R = 1 ,41215   ,252.3,246.1,242.3
XS GIS Cut Line= 3
     2119036.485      191123.779     2118773.052       191373.55
     2118559.513      191580.201
#Sta/Elev= 30
       0 2330.47    46.7 2305.72    55.8 2302.14    85.3  2293.5   105.5 2286.57
   130.8 2275.24   164.2 2258.85   182.8 2251.66   192.8 2243.53   197.6 2240.58
   202.3 2239.28   215.3  2238.9   230.9 2227.16     250 2215.08   278.6 2200.54
   307.2 2190.54   315.1 2188.84   326.3 2187.92   331.5 2186.36   335.8 2186.05
   364.4 2186.63     388 2187.69     418 2192.27   440.4 2193.56   470.5    2199
   512.3 2204.29   534.3 2205.67   554.1 2208.34     633 2228.14   660.2 2237.42
#Mann= 5 ,-1 , 0
       0      .1       0     180     .04       0     320      .1       0
   331.5    .045       0   364.4      .1       0
Bank Sta=331.5,364.4
XS Rating Curve= 0 ,0
Exp/Cntr=0.3,0.1

Type RM Length L Ch R = 1 ,40969   ,257.4,256.5,256.1
XS GIS Cut Line= 2
     2118669.334      191029.918     2118473.191      191546.422
#Sta/Elev= 30
       0 2297.59    29.2 2284.56    77.3 2260.72    94.9 2253.34    98.4 2251.39
   105.4 2245.36   110.6 2243.68     123 2243.16     130 2239.28   151.3 2225.99
   169.1 2211.83   181.8 2199.59   191.9 2185.58   194.5 2182.63     197 2180.49
   202.72179.539   210.7 2179.31     2192179.622   235.3 2182.48   245.8 2183.46
   303.4 2183.87   326.5 2184.72   351.1 2186.69   393.2 2188.59   428.5 2192.87
   452.9  2197.2   473.9 2202.35     515 2215.43   533.6 2222.56   552.5 2230.77
#Mann= 6 ,-1 , 0
       0     .04       0     130      .1       0   202.7    .045       0
     219      .1       0     240     .12       0     450      .1       0
#XS Ineff= 2 , 0
                          250.81         2193.03
Permanent Ineff=
       F       F
Bank Sta=202.7,219
XS Rating Curve= 0 ,0
Exp/Cntr=0.3,0.1

Type RM Length L Ch R = 1 ,40712   ,228.3,230.1,231.5
XS GIS Cut Line= 2
2118401.45312857190977.1765947952118246.50322374191507.105269324
#Sta/Elev= 30
       0 2265.22    48.3 2248.28    61.9 2242.92    65.3  2240.7    71.1 2235.58
    74.1 2234.11    76.4 2233.56    89.3  2233.2    92.7 2232.14   102.9 2224.95
   130.3 2211.32   171.6 2181.13   178.1 2178.49   191.8 2176.87   198.7 2175.98
   219.5 2176.68   229.8 2178.53   260.2 2178.29   277.3 2179.31   318.3 2179.23
   328.5 2178.68   356.8 2179.67   379.8 2178.93   441.2  2187.6   461.9  2191.9
   472.1 2195.46   499.5 2207.97   520.7 2218.58   528.7 2221.82   552.1 2234.29
#Mann= 6 ,-1 , 0
       0      .1       0      50     .04       0     180     .12       0
   191.8    .045       0   219.5     .12       0     400      .1       0
Bank Sta=191.8,219.5
XS Rating Curve= 0 ,0
Exp/Cntr(USF)=0,0
Exp/Cntr=0.3,0.1

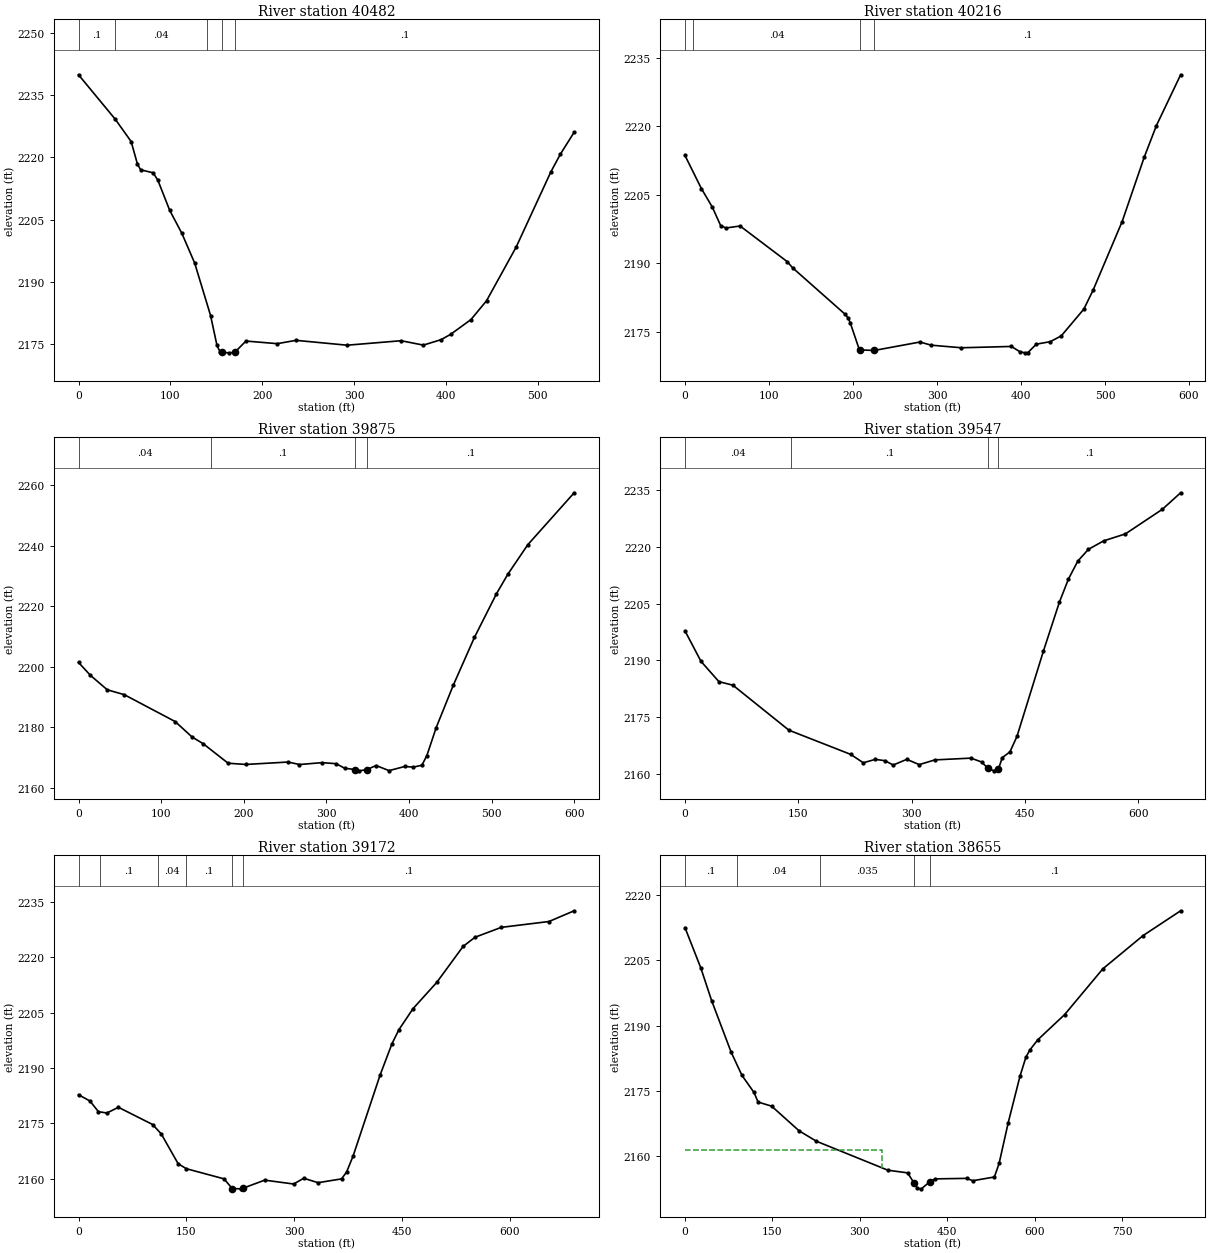
Type RM Length L Ch R = 1 ,40482   ,271,266.3,261
XS GIS Cut Line= 2
     2118191.349      190919.918     2118020.659      191431.865
#Sta/Elev= 30
       0 2239.89      40 2229.18    57.3 2223.81    64.2 2218.34    67.7 2216.99
    81.2 2216.28    86.4 2214.49    99.3 2207.23   112.6 2201.66   126.5 2194.52
   143.8 2181.89   150.7 2174.76   154.1  2173.1   156.52173.004   164.2  2172.9
   170.12173.017   182.3 2175.74   216.4 2175.11   236.8 2175.91   292.5 2174.74
   351.3 2175.82   375.5 2174.76     395 2176.09   405.4 2177.39   427.3 2180.91
   444.3 2185.45   476.5 2198.36   514.3 2216.49   524.7 2220.77   539.7 2226.05
#Mann= 5 ,-1 , 0
       0      .1       0      40     .04       0     140      .1       0
   156.5    .045       0   170.1      .1       0
Bank Sta=156.5,170.1
XS Rating Curve= 0 ,0
Exp/Cntr=0.3,0.1

Type RM Length L Ch R = 1 ,40216   ,335.7,340.9,345.3
XS GIS Cut Line= 3
     2117858.838      190843.396      2117880.91      191067.496
     2117914.706      191430.696
#Sta/Elev= 30
       0 2213.62    19.5 2206.38    32.6 2202.28    42.5 2198.25    48.6 2197.73
    65.6 2198.17   121.6 2190.38   128.2    2189   190.9 2178.79   194.2 2178.03
   196.6 2177.03   207.3 2171.22   208.92171.026   225.2 2170.91   279.8 2172.76
     293 2172.07   329.1  2171.5   388.6 2171.79   398.5 2170.65   404.5 2170.39
   408.3 2170.46   418.2 2172.29   434.7 2172.83   447.9  2174.1   474.8 2179.97
   485.9 2184.16   520.4 2199.15   546.7 2213.26   561.2 2220.18     590 2231.29
#Mann= 4 ,-1 , 0
       0      .1       0      10     .04       0   208.9    .045       0
   225.2      .1       0
Bank Sta=208.9,225.2
XS Rating Curve= 0 ,0
Exp/Cntr=0.3,0.1

Type RM Length L Ch R = 1 ,39875   ,323.2,328.2,329.2
XS GIS Cut Line= 3
     2117671.418      190799.761     2117578.973      191115.958
      2117491.53      191371.691
#Sta/Elev= 30
       0 2201.35    14.4 2197.08    34.8  2192.3    55.3  2190.7   116.9 2181.81
   137.4  2176.7   151.1 2174.43     181 2168.03   202.3 2167.62   253.6 2168.42
   267.3  2167.6   294.8 2168.22   311.7 2167.87     322 2166.37   334.52165.943
   339.5 2165.51     3492165.923     360 2167.27   375.7 2165.58   394.7 2166.95
   405.1 2166.74   415.5 2167.37   421.5 2170.57   432.8 2179.83   453.6 2193.92
     479 2209.61   505.6    2224   519.5 2230.53   543.6 2240.26   599.7 2257.43
#Mann= 4 ,-1 , 0
       0     .04       0     160      .1       0   334.5    .045       0
     349      .1       0
Bank Sta=334.5,349
XS Rating Curve= 0 ,0
Exp/Cntr=0.3,0.1

Type RM Length L Ch R = 1 ,39547   ,373.3,375,369.8
XS GIS Cut Line= 3
     2117489.304        190724.9     2117419.972      190900.604
     2117137.496      191272.979
#Sta/Elev= 30
       0 2197.79    21.2 2189.74    44.9 2184.38    63.5 2183.43   137.6 2171.55
   219.4 2165.16   236.1 2162.94     252 2163.84   264.9 2163.49   275.7 2162.34
   293.7 2163.85   310.2 2162.45   330.8  2163.7   378.7 2164.17   392.8 2163.14
   401.32161.453   409.2 2160.81   415.12161.343   420.2 2164.31   430.3 2165.82
   439.6 2169.91   474.7  2192.5   495.8 2205.39   507.8  2211.5   520.2 2216.24
   534.2 2219.33   554.4 2221.57   583.1  2223.4     632 2229.89   656.3 2234.27
#Mann= 4 ,-1 , 0
       0     .04       0     140      .1       0   401.3    .045       0
   415.1      .1       0
Bank Sta=401.3,415.1
XS Rating Curve= 0 ,0
Exp/Cntr=0.3,0.1

Type RM Length L Ch R = 1 ,39172   ,519.8,516.9,458.9
XS GIS Cut Line= 3
     2117266.096      190633.147     2117012.778      191005.611
     2117049.237      191241.767
#Sta/Elev= 30
       0 2182.74    15.8 2181.05    27.7 2178.15    39.4 2177.78    55.5 2179.33
   103.1 2174.66     115 2172.13   138.6 2164.02     150 2162.67   202.4 2159.92
   213.82157.288   226.1 2157.21   228.62157.366     259 2159.57   299.2 2158.52
   313.3 2160.08   333.2 2158.88   365.9 2159.91   372.9 2161.79   381.9  2166.1
   419.6 2188.15   435.9 2196.53   445.6 2200.37   465.2 2206.07   498.4 2213.24
   534.9 2222.97   551.5 2225.46     588 2228.14   654.4 2229.73   689.4 2232.64
#Mann= 6 ,-1 , 0
       0     .04       0      30      .1       0     110     .04       0
     150      .1       0   213.8    .045       0   228.6      .1       0
Bank Sta=213.8,228.6
XS Rating Curve= 0 ,0
Exp/Cntr=0.3,0.1

Type RM Length L Ch R = 1 ,38655   ,327.9,325.8,258.5
XS GIS Cut Line= 5
2116954.23978681190310.6651195732116901.99935146190408.358060473
2116798.74251326190493.7029981732116711.03494185190841.804926748
     2116714.326      191087.968
#Sta/Elev= 30
       0 2212.58  27.0442203.321  45.6472195.761  79.131 2183.86  97.733 2178.49
 118.3172174.577 125.3082172.354 148.611  2171.4 195.7152165.709 225.5122163.304
 347.8672156.633 381.7012156.017 392.6962153.708 398.6182152.453 405.3842152.333
 419.7212153.964 429.0682154.631 483.2022154.747 493.3522154.204 530.5692155.061
 538.6292158.192 554.2532167.582 574.5532178.368 584.7032182.736  591.472184.378
 604.965 2186.71 650.9012192.509 716.5232203.077 785.4272210.739 849.9122216.465
#Mann= 5 ,-1 , 0
       0      .1       0      90     .04       0  230.78    .035       0
 392.696    .045       0 419.721      .1       0
#XS Ineff= 2 , 0
          337.52 2161.36
Permanent Ineff=
       F       F
Bank Sta=392.696,419.721
XS Rating Curve= 0 ,0
Exp/Cntr=0.3,0.1