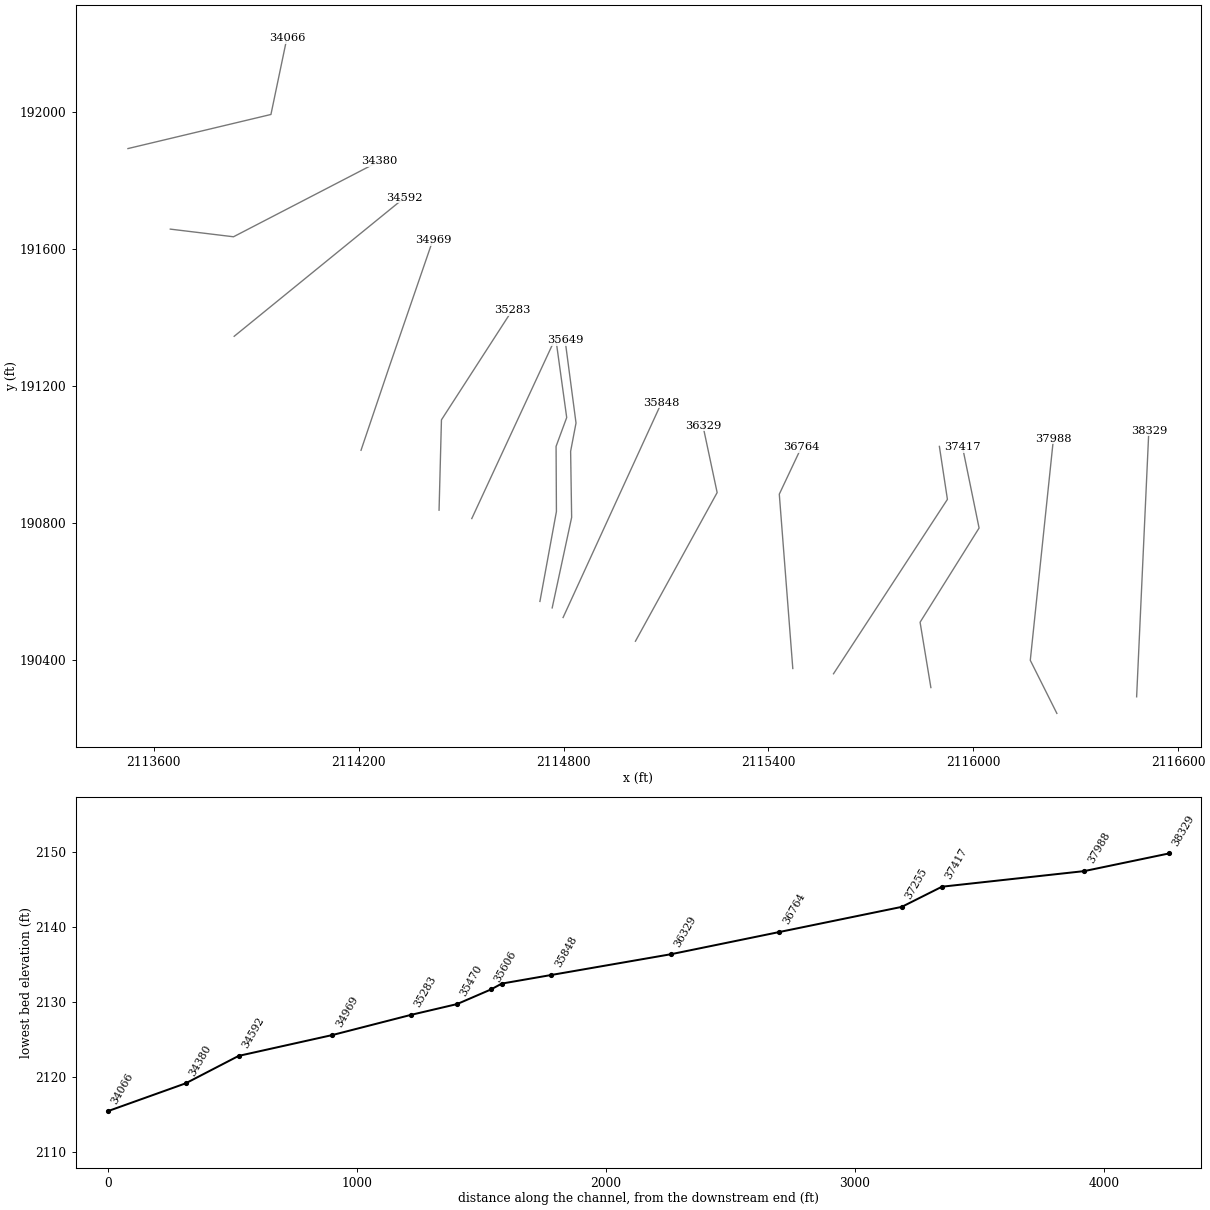
HEC-RAS study TRKYCK.prj: TRKYCK

--- TRKYCK.g01 (geometry) --- (continued)

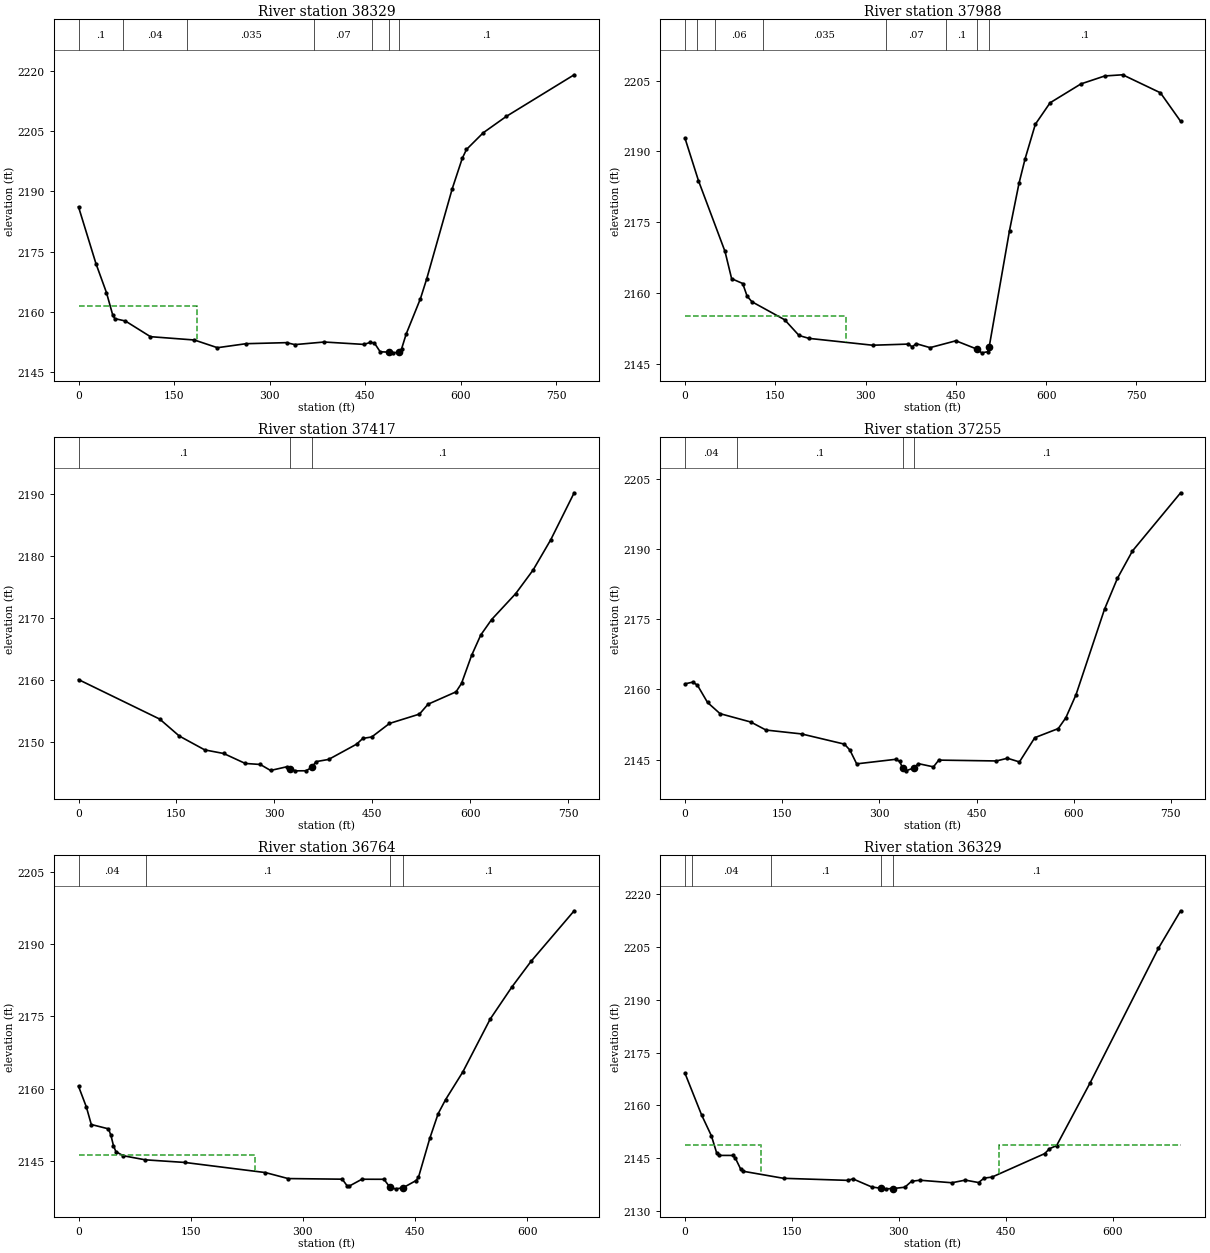
Type RM Length L Ch R = 1 ,38329   ,340.3,341.1,337
XS GIS Cut Line= 2
     2116478.317      190293.934     2116514.063      191070.881
#Sta/Elev= 30
       0 2186.16    27.4 2171.99    43.9 2164.76    53.8 2159.13      57 2158.29
    73.5  2157.7   112.9 2153.79   181.8 2152.96     218 2151.04     263 2152.04
   326.4  2152.3   339.5 2151.81   385.5 2152.46   447.9 2151.86   457.7 2152.36
   464.3 2152.21   473.4 2150.02   486.6 2149.94   493.9 2149.76   503.32149.945
     507 2150.76   514.2 2154.46   536.6 2163.28   546.4  2168.2   586.4 2190.64
   602.2 2198.25   608.8 2200.46   635.1 2204.62   671.2 2208.69   777.8 2219.08
#Mann= 7 ,-1 , 0
       0      .1       0      70     .04       0     170    .035       0
     370     .07       0     460      .1       0   486.6    .045       0
   503.3      .1       0
#XS Ineff= 2 , 0
          185.46 2161.54
Permanent Ineff=
       F       F
Bank Sta=486.6,503.3
XS Rating Curve= 0 ,0
Exp/Cntr=0.3,0.1

Type RM Length L Ch R = 1 ,37988   ,573.5,571.2,465.4
XS GIS Cut Line= 3
     2116244.706      190245.565     2116166.887190400.491582013
     2116234.686      191047.043
#Sta/Elev= 30
       0 2192.82    22.4 2183.83    66.5 2168.85    77.5 2163.09    95.9 2162.07
   103.2  2159.4   111.2 2158.21   165.6  2154.4   189.5 2151.07     206 2150.46
   311.8 2149.01   370.9 2149.25   377.5 2148.67   384.1 2149.34   407.2  2148.5
   450.1 2149.95     485 2148.19     493  2147.4   502.9 2147.63   505.4 2148.64
   539.2 2173.28     555 2183.29   565.1 2188.46   582.1 2195.76   606.6  2200.3
   657.9  2204.3   697.5 2205.98   727.2 2206.23   789.9 2202.42   823.5 2196.38
#Mann= 8 ,-1 , 0
       0      .1       0      20     .04       0      50     .06       0
     130    .035       0  333.37     .07       0  433.37      .1       0
     485    .045       0   505.4      .1       0
#XS Ineff= 2 , 0
          268.19 2155.16
Permanent Ineff=
       F       F
Bank Sta=485,505.4
XS Rating Curve= 0 ,0
Exp/Cntr=0.3,0.1

Type RM Length L Ch R = 1 ,37417   ,156.7,161.5,166.5
XS GIS Cut Line= 4
2115875.75281665190320.9058403612115844.14358047190511.614898678
2116016.94073828190786.615253489 2115968.4732428191022.630883672
#Sta/Elev= 30
       0 2160.05   124.4 2153.67   154.3 2150.94   193.3  2148.7   222.3 2148.12
   255.4 2146.51   278.3 2146.35   294.1 2145.38   318.7 2145.97     3242145.644
   332.2 2145.32   348.4 2145.33   356.8 2145.86   363.9 2146.81     383 2147.16
   425.9 2149.63   435.3 2150.55   449.1 2150.79   476.2 2152.97   522.1 2154.48
   535.2 2156.07   578.1 2158.07   586.5 2159.43   601.9 2163.94     616 2167.25
   632.6 2169.74   669.5 2173.93   696.1 2177.73   723.1 2182.61     759  2190.2
#Mann= 3 ,-1 , 0
       0      .1       0     324    .045       0   356.8      .1       0
Bank Sta=324,356.8
XS Rating Curve= 0 ,0
Exp/Cntr(USF)=0,0
Exp/Cntr=0.3,0.1

Type RM Length L Ch R = 1 ,37255   ,477.7,491.2,495.1
XS GIS Cut Line= 3
     2115590.597      190361.186     2115924.204      190870.268
     2115900.668      191024.842
#Sta/Elev= 30
       0  2161.2    11.8 2161.56    19.1 2160.94    34.8 2157.23    54.1 2154.84
   101.6 2153.05     125 2151.34   179.9 2150.51   246.1 2148.33   254.5 2147.07
     265 2144.12   325.1 2145.09   331.4 2144.63     3362143.196   340.8 2142.63
     353 2143.23   360.4 2144.16   383.5 2143.48   391.7 2144.92   480.7 2144.74
   497.7 2145.32   516.2 2144.53   539.9 2149.71   576.1 2151.65   587.9 2153.98
   603.6 2158.91   647.5 2177.12   667.4 2183.72   690.6 2189.56     765 2201.99
#Mann= 4 ,-1 , 0
       0     .04       0      80      .1       0     336    .045       0
     353      .1       0
Bank Sta=336,353
XS Rating Curve= 0 ,0
Exp/Cntr=0.3,0.1

Type RM Length L Ch R = 1 ,36764   ,436.6,435.1,420.5
XS GIS Cut Line= 3
     2115471.382       190376.57     2115431.838      190885.436
     2115497.055      191023.294
#Sta/Elev= 30
       0 2160.54    10.5 2156.24    17.1 2152.61    40.1 2151.71    43.4 2150.34
    46.7 2148.25      50 2146.98    59.8 2146.14    89.4 2145.29   142.1 2144.75
     250 2142.65   280.3 2141.41   352.7 2141.28   359.3  2139.9   362.1 2139.85
     379 2141.27   408.5 2141.26   416.62139.582     424 2139.28   433.72139.474
   451.4 2140.99   454.7 2141.68   469.8 2149.74     481 2154.86   490.9 2157.76
     514 2163.51   550.6 2174.46   579.6 2181.11   605.1  2186.4   662.9  2196.9
#Mann= 4 ,-1 , 0
       0     .04       0      90      .1       0   416.6    .045       0
   433.7      .1       0
#XS Ineff= 2 , 0
          235.85 2146.21
Permanent Ineff=
       F       F
Bank Sta=416.6,433.7
XS Rating Curve= 0 ,0
Exp/Cntr=0.3,0.1

Type RM Length L Ch R = 1 ,36329   ,474.9,480.7,474
XS GIS Cut Line= 3
      2115010.57      190456.252     2115249.826      190890.103
     2115208.214      191085.309
#Sta/Elev= 30
       0 2169.16    23.3 2157.31    37.1 2151.36    44.6 2146.41    48.3 2145.82
      67 2145.81    70.8 2144.98    78.3 2141.84      82  2141.3   138.2 2139.31
   228.1 2138.73   235.6 2139.14   261.9 2136.85   275.52136.451   281.7 2136.32
   291.92136.406   308.3 2136.78   317.7 2138.46   329.3 2138.77   374.3 2138.05
     393  2138.8   411.7 2138.11   419.4 2139.36   430.5 2139.66   504.4 2146.33
   511.1 2147.72   521.1 2148.61   568.1 2166.44   663.8 2204.64     695 2215.32
#Mann= 5 ,-1 , 0
       0      .1       0      10     .04       0     120      .1       0
   275.5    .045       0   291.9      .1       0
#XS Ineff= 2 , 0
          106.16 2148.67  440.69         2148.67
Permanent Ineff=
       F       F
Bank Sta=275.5,291.9
XS Rating Curve= 0 ,0
Exp/Cntr=0.3,0.1

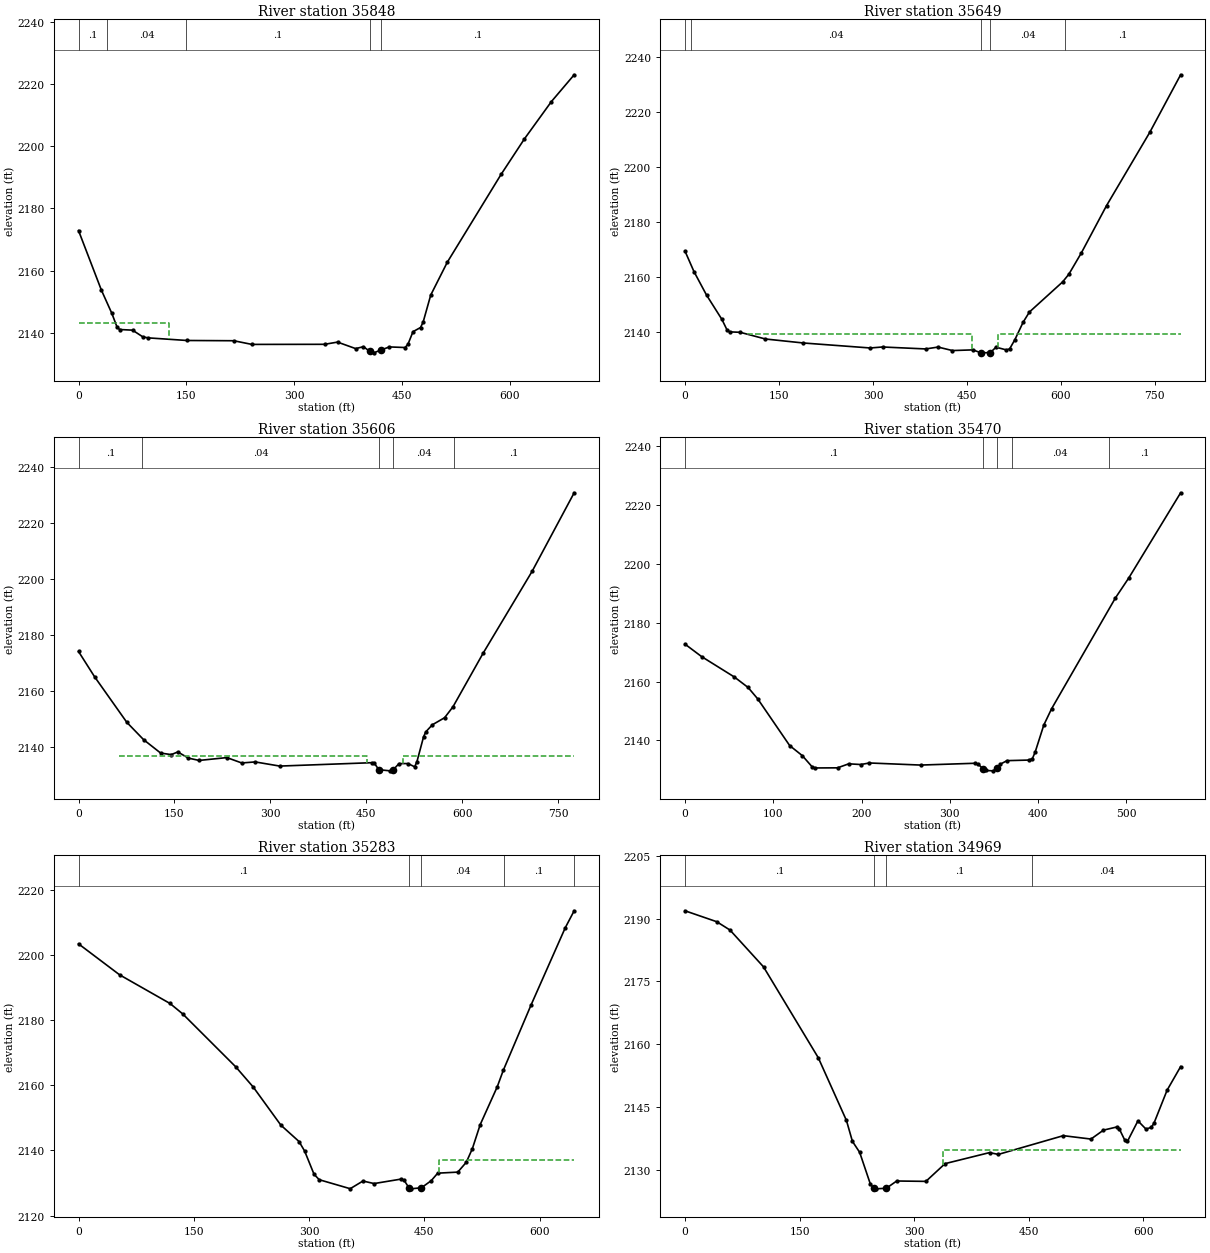
Type RM Length L Ch R = 1 ,35848   ,195,199.2,200.9
XS GIS Cut Line= 2
2114798.67386118190525.370233228 2115086.7917452191152.095554299
#Sta/Elev= 30
       0 2172.86    31.9 2153.67    46.3 2146.28    53.5 2141.91    57.1 2141.05
    75.2 2140.84    89.6 2138.67    96.9 2138.36     151 2137.52     216 2137.44
   241.3 2136.26   342.4 2136.29   360.5    2137   385.7 2134.91   396.6 2135.53
   405.42133.996     411 2133.55   420.82134.469   432.7 2135.45   454.4 2135.26
   458.4 2136.25   465.5 2140.35     476 2141.69   479.6 2143.43   490.2 2152.13
   513.3  2162.7     588 2190.87   620.5 2202.29   658.1  2214.3   689.8 2222.92
#Mann= 5 ,-1 , 0
       0      .1       0      40     .04       0     150      .1       0
   405.4    .045       0   420.8      .1       0
#XS Ineff= 2 , 0
          125.62 2143.22
Permanent Ineff=
       F       F
Bank Sta=405.4,420.8
XS Rating Curve= 0 ,0
Exp/Cntr(USF)=0,0
Exp/Cntr=0.5,0.3

Type RM Length L Ch R = 1 ,35649   ,44.5,43.3,41.2
XS GIS Cut Line= 5
2114766.70975229190553.472212989 2114823.7239649190817.649198532
2114820.73397587191010.6180523132114836.53042951191093.179134979
2114804.54539142191334.886564378
#Sta/Elev= 30
       0 2169.47    14.3 2162.02    34.4 2153.44      59 2144.55    67.2  2140.7
    71.4 2140.04    88.1 2139.88   128.4 2137.44   188.8 2135.99   295.7 2134.17
   315.3 2134.53   384.2 2133.82   403.9  2134.5   426.9 2133.23   459.7 2133.48
   472.12132.413     473  2132.4   487.42132.499   496.4 2134.45   513.1 2133.46
   518.2 2133.85   526.5 2137.17   539.8 2143.59   549.8 2147.28   602.8 2158.24
   612.7 2161.04   632.6 2168.78   672.8 2186.01   741.8 2212.69   791.1 2233.68
#Mann= 5 ,-1 , 0
       0      .1       0      10     .04       0   472.1    .045       0
   487.4     .04       0  607.31      .1       0
#XS Ineff= 2 ,-1
   99.77   458.12139.284  499.81  792.132139.406
Permanent Ineff=
       F       F
Bank Sta=472.1,487.4
XS Rating Curve= 0 ,0
Exp/Cntr=0.5,0.3

Type RM Length L Ch R = 1 ,35606   ,138.5,136,134.9
XS GIS Cut Line= 5
2114730.82454497190572.3651640252114779.14389219190834.807500601
2114778.12587819191024.9812372212114809.23576966191109.143969131
2114777.97875229   191334.972734
#Sta/Elev= 30
       0 2174.22      25 2165.23    75.5 2148.93   101.8 2142.73   128.4 2137.96
     145 2137.41   155.1 2138.36   171.8 2136.16   188.5 2135.33   231.9 2136.35
   255.1 2134.43   276.1  2134.8   314.5 2133.32   458.9 2134.53   462.6 2134.26
   469.4 2132.03   486.9 2131.62   491.72131.954   500.9  2134.2   514.9 2134.22
   525.4 2133.06     529 2134.94   539.4 2143.83   542.9 2145.56     553 2148.05
   572.2 2150.58   585.3 2154.48   632.5 2173.64     709 2202.83   774.7 2230.85
#Mann= 5 ,-1 , 0
       0      .1       0     100     .04       0   469.4    .045       0
   491.7     .04       0  586.76      .1       0
#XS Ineff= 2 ,-1
   63.48  450.67    2137  507.41  786.52    2137
Permanent Ineff=
       F       F
Bank Sta=469.4,491.7
XS Rating Curve= 0 ,0
Exp/Cntr=0.5,0.3

Type RM Length L Ch R = 1 ,35470   ,187.6,186.4,184
XS GIS Cut Line= 2
2114531.29252407190814.2830354632114768.13383525191323.420943938
#Sta/Elev= 30
       0  2172.7    18.8 2168.47    55.9 2161.54    71.5 2157.98    82.4 2154.11
   118.6 2138.25     133 2134.81   143.9 2131.08   147.5 2130.65   172.8 2130.69
   185.5 2132.05   199.1 2131.82     209 2132.34   266.9 2131.63   328.4 2132.24
   332.5 2131.84   337.4 2130.42   341.1 2129.79   348.9 2129.67     3542130.635
   357.4 2131.96   364.8 2133.13   389.9 2133.33   393.6 2133.84   396.7 2136.03
   406.5 2145.23   415.3 2150.74   487.6 2188.37   502.9 2195.23   561.5 2224.09
#Mann= 5 ,-1 , 0
       0      .1       0   337.4    .045       0     354      .1       0
     370     .04       0     480      .1       0
Bank Sta=337.4,354
XS Rating Curve= 0 ,0
Exp/Cntr(USF)=0,0
Exp/Cntr=0.3,0.1

Type RM Length L Ch R = 1 ,35283   ,308.5,314.6,314.7
XS GIS Cut Line= 3
     2114435.437      190838.766     2114442.438      191102.451
     2114649.763      191422.453
#Sta/Elev= 30
       0 2203.38    53.5 2193.87   119.1 2185.08   135.6 2181.89   204.5 2165.68
   227.5 2159.42   263.4 2147.75     287 2142.74   294.3 2139.81   306.5 2132.71
   313.3 2131.02   353.6 2128.26   370.2 2130.62   384.7 2129.84   420.3 2131.23
   423.8 2130.83   430.12128.529   432.3 2128.22   446.32128.551     459 2130.71
   467.5 2133.03   493.6 2133.35   504.7 2136.37   512.6 2140.54   522.8 2147.92
     545 2159.53   552.8 2164.55   589.2 2184.73   633.5 2208.31   645.1 2213.52
#Mann= 5 ,-1 , 0
       0      .1       0   430.1    .045       0   446.3     .04       0
  553.78      .1       0  645.07     .12       0
#XS Ineff= 2 , 0
                          469.49            2137
Permanent Ineff=
       F       F
Bank Sta=430.1,446.3
XS Rating Curve= 0 ,0
Exp/Cntr=0.3,0.1

Type RM Length L Ch R = 1 ,34969   ,382.8,376.2,367.8
XS GIS Cut Line= 3
     2114206.915      191013.641     2114288.791      191254.961
     2114417.354      191627.504
#Sta/Elev= 30
       0 2191.85    41.6 2189.24    58.9 2187.26   102.8 2178.48   174.5 2156.81
   211.4 2141.84   219.2 2136.87   228.7 2134.24   242.5 2126.79   247.22125.645
   249.5 2125.54   263.62125.677   277.2 2127.41   315.4 2127.32   340.5 2131.55
   398.7 2134.18   410.2 2133.75   495.3 2138.22   531.5 2137.41   547.9 2139.54
   565.3 2140.29   568.7  2139.8   575.7 2137.18   579.2 2136.84     593 2141.75
   603.5 2139.79   610.4  2140.2   613.9 2141.15   631.2 2149.07   648.9 2154.69
#Mann= 4 ,-1 , 0
       0      .1       0   247.2    .045       0   263.6      .1       0
  454.83     .04       0
#XS Ineff= 2 , 0
                          338.31         2134.88
Permanent Ineff=
       F       F
Bank Sta=247.2,263.6
XS Rating Curve= 0 ,0
Exp/Cntr=0.3,0.1

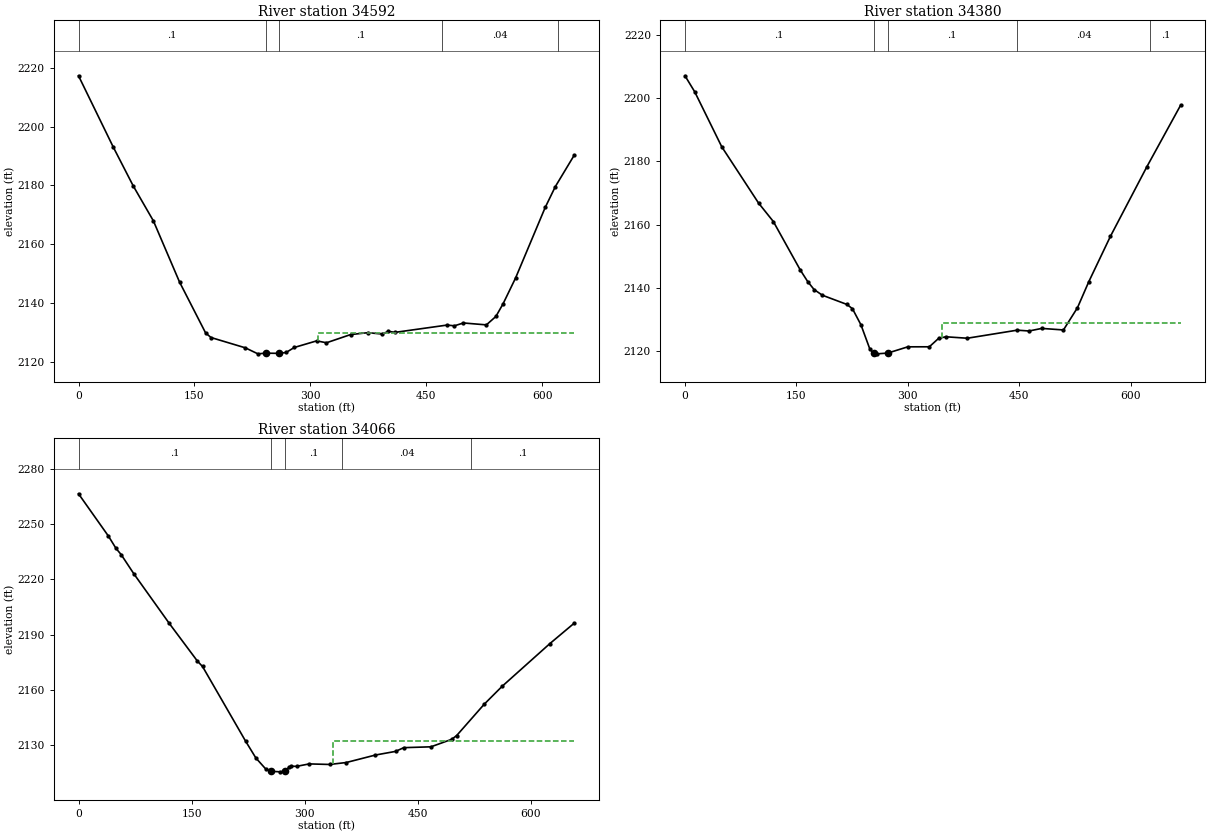
Type RM Length L Ch R = 1 ,34592   ,215.8,212.8,210
XS GIS Cut Line= 2
     2113835.452      191346.323     2114333.581      191750.372
#Sta/Elev= 30
       0 2217.25    44.8 2193.11    70.8 2179.83    96.9 2167.94   130.7 2147.18
   164.5 2129.85   171.5  2128.3   215.9  2124.8   232.1 2122.76   242.32122.993
   259.82122.917   268.7 2123.23   279.2 2124.92   308.2 2127.17   320.9 2126.52
   352.1 2129.31   374.5 2129.95   392.6  2129.5   401.1 2130.41   409.5 2130.05
   477.1 2132.54   486.4 2132.28   498.1 2133.25   527.8  2132.6   540.1 2135.46
   549.4 2139.76   565.6 2148.54   603.9 2172.49     617 2179.58   641.4 2190.23
#Mann= 5 ,-1 , 0
       0      .1       0   242.3    .045       0   259.8      .1       0
     470     .04       0     620      .1       0
#XS Ineff= 2 , 0
                          309.32         2129.69
Permanent Ineff=
       F       F
Bank Sta=242.3,259.8
XS Rating Curve= 0 ,0
Exp/Cntr=0.3,0.1

Type RM Length L Ch R = 1 ,34380   ,315.9,313.3,308.9
XS GIS Cut Line= 3
     2113648.356      191659.181     2113833.397       191636.82
     2114260.426      191857.335
#Sta/Elev= 30
       0 2207.11    13.1 2202.04    49.5 2184.63      99 2166.83   118.9 2160.98
   155.2 2145.62   165.1 2141.99   173.7 2139.46   184.8 2137.66     218 2134.73
   225.4 2133.37   236.8 2128.29   248.8  2120.6   253.7 2119.35   258.5  2119.1
   272.92119.344   299.9 2121.32   328.8 2121.33   341.3 2123.99     351  2124.5
   379.9 2124.04     447 2126.59   463.1 2126.33   480.1 2127.15   509.3 2126.66
   528.2 2133.71   543.4 2141.93   572.6 2156.33   621.3  2178.2     667  2197.8
#Mann= 5 ,-1 , 0
       0      .1       0   253.7    .045       0   272.9      .1       0
  446.39     .04       0  626.39      .1       0
#XS Ineff= 2 , 0
                          345.37         2128.75
Permanent Ineff=
       F       F
Bank Sta=253.7,272.9
XS Rating Curve= 0 ,0
Exp/Cntr=0.3,0.1

Type RM Length L Ch R = 1 ,34066   ,339.6,347.7,352.2
XS GIS Cut Line= 3
     2113524.356      191894.313     2113943.071      191993.844
     2113989.651      192216.098
#Sta/Elev= 30
       0 2266.51    39.7  2243.5    49.8 2236.78    56.5  2233.5    73.4 2223.02
   120.3 2196.11   157.7 2175.58   164.5 2172.64   221.6 2132.09   235.3 2122.89
   248.6 2116.82   254.72115.683   267.9 2115.38   273.92115.788   279.1 2117.83
   282.5 2118.43   289.2 2118.36   306.1 2119.69   333.1 2119.39   355.1 2120.44
   393.8 2124.51   420.7  2126.5   431.4 2128.52   467.5 2128.98   494.9 2133.03
   501.6 2135.09   538.4 2152.23   561.9 2161.85   625.4 2185.12   657.5 2196.16
#Mann= 5 ,-1 , 0
       0      .1       0   254.7    .045       0   273.9      .1       0
     350     .04       0  520.38      .1       0
#XS Ineff= 2 , 0
                           337.8         2132.16
Permanent Ineff=
       F       F
Bank Sta=254.7,273.9
XS Rating Curve= 0 ,0
Exp/Cntr=0.3,0.1