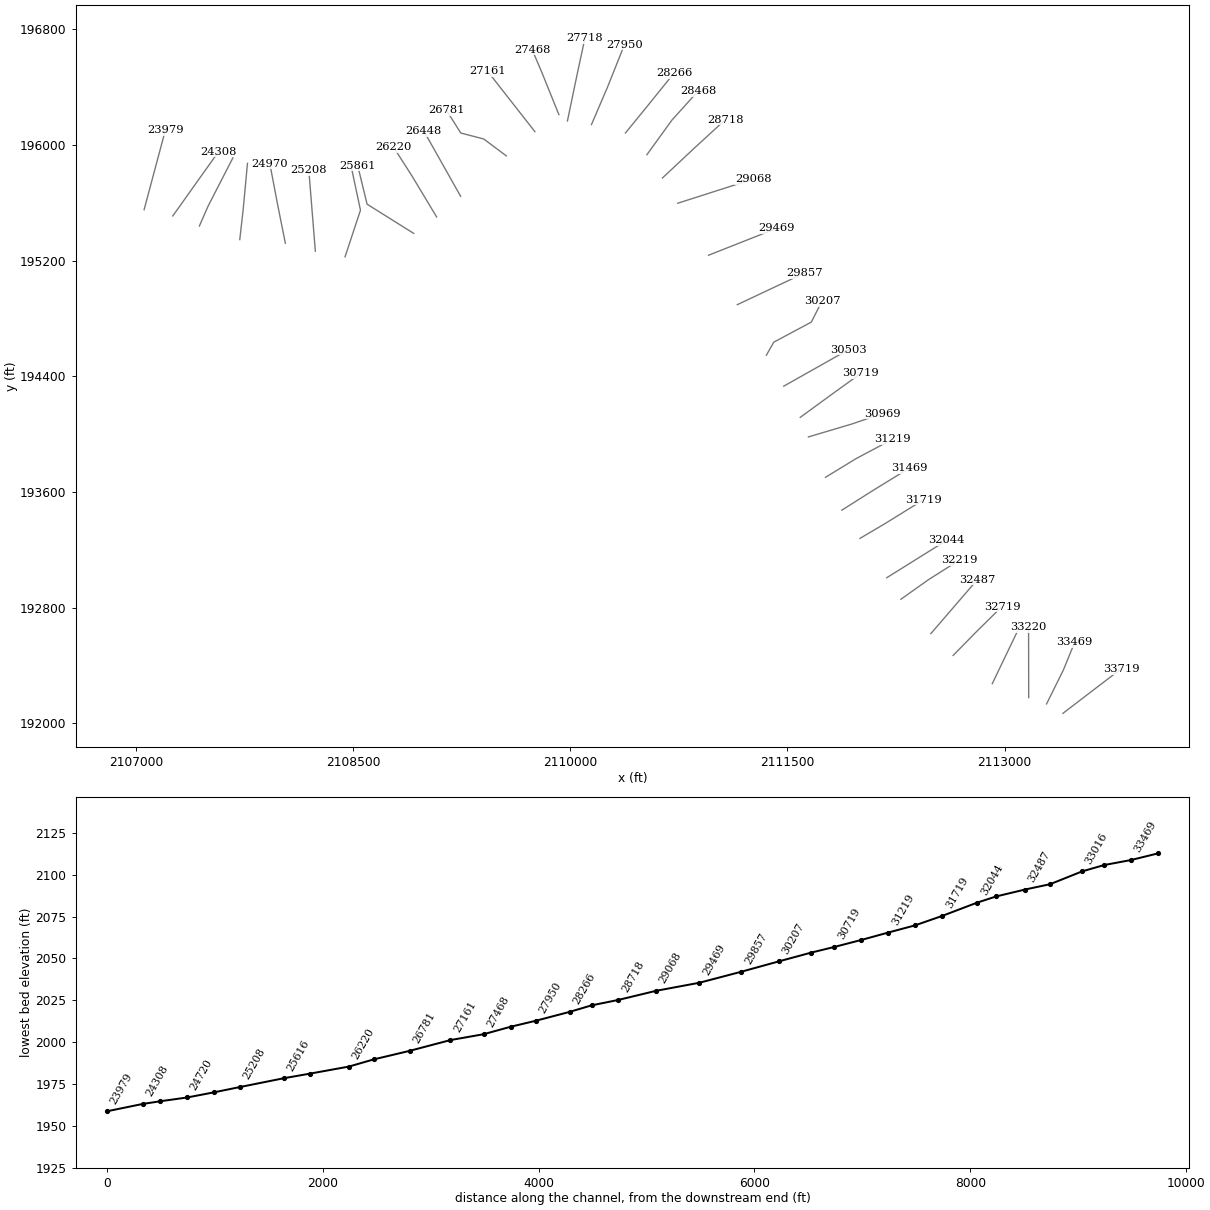
HEC-RAS study TRKYCK.prj: TRKYCK

--- TRKYCK.g01 (geometry) --- (continued)

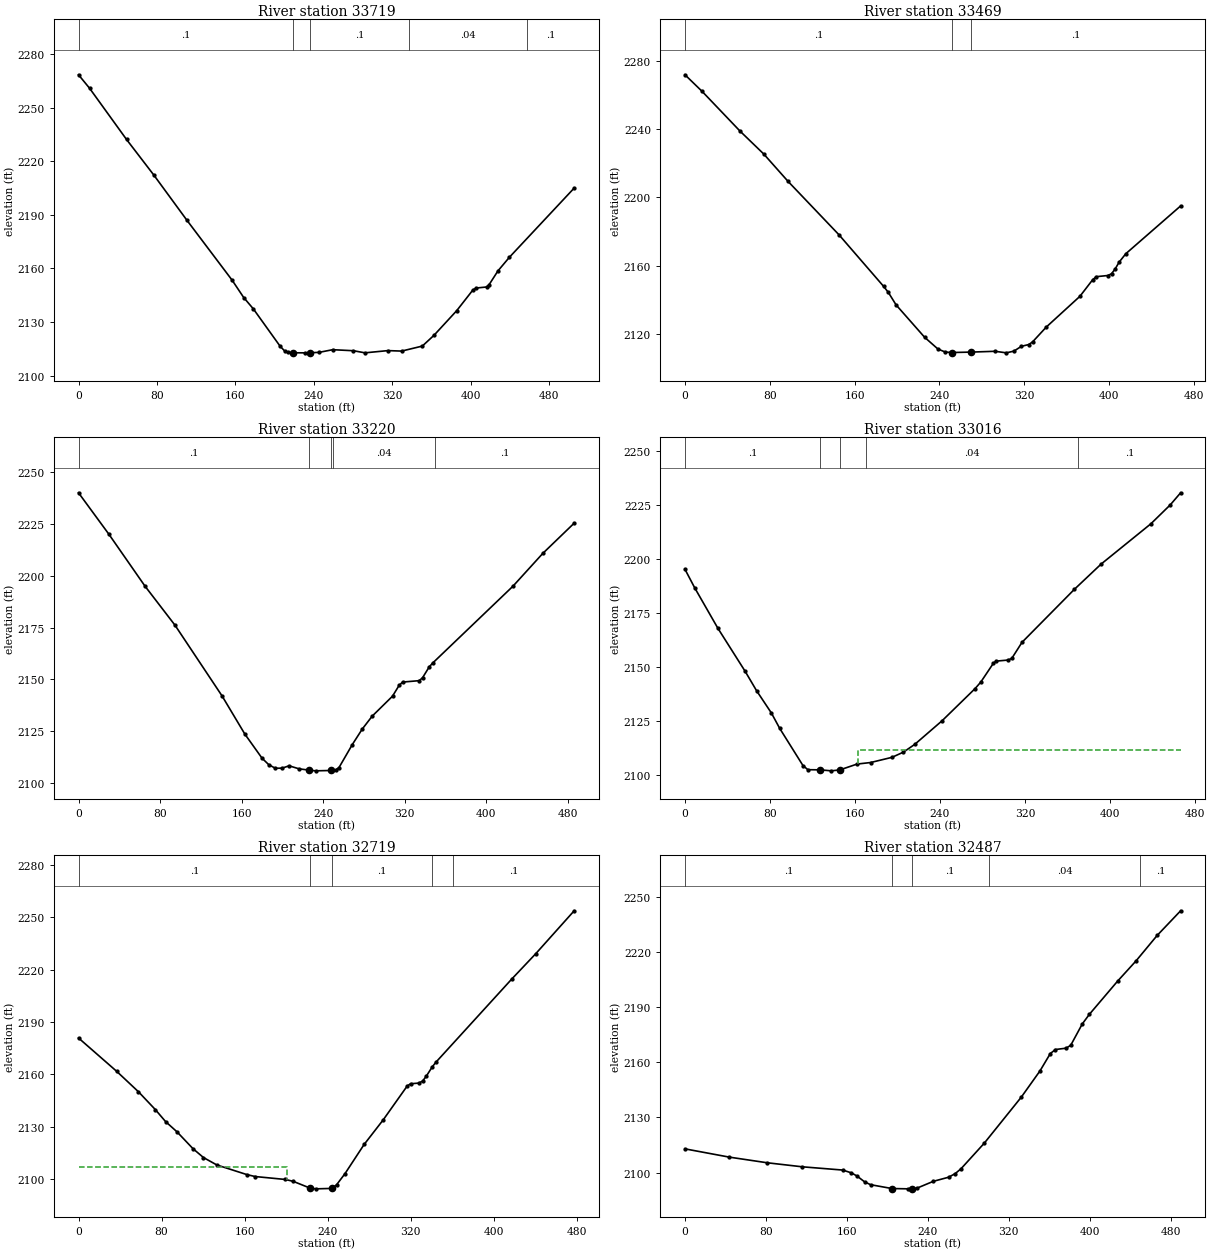
Type RM Length L Ch R = 1 ,33719   ,243.4,250,257
XS GIS Cut Line= 3
     2113403.002      192069.772     2113583.392      192208.178
     2113804.666      192376.799
#Sta/Elev= 30
       0 2268.54    11.3 2260.97      49 2232.28    76.9 2212.29   110.6    2187
   156.8 2153.34   168.5 2143.71   178.4  2137.3   205.6 2116.45   210.2 2113.81
     214 2112.91   218.52112.736   230.6 2112.71   236.22112.773   245.3 2112.97
   259.3 2114.47   280.5 2113.89   292.2 2112.71   315.6 2113.96   329.6 2113.69
   350.7  2116.5   362.6 2122.53   385.8 2136.35   402.2 2147.87   405.5 2149.02
   416.2 2149.61   418.6 2150.72   427.9 2158.67   439.6 2166.31   505.6 2205.04
#Mann= 5 ,-1 , 0
       0      .1       0   218.5    .045       0   236.2      .1       0
  337.37     .04       0  457.37      .1       0
Bank Sta=218.5,236.2
XS Rating Curve= 0 ,0
Exp/Cntr=0.3,0.1

Type RM Length L Ch R = 1 ,33469   ,242.3,248.8,254.8
XS GIS Cut Line= 3
     2113290.082      192135.185     2113405.898      192368.859
     2113484.091      192560.236
#Sta/Elev= 30
       0 2271.93    16.1 2262.22    51.8 2238.95    74.3 2225.43    97.3 2209.32
   145.3    2178   187.3  2147.8   191.8 2144.23   199.1 2136.91     226 2117.91
   238.6 2110.99   245.6 2109.21   251.92108.946   269.72109.194   292.5 2109.67
   303.1 2108.76   310.2 2109.76   317.3 2112.58   324.3 2113.64   327.9 2115.21
   340.8  2123.9   372.5 2141.93   384.6 2151.71   388.1 2153.46   398.8 2154.14
   402.3 2155.16   405.9 2158.13   409.4 2161.91   415.8 2166.93   467.5 2194.97
#Mann= 3 ,-1 , 0
       0      .1       0   251.9    .045       0   269.7      .1       0
Bank Sta=251.9,269.7
XS Rating Curve= 0 ,0
Exp/Cntr=0.3,0.1

Type RM Length L Ch R = 1 ,33220   ,207.1,204.2,194.3
XS GIS Cut Line= 2
       2113166.6      192178.767 2113165.8533118192665.008391631
#Sta/Elev= 30
       0 2240.17    29.7  2220.2    65.2 2195.05    94.7 2176.12   140.7 2142.05
   163.2  2123.5     180 2111.89   186.6 2108.74   193.1    2107   199.7 2107.06
   206.6 2108.19   216.4 2106.72   226.2 2106.11   232.5 2105.76   247.72105.936
   252.2 2106.19   255.5 2107.34   268.6 2118.48   278.4 2126.01   288.1 2132.21
     308 2141.84   314.5 2147.08   317.9 2148.67   334.2 2149.35   337.5 2150.78
     344 2155.99   347.3 2157.81   426.1 2194.98   455.5  2210.9   486.2 2225.48
#Mann= 5 ,-1 , 0
       0      .1       0   226.2    .045       0   247.7      .1       0
     250     .04       0     350      .1       0
Bank Sta=226.2,247.7
XS Rating Curve= 0 ,0
Exp/Cntr=0.3,0.1

Type RM Length L Ch R = 1 ,33016   ,299.3,296.9,289.8
XS GIS Cut Line= 2
     2112914.945       192275.04     2113116.748        192695.7
#Sta/Elev= 30
       0 2195.12     9.2 2186.52      31 2167.85    56.7 2147.93    67.4 2139.01
    81.3 2128.75    89.2 2121.58   111.1  2104.4   115.7 2102.51   127.22102.437
   137.8 2101.98   145.82102.414     162 2105.11   174.7 2105.82   194.8 2108.21
   205.7 2110.64   216.3 2114.21   242.1 2125.15   273.1 2139.99   278.5 2143.02
   290.3 2151.68     293 2152.69   303.9 2153.17   307.6 2153.91   317.3 2161.39
   366.5 2185.83   391.7 2197.52   438.6 2216.16   456.8 2224.88   466.6 2230.49
#Mann= 5 ,-1 , 0
       0      .1       0   127.2    .045       0   145.8      .1       0
     170     .04       0     370      .1       0
#XS Ineff= 2 , 0
                          162.88         2111.55
Permanent Ineff=
       F       F
Bank Sta=127.2,145.8
XS Rating Curve= 0 ,0
Exp/Cntr=0.3,0.1

Type RM Length L Ch R = 1 ,32719   ,230.3,231.2,232.5
XS GIS Cut Line= 3
     2112644.552      192470.386     2112806.469      192635.194
     2112981.886      192808.451
#Sta/Elev= 30
       0  2180.8    36.7 2161.73    57.8 2149.95      74 2139.77    83.9 2132.88
    94.9 2127.01   110.3 2117.35   120.4 2112.27   133.3 2108.01   162.2  2102.5
   170.1 2101.39   199.3  2099.7   206.9 2098.62   223.42094.683   229.1 2094.33
     2442094.571   248.6  2096.6   256.8 2103.06   275.2 2119.76   293.7 2133.95
   316.7 2153.26     320 2154.57   327.9 2154.94   331.6 2156.13   335.2 2158.98
   340.8  2164.2   344.4 2166.92   417.4 2214.54   440.6 2229.12   477.6 2253.71
#Mann= 5 ,-1 , 0
       0      .1       0   223.4    .045       0     244      .1       0
  341.04     .04       0  361.04      .1       0
#XS Ineff= 2 , 0
          200.51 2106.61
Permanent Ineff=
       F       F
Bank Sta=223.4,244
XS Rating Curve= 0 ,0
Exp/Cntr=0.3,0.1

Type RM Length L Ch R = 1 ,32487   ,270.9,268.8,262.8
XS GIS Cut Line= 2
     2112490.717      192621.249     2112810.383      192992.531
#Sta/Elev= 30
       0 2112.89    43.8  2108.4      81 2105.35   115.9 2103.14   155.9 2101.37
   164.5 2099.84   170.1  2098.1   177.5 2094.97   183.4 2093.42   204.52091.328
   220.6 2091.16   224.1 2091.16   229.5 2091.58   245.5 2095.25   260.6 2097.48
   267.1 2099.45   272.8 2102.06   295.8 2115.97   332.3 2140.93   350.9 2155.28
   361.1  2164.7   366.2  2166.9   376.7 2167.62   381.3 2169.22   392.7  2180.8
   399.7 2186.02   427.6 2204.07   445.9 2215.11   466.7 2228.91   489.9 2242.31
#Mann= 5 ,-1 , 0
       0      .1       0   204.5    .045       0   224.1      .1       0
     300     .04       0     450      .1       0
Bank Sta=204.5,224.1
XS Rating Curve= 0 ,0
Exp/Cntr=0.3,0.1

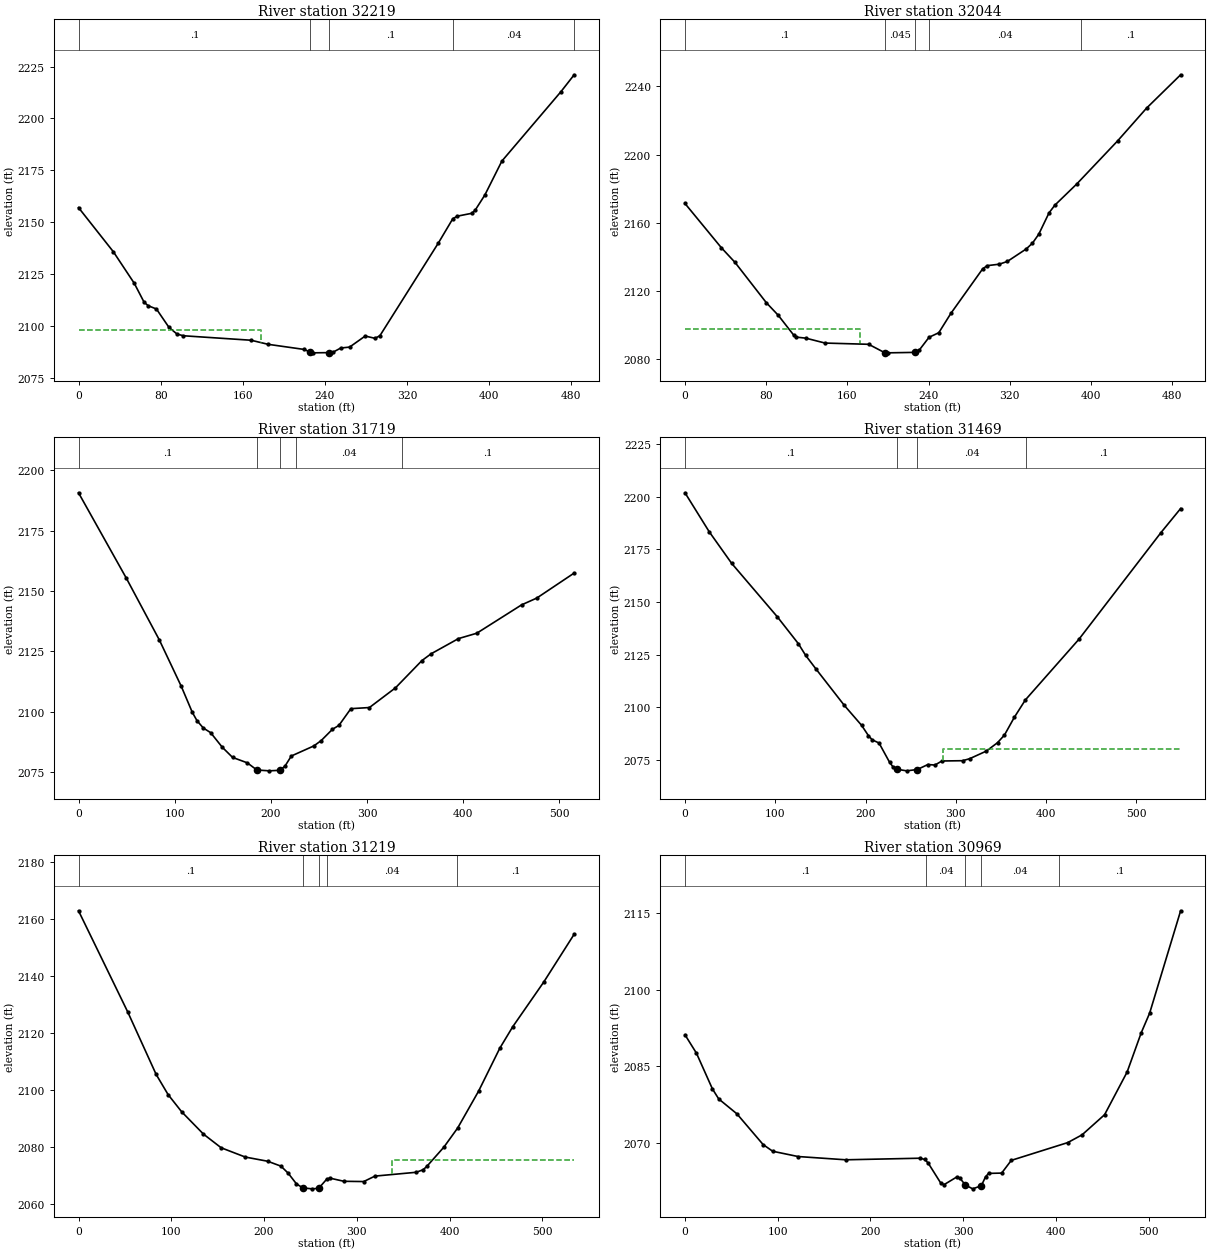
Type RM Length L Ch R = 1 ,32219   ,173.9,174.5,170.4
XS GIS Cut Line= 3
     2112283.853      192858.854     2112475.341       192994.76
     2112684.711      193127.419
#Sta/Elev= 30
       0 2157.03      34  2135.7    54.3 2120.54    63.9 2111.39    67.9 2109.73
    75.9 2108.14    88.1 2099.29      96 2096.05   102.2 2095.25   168.1 2093.09
   184.6 2091.13   219.9 2088.65   225.8 2087.27   228.8 2087.02   243.82087.128
   248.3 2087.45   255.4 2089.34     264 2089.79   279.2 2095.12   288.7 2094.02
   293.5 2095.26   350.5    2140   364.5 2151.66   368.8 2152.89   382.9 2154.27
   386.2 2155.71   395.7 2163.07   412.3 2179.45   469.8 2212.89   482.7 2221.05
#Mann= 5 ,-1 , 0
       0      .1       0   225.8    .045       0   243.8      .1       0
  364.82     .04       0  482.67      .1       0
#XS Ineff= 2 , 0
          177.38 2097.99
Permanent Ineff=
       F       F
Bank Sta=225.8,243.8
XS Rating Curve= 0 ,0
Exp/Cntr=0.3,0.1

Type RM Length L Ch R = 1 ,32044   ,326,325.5,325.9
XS GIS Cut Line= 2
     2112185.851      193007.477     2112600.117      193266.195
#Sta/Elev= 30
       0 2171.19    35.8 2145.21    49.3 2136.56    80.2 2112.83    91.8 2105.52
   107.3 2093.67   109.6 2092.62   119.1    2092     138 2089.12     181 2088.39
   196.72083.491   200.1 2083.37   226.3 2083.64   230.9 2085.02   240.5 2092.52
   250.1  2095.2     262 2106.56   293.2 2132.66   297.7 2134.63   309.6 2135.49
   317.6 2137.09   336.2 2144.44   342.4 2147.86   348.6 2153.12   358.7 2165.65
   364.4 2170.17     386 2182.64   426.3    2208   454.8 2227.25   488.4 2246.88
#Mann= 5 ,-1 , 0
       0      .1       0   196.7    .045       0   226.3      .1       0
     240     .04       0     390      .1       0
#XS Ineff= 2 , 0
          172.54 2097.43
Permanent Ineff=
       F       F
Bank Sta=196.7,226.3
XS Rating Curve= 0 ,0
Exp/Cntr=0.3,0.1

Type RM Length L Ch R = 1 ,31719   ,247.9,250,248.3
XS GIS Cut Line= 3
2112001.07182834193279.546594552     2112170.365      193379.441
     2112441.446      193547.245
#Sta/Elev= 30
       0 2190.71    49.8 2155.24    84.1 2129.64   106.9 2110.41   118.3 2099.68
   123.2  2096.2   129.8 2093.15   137.4 2091.23   149.5 2085.18   160.2 2080.97
   175.5 2078.72   185.5 2075.75   198.4  2075.4   209.4 2075.63   214.7 2077.36
   221.3 2081.55   244.7 2085.73   252.3 2087.93     264 2092.61   270.8 2094.25
   283.2 2101.18   302.5 2101.65   329.6 2109.82   357.1 2121.13   366.7 2123.95
   395.1 2130.24   414.1 2132.46   460.7 2144.22   476.5 2147.04   515.4 2157.42
#Mann= 5 ,-1 , 0
       0      .1       0   185.5    .045       0   209.4      .1       0
  226.57     .04       0  336.57      .1       0
Bank Sta=185.5,209.4
XS Rating Curve= 0 ,0
Exp/Cntr=0.3,0.1

Type RM Length L Ch R = 1 ,31469   ,251.2,250,249.1
XS GIS Cut Line= 3
 2111875.5878574193474.450237661     2112085.064      193607.242
     2112341.319      193764.854
#Sta/Elev= 30
       0 2201.96    26.8 2183.46    51.7 2168.41   102.2 2143.04   125.5 2130.27
   133.7 2124.63   144.9  2118.3   176.5 2100.88   195.6 2091.42   203.2 2086.49
   207.4 2084.51   214.9 2083.02   226.7 2073.76   230.4 2071.67   234.3 2070.57
   245.5 2069.79   257.2 2070.41   269.1  2072.8   276.8 2072.53   284.5 2074.47
   307.5 2074.61   315.3 2075.57   333.7 2079.17   346.1 2083.16   353.8  2086.8
   364.7 2095.21   376.9 2103.47   436.3 2132.35   527.1 2183.03   548.9 2194.47
#Mann= 4 ,-1 , 0
       0      .1       0   234.3    .045       0   257.2     .04       0
  378.02      .1       0
#XS Ineff= 2 , 0
                          285.61         2080.39
Permanent Ineff=
       F       F
Bank Sta=234.3,257.2
XS Rating Curve= 0 ,0
Exp/Cntr=0.3,0.1

Type RM Length L Ch R = 1 ,31219   ,251.3,250,245.7
XS GIS Cut Line= 3
     2111762.517      193701.703     2111974.442      193831.137
2112227.00294514193965.411816284
#Sta/Elev= 30
       0 2162.84      53 2127.46    83.7 2105.54    96.6 2098.47   111.3 2092.42
   134.7 2084.64   153.8 2079.85   179.8  2076.6     204 2075.13   218.3 2073.41
     226 2070.97     235  2067.2   241.8 2065.81   251.7 2065.47   258.92065.643
   267.6 2068.85   270.9 2069.23   286.2 2068.11   307.5 2068.02   319.6 2069.93
   364.2 2071.27   371.6 2072.17   375.5 2073.32   393.9 2080.06   408.8 2086.78
   431.3 2099.65   454.2  2114.7   468.2 2122.25   501.7 2137.93   534.4 2154.63
#Mann= 5 ,-1 , 0
       0      .1       0   241.8    .045       0   258.9      .1       0
  268.33     .04       0  408.33      .1       0
#XS Ineff= 2 , 0
                          338.31         2075.63
Permanent Ineff=
       F       F
Bank Sta=241.8,258.9
XS Rating Curve= 0 ,0
Exp/Cntr=0.3,0.1

Type RM Length L Ch R = 1 ,30969   ,244.4,250,253.3
XS GIS Cut Line= 3
     2111644.872       193980.86      2111944.93      194070.211
     2112154.251      194142.272
#Sta/Elev= 30
       0 2091.17    12.4 2087.56    29.6 2080.58    36.4 2078.62      56 2075.71
    84.3 2069.69    94.6 2068.39   121.9 2067.36   173.3 2066.72   253.7 2067.03
   258.6 2066.78   262.3 2066.07     276 2062.12   279.5 2061.87   293.1 2063.36
   296.6 2063.11   302.32061.793   310.3 2061.04   319.6 2061.65   324.1 2063.39
   327.4 2064.06   341.5 2064.12   351.9 2066.61   412.7 2070.08   428.2  2071.6
   452.5 2075.54   476.8 2083.89     492 2091.56   501.1 2095.41   534.5 2115.42
#Mann= 5 ,-1 , 0
       0      .1       0     260     .04       0   302.3    .045       0
   319.6     .04       0  403.08      .1       0
Bank Sta=302.3,319.6
XS Rating Curve= 0 ,0
Exp/Cntr=0.3,0.1

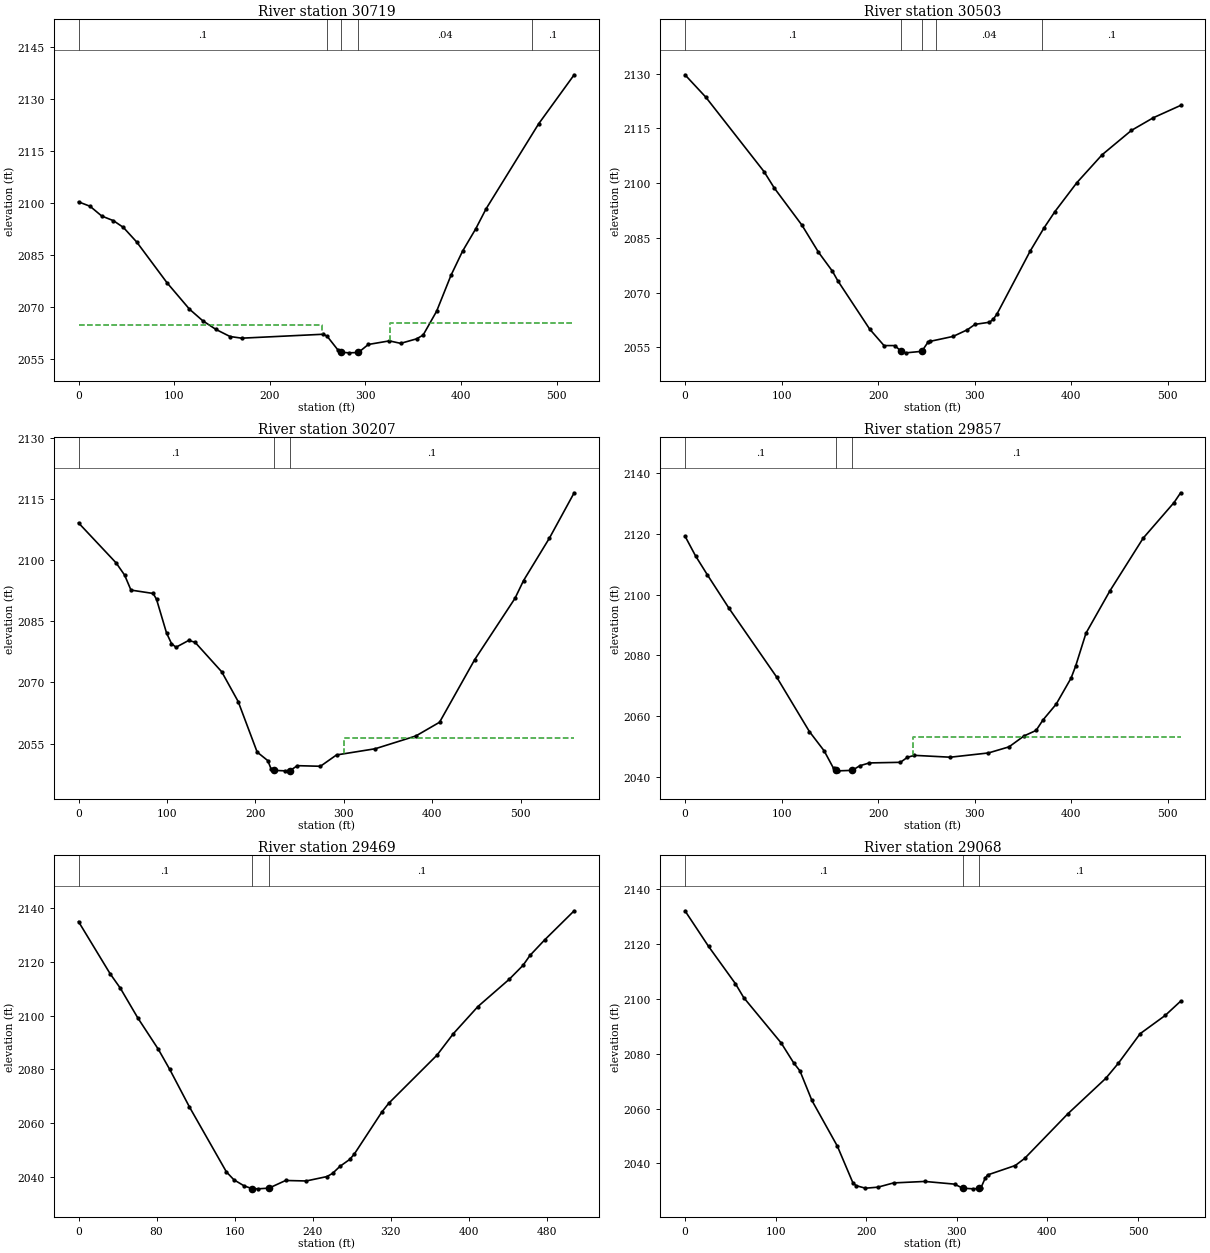
Type RM Length L Ch R = 1 ,30719   ,216.8,215.2,212.9
XS GIS Cut Line= 3
     2111587.968      194115.887     2111817.698      194283.684
     2112007.461      194420.152
#Sta/Elev= 30
       0 2100.33    12.1 2099.05    24.3 2096.24    36.5 2094.91    46.9 2092.97
    60.9 2088.75    92.5 2077.05     116 2069.44   129.9  2066.1   143.8 2063.59
   158.4 2061.57   170.6 2061.09   255.9 2062.22   259.9 2061.66     271 2057.77
   274.72057.042   282.7 2056.87   292.62056.969     303 2059.28     325 2060.31
   336.8  2059.6   353.5  2060.9   360.3 2061.99   374.4 2068.85   389.4 2079.17
   401.5 2086.12   415.4 2092.62   426.1 2098.32   481.1  2122.8   518.2  2136.9
#Mann= 5 ,-1 , 0
       0      .1       0     260     .04       0   274.7    .045       0
   292.6     .04       0  474.48      .1       0
#XS Ineff= 2 , 0
          254.96 2064.84  325.53         2065.49
Permanent Ineff=
       F       F
Bank Sta=274.7,292.6
XS Rating Curve= 0 ,0
Exp/Cntr=0.3,0.1

Type RM Length L Ch R = 1 ,30503   ,297.1,296.8,296.7
XS GIS Cut Line= 2
     2111474.038       194331.55     2111921.029      194583.773
#Sta/Elev= 30
       0 2129.72    21.5  2123.6    81.8 2103.19    92.5 2098.66   121.1 2088.49
   138.2 2081.08   152.7 2075.85   158.2 2073.25   191.2    2060   206.1 2055.47
   217.4 2055.47   223.82053.865   228.7 2053.48   245.22053.894   251.4 2056.32
   253.8 2056.63   277.7 2057.99   292.4 2059.81   300.3 2061.29   315.3 2061.87
   319.1 2062.68   322.9 2064.06   357.4 2081.37   371.8 2087.75   383.1 2092.23
   405.7 2100.12   431.9 2107.79   462.2 2114.46     485 2117.95   513.2 2121.32
#Mann= 5 ,-1 , 0
       0      .1       0   223.8    .045       0   245.2      .1       0
     260     .04       0     370      .1       0
Bank Sta=223.8,245.2
XS Rating Curve= 0 ,0
Exp/Cntr=0.3,0.1

Type RM Length L Ch R = 1 ,30207   ,349.2,349.2,348.3
XS GIS Cut Line= 4
     2111354.176      194545.793     2111404.999       194635.69
     2111664.344      194774.411     2111738.659      194919.536
#Sta/Elev= 30
       0 2109.18    42.5 2099.36    52.1 2096.37    59.3 2092.68    84.4 2091.85
    88.2 2090.42    99.5 2082.16   105.1 2079.56   110.2 2078.64   124.5 2080.31
   131.7 2079.88   161.9 2072.62   180.5 2065.32     202  2052.9     214 2050.81
   217.7 2048.79   220.92048.416   233.6  2048.3   239.32048.368   247.4 2049.57
   273.5 2049.42   291.7  2052.2   335.4 2053.72   381.4 2056.86   408.2 2060.23
   447.9 2075.59   493.5 2090.66   503.2 2095.03   532.5 2105.47   560.4 2116.57
#Mann= 3 ,-1 , 0
       0      .1       0   220.9    .045       0   239.3      .1       0
#XS Ineff= 2 , 0
                          299.81         2056.25
Permanent Ineff=
       F       F
Bank Sta=220.9,239.3
XS Rating Curve= 0 ,0
Exp/Cntr=0.3,0.1

Type RM Length L Ch R = 1 ,29857   ,388.7,388.8,386.8
XS GIS Cut Line= 2
       2111153.2      194895.057     2111617.387      195113.862
#Sta/Elev= 30
       0 2119.25    10.9 2112.76    23.3 2106.45    45.7 2095.46    94.8 2072.97
   128.8 2055.01   144.1 2048.66   153.9 2042.87   156.72042.249   158.9 2042.09
   173.22042.247     181 2043.76   190.9 2044.69   223.1 2044.89   230.3 2046.54
   237.6 2047.18   274.7 2046.57   314.2 2047.97   335.5 2049.97   351.1 2053.57
   363.5 2055.36   370.8 2058.86   384.3 2063.99   399.7 2072.53   404.4 2076.43
   415.2 2087.34   439.9  2101.2   474.4 2118.56   506.4 2130.28   513.2 2133.48
#Mann= 3 ,-1 , 0
       0      .1       0   156.7    .045       0   173.2      .1       0
#XS Ineff= 2 , 0
                          236.26         2053.16
Permanent Ineff=
       F       F
Bank Sta=156.7,173.2
XS Rating Curve= 0 ,0
Exp/Cntr=0.3,0.1

Type RM Length L Ch R = 1 ,29469   ,401,400.8,399.1
XS GIS Cut Line= 3
     2110954.087      195236.647     2111125.458      195304.399
     2111426.764      195423.519
#Sta/Elev= 30
       0 2134.97    32.4 2115.58      43 2110.13    60.7 2099.18    81.8 2087.48
    93.6 2079.93   113.8 2065.96   151.7 2041.79   159.4 2038.87     170 2036.58
   177.82035.617   184.1 2035.51   195.32035.772   212.4 2038.62   233.5 2038.44
   254.7 2040.07   260.5 2041.25     268 2043.85   278.2 2046.48   282.9 2048.49
     311 2064.06   318.2 2067.38   367.6 2085.26   384.3 2093.22   409.6 2103.36
   441.7  2113.5   455.8 2118.67     463 2122.39   477.9 2128.11   508.3    2139
#Mann= 3 ,-1 , 0
       0      .1       0   177.8    .045       0   195.3      .1       0
Bank Sta=177.8,195.3
XS Rating Curve= 0 ,0
Exp/Cntr=0.3,0.1

Type RM Length L Ch R = 1 ,29068   ,342.6,349.7,355.2
XS GIS Cut Line= 2
     2110741.992      195596.372     2111263.035      195763.261
#Sta/Elev= 30
       0 2132.22    26.1 2119.18    55.7 2105.59    64.9 2100.49   106.2 2083.95
     120 2076.68   126.9 2073.76   140.1 2062.97   168.2 2046.28   185.5 2032.79
   188.9 2031.87   199.2 2030.93     213 2031.31   230.2 2032.86   264.7  2033.4
   297.5 2032.42   306.62030.928   318.4  2030.7     3252030.867   326.7 2031.11
   331.4  2034.6     334 2035.77   364.6 2039.22   374.9  2041.8   422.7 2058.13
   464.5 2071.05   478.3 2076.53   502.4 2087.34     530 2093.99   547.1 2099.21
#Mann= 3 ,-1 , 0
       0      .1       0   306.6    .045       0     325      .1       0
Bank Sta=306.6,325
XS Rating Curve= 0 ,0
Exp/Cntr=0.3,0.1

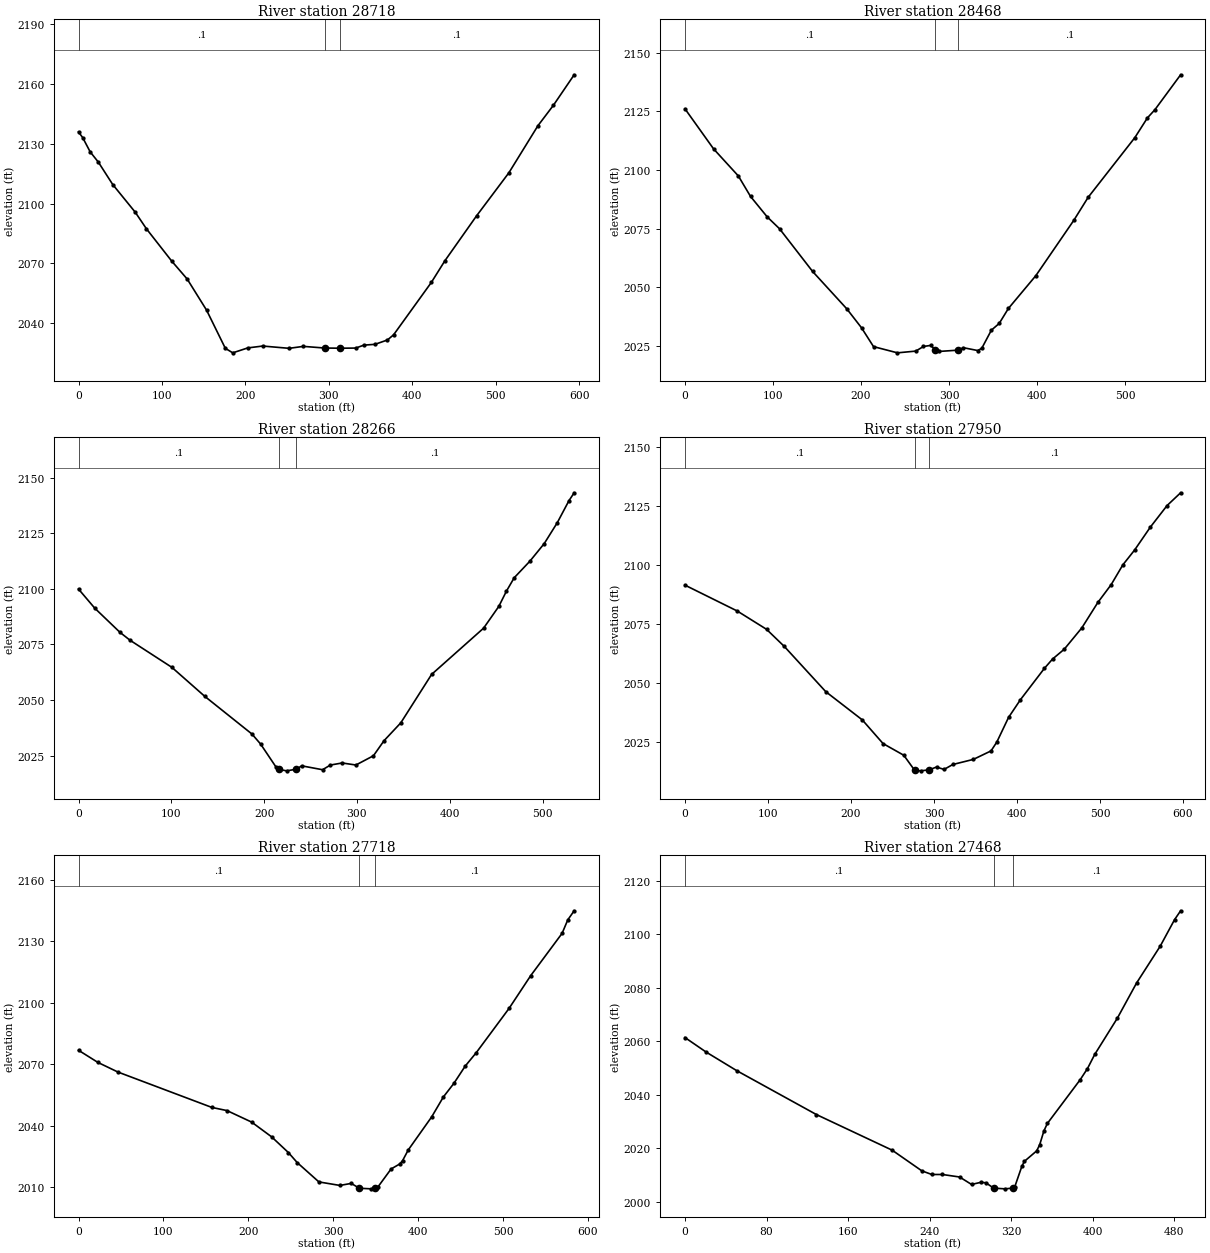
Type RM Length L Ch R = 1 ,28718   ,246.5,250,251.1
XS GIS Cut Line= 3
     2110636.063       195770.98     2110858.059      195978.901
     2111071.374       196174.77
#Sta/Elev= 30
       0 2135.84       5    2133      14 2125.85    23.8 2120.71      41 2109.52
      68 2095.64    81.4 2087.34   111.6 2071.22   130.2 2062.21   153.4 2046.65
   175.9 2027.52   184.8 2025.27   202.8 2027.74   220.7 2028.67   252.3 2027.53
   269.4  2028.5   294.72027.684   313.62027.582   332.1 2027.66   341.8 2029.12
   355.2 2029.53   370.1 2031.71   377.5 2034.31   422.7 2060.52   438.9 2071.34
   476.8  2093.8   515.6  2115.4   550.4 2138.96     569 2149.22   593.8 2164.45
#Mann= 3 ,-1 , 0
       0      .1       0   294.7    .045       0   313.6      .1       0
Bank Sta=294.7,313.6
XS Rating Curve= 0 ,0
Exp/Cntr=0.3,0.1

Type RM Length L Ch R = 1 ,28468   ,202.1,202.4,202.4
XS GIS Cut Line= 3
     2110528.812      195931.907     2110702.019      196171.555
     2110881.228      196369.965
#Sta/Elev= 30
       0 2126.04    32.5 2108.96    60.6 2097.43    74.5 2088.67    93.3 2080.01
   107.4 2074.91     145 2056.69   183.8 2040.77   200.6 2032.65   214.2 2024.64
   241.4 2021.99   262.2 2022.73   270.9  2024.7     279 2025.15   284.6 2023.28
   288.4 2022.58   310.5 2023.14   316.3 2024.18   332.6 2022.97   337.2 2023.94
   348.1 2031.66     357 2034.53   367.4  2040.9   398.6  2054.9   441.8 2078.53
     458 2088.29   511.1 2113.77   525.4  2122.2   533.8 2125.63   563.1 2140.56
#Mann= 3 ,-1 , 0
       0      .1       0   284.6    .045       0   310.5      .1       0
Bank Sta=284.6,310.5
XS Rating Curve= 0 ,0
Exp/Cntr=0.3,0.1

Type RM Length L Ch R = 1 ,28266   ,311.5,315.3,319.5
XS GIS Cut Line= 3
      2110380.51      196082.071     2110534.568      196270.961
     2110716.797      196496.969
#Sta/Elev= 30
       0 2099.96    17.5 2091.35    44.7 2080.46    55.6 2076.89   100.6 2064.71
   136.1 2051.64   186.9 2034.69   196.2 2030.19   212.6 2019.97   216.32018.741
   224.2 2018.12   234.72018.847   240.5 2020.37     263 2018.62   271.4 2020.73
   284.1 2021.66   298.9 2020.74   317.8 2024.91   329.2 2031.68   347.3 2039.74
   380.5 2061.54   436.5 2082.35   452.9 2092.15   461.1 2099.01   469.5 2105.05
   486.4 2112.51   501.9 2120.46   515.9 2129.82   528.5 2139.76   534.1  2143.3
#Mann= 3 ,-1 , 0
       0      .1       0   216.3    .045       0   234.7      .1       0
Bank Sta=216.3,234.7
XS Rating Curve= 0 ,0
Exp/Cntr=0.3,0.1

Type RM Length L Ch R = 1 ,27950   ,229.2,232.3,234.5
XS GIS Cut Line= 3
     2110145.479      196139.866     2110257.483      196401.155
     2110373.165      196691.755
#Sta/Elev= 30
       0 2091.48    62.9 2080.53    98.3 2072.75   119.7 2065.49   169.6 2046.34
   213.6 2034.38   238.6 2024.35   263.6 2019.39   276.62013.047   283.9 2012.79
   294.22013.218     303  2014.4   312.1 2013.39   322.7 2015.48   347.4 2017.64
   368.7 2021.24   375.7    2025   389.8 2035.42   404.1 2042.92   433.1 2056.27
   442.8 2060.16   456.9 2064.33   478.1 2073.38   497.4 2084.16   513.4 2091.68
   527.5 2100.08   541.7 2106.38   560.6 2116.06   580.8 2125.22   597.1 2130.62
#Mann= 3 ,-1 , 0
       0      .1       0   276.6    .045       0   294.2      .1       0
Bank Sta=276.6,294.2
XS Rating Curve= 0 ,0
Exp/Cntr=0.3,0.1

Type RM Length L Ch R = 1 ,27718   ,240.7,250,258.1
XS GIS Cut Line= 3
 2109979.5768037196165.061732099     2110048.874      196498.076
     2110100.234      196736.178
#Sta/Elev= 30
       0 2076.77    22.9 2070.83    46.4 2066.16     157 2048.91   174.9 2047.36
   203.9 2041.75   227.4 2034.57   247.1 2026.93   257.5 2022.04   283.1 2012.59
   307.8 2010.88   321.2 2011.87   330.72009.507   344.7 2009.22   349.6 2009.43
   352.4 2010.03   368.1  2018.9   378.2 2021.33   381.6 2022.94   388.3 2028.17
   415.9  2044.3   429.7 2054.03     442 2060.61   455.4 2069.06   468.4  2075.6
     507 2097.16   532.6  2113.2   569.5 2133.78   576.2 2140.36   583.7 2144.77
#Mann= 3 ,-1 , 0
       0      .1       0   330.7    .045       0   349.6      .1       0
Bank Sta=330.7,349.6
XS Rating Curve= 0 ,0
Exp/Cntr=0.3,0.1

Type RM Length L Ch R = 1 ,27468   ,301.9,307.2,309.9
XS GIS Cut Line= 3
 2109920.3613903 196208.92851499     2109802.902      196500.118
     2109735.456      196658.812
#Sta/Elev= 30
       0 2061.41    20.7 2055.99    50.9 2048.99     129 2032.58   203.3 2019.25
   232.4 2011.52   242.2 2010.15   252.6 2010.15   269.5 2009.21   281.2 2006.43
   290.4 2007.22   295.3 2007.04   302.92005.048     314 2004.78   321.92005.056
   323.7 2005.62   330.6 2013.23   333.1 2015.08   345.1 2018.98   348.1 2021.29
   352.2 2026.44   355.6 2029.24   387.9 2045.66     395 2049.81   402.1 2055.09
   424.3 2068.66   443.2 2081.85   466.3 2095.57   480.5 2105.58   486.4 2108.86
#Mann= 3 ,-1 , 0
       0      .1       0   302.9    .045       0   321.9      .1       0
Bank Sta=302.9,321.9
XS Rating Curve= 0 ,0
Exp/Cntr=0.3,0.1

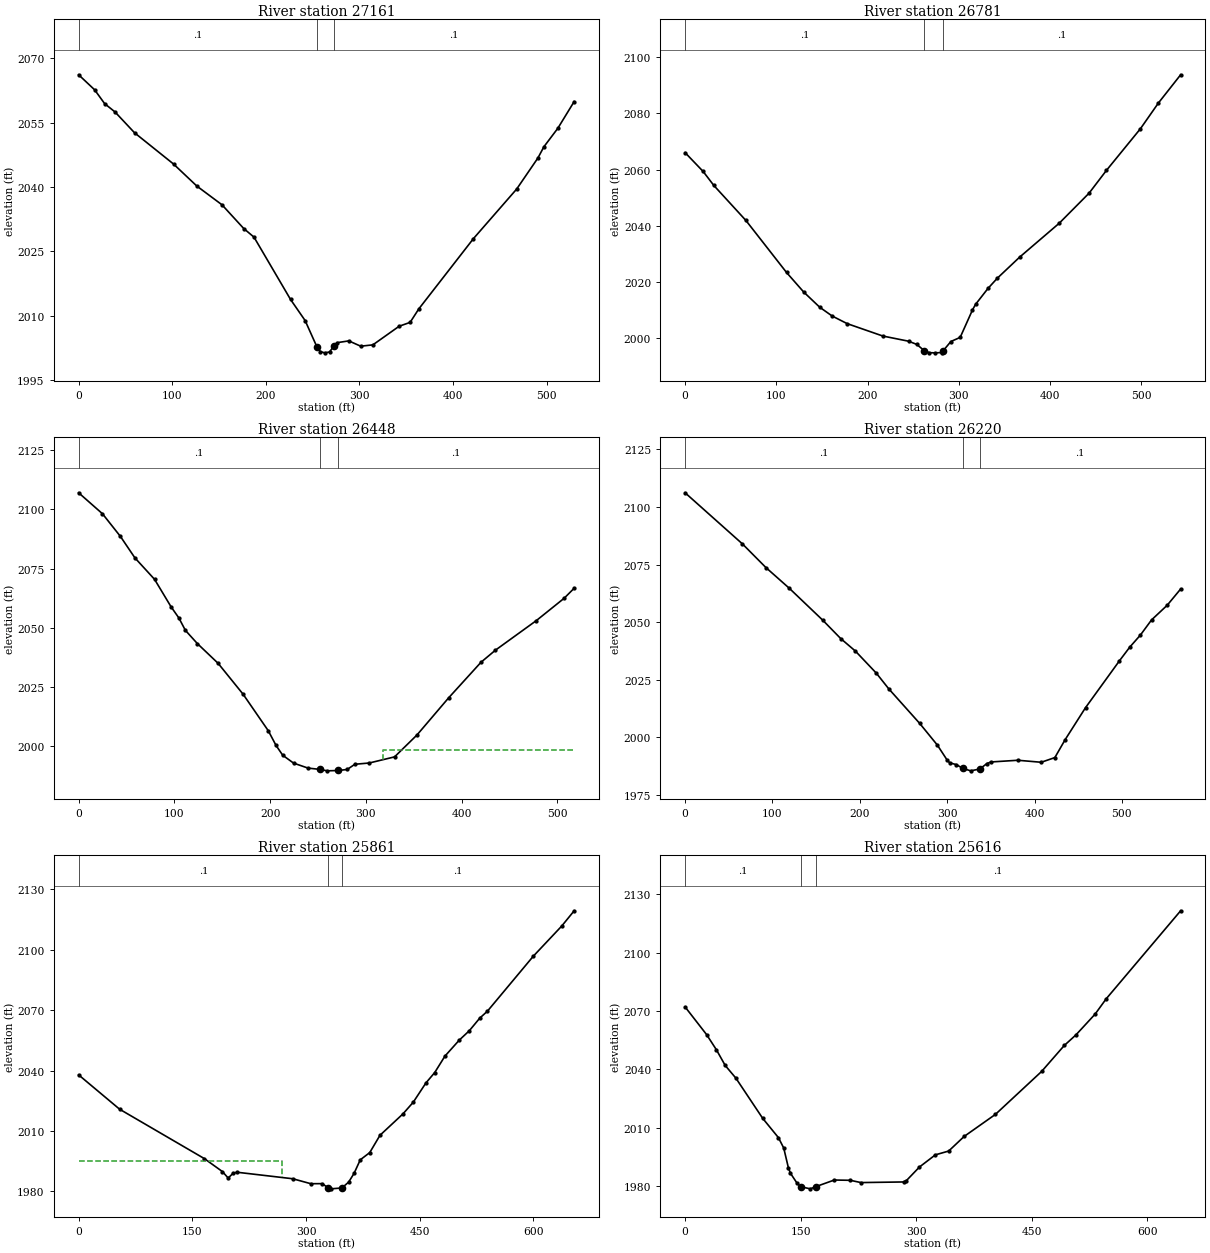
Type RM Length L Ch R = 1 ,27161   ,371.6,379.8,391
XS GIS Cut Line= 2
     2109754.637      196091.303      2109428.18      196508.178
#Sta/Elev= 30
       0 2066.19    17.1 2062.68    27.8 2059.45    38.9 2057.51    59.7 2052.66
   101.4 2045.36   126.4  2040.2   153.2 2035.84   176.4 2030.31   187.4 2028.29
   226.4 2013.76     242 2008.83   254.6 2002.69   258.3 2001.57     263 2001.29
   268.1 2001.49   272.72002.865   276.4 2003.67   288.7 2004.08   301.4 2002.84
   314.4 2003.15   342.5  2007.5   354.2  2008.4   363.5 2011.55   421.9 2027.96
   468.1 2039.53   490.7 2046.75   497.2  2049.4     512 2053.69   529.5 2059.94
#Mann= 3 ,-1 , 0
       0      .1       0   254.6    .045       0   272.7      .1       0
Bank Sta=254.6,272.7
XS Rating Curve= 0 ,0
Exp/Cntr=0.3,0.1

Type RM Length L Ch R = 1 ,26781   ,341.7,332.9,316.9
XS GIS Cut Line= 4
     2109557.245       195923.73     2109401.198      196040.272
     2109242.344      196081.938      2109144.33      196238.006
#Sta/Elev= 30
       0 2066.07    19.8 2059.36    31.5 2054.39    66.7 2041.92   111.2 2023.43
     130 2016.48   147.6 2011.06   161.2 2007.94   177.7 2005.22   216.8 2000.81
     245 1998.97   254.1 1997.82   262.41995.544   267.7 1994.88   273.7 1994.83
   281.2 1994.91   282.81995.518   291.4 1998.86   301.6 2000.33   315.1 2010.11
   318.5  2012.1   332.1 2017.76   342.3 2021.38   366.7 2028.86   410.1 2040.92
   442.9 2051.64   461.9 2059.73   499.2 2074.57     519 2083.76   543.3 2093.77
#Mann= 3 ,-1 , 0
       0      .1       0   262.4    .045       0   282.8      .1       0
Bank Sta=262.4,282.8
XS Rating Curve= 0 ,0
Exp/Cntr=0.3,0.1

Type RM Length L Ch R = 1 ,26448   ,227.6,228.1,228.6
XS GIS Cut Line= 2
     2109241.648       195644.16     2108987.543      196095.077
#Sta/Elev= 30
       0 2107.03    24.9 2098.18    43.7 2088.59    58.8 2079.56    79.3 2070.52
    96.5 2058.96   104.7 2054.22   111.5    2049     124 2043.42   145.7 2035.08
   171.8 2022.05   198.1 2006.64   206.2 2000.45   213.2  1996.3   224.5 1992.99
   239.6 1990.89   251.6 1990.36   259.7 1989.73   271.3 1989.88   280.5  1990.3
   288.5  1992.5   303.6 1993.04     330 1995.62   353.3 2004.81   386.4 2020.49
   420.3 2035.54   435.4 2040.65   478.1 2053.12     507 2062.49   517.6 2066.76
#Mann= 3 ,-1 , 0
       0      .1       0   251.6    .045       0   271.3      .1       0
#XS Ineff= 2 , 0
                          318.24         1998.59
Permanent Ineff=
       F       F
Bank Sta=251.6,271.3
XS Rating Curve= 0 ,0
Exp/Cntr=0.3,0.1

Type RM Length L Ch R = 1 ,26220   ,350.8,359,363.7
XS GIS Cut Line= 3
     2109075.946      195501.308     2108907.122      195782.138
2108777.96832395195984.035343327
#Sta/Elev= 30
       0 2106.13    65.7 2083.92    92.5 2073.69   119.3 2064.69   157.6 2050.84
   178.1 2042.89   194.9 2037.46   218.8 2027.91   233.1 2021.08   268.6 2006.04
   288.8 1996.64   300.1 1990.08     303 1988.94   310.7 1988.15     3181986.514
     327 1985.47   337.41986.282   345.4  1988.6   350.1 1989.32     381 1990.06
   407.7 1989.19   423.3 1991.22     435 1998.95   458.4 2012.88   497.3 2033.25
     509 2039.12   521.2 2044.37     534 2050.96   551.9 2057.32   567.3 2064.37
#Mann= 3 ,-1 , 0
       0      .1       0     318    .045       0   337.4      .1       0
Bank Sta=318,337.4
XS Rating Curve= 0 ,0
Exp/Cntr=0.3,0.1

Type RM Length L Ch R = 1 ,25861   ,269.9,244.6,231.3
XS GIS Cut Line= 3
      2108917.19      195387.911     2108595.208      195589.751
     2108530.714      195855.789
#Sta/Elev= 30
       0 2037.85    54.1  2020.8   165.9 1996.28   189.7 1989.85   197.3 1986.64
   203.9 1989.04     209 1989.52   282.5 1986.29   306.3 1983.83   321.3 1983.86
   329.31981.788   332.9 1981.28   347.31981.709   356.3 1984.64   363.4 1988.97
   371.6 1995.69   384.1 1999.28   397.6 2007.87     428 2018.52   441.5 2024.29
   458.3  2033.9   469.8    2039   483.3 2047.17   502.2 2055.11   515.4 2059.75
   529.2 2066.01   539.4  2069.5     600 2096.82   637.3 2111.71   653.8 2119.32
#Mann= 3 ,-1 , 0
       0      .1       0   329.3    .045       0   347.3      .1       0
#XS Ineff= 2 , 0
          267.89  1994.9
Permanent Ineff=
       F       F
Bank Sta=329.3,347.3
XS Rating Curve= 0 ,0
Exp/Cntr=0.3,0.1

Type RM Length L Ch R = 1 ,25616   ,403.5,408.4,415
XS GIS Cut Line= 3
     2108443.029      195225.973     2108549.635      195548.084
     2108486.336      195845.686
#Sta/Elev= 30
       0 2072.05    27.9 2057.83    40.6 2050.06    52.1 2041.94    65.9 2035.46
   100.8 2014.75   121.2 2004.85   128.1 1999.49   134.1 1989.43   136.7 1986.61
   145.4 1981.41   150.11979.595   162.7 1978.51   169.6 1979.62   193.8 1983.04
   214.6  1982.9   228.4 1981.73   283.7 1982.05   287.3 1982.69   304.4 1989.74
   325.1    1996   342.3 1997.93   362.4 2005.44   403.1 2016.81   463.1 2038.89
   492.5 2052.23   507.6 2057.65   532.5 2068.34   546.9 2076.21   643.6 2121.48
#Mann= 3 ,-1 , 0
       0      .1       0   150.1    .045       0   169.6      .1       0
Bank Sta=150.1,169.6
XS Rating Curve= 0 ,0
Exp/Cntr=0.3,0.1

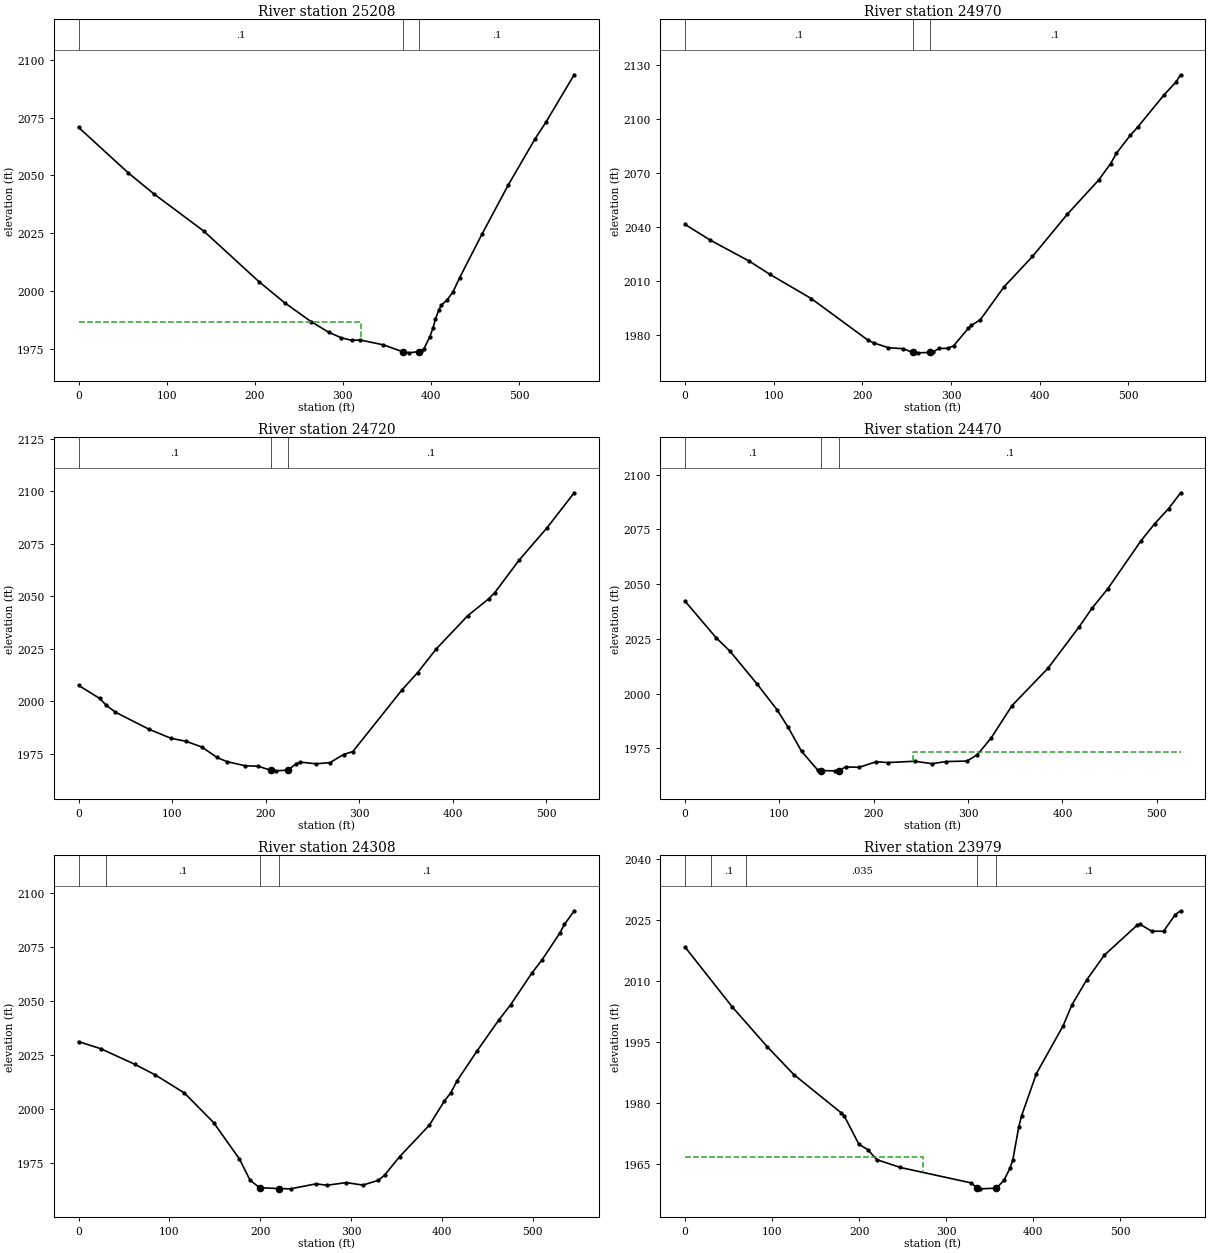
Type RM Length L Ch R = 1 ,25208   ,236.2,238.2,239.3
XS GIS Cut Line= 2
      2108237.78      195265.089     2108192.547      195825.978
#Sta/Elev= 30
       0 2070.73    56.5 2051.02    86.1  2041.8   142.1  2025.9   204.6 2004.08
   234.2 1994.81   263.8 1986.78   283.8 1982.18   298.1 1979.75   309.9 1978.67
   319.8 1978.78   346.1 1976.68   367.91973.719   375.7 1973.23     3861973.805
   388.9 1973.92   392.2 1975.08   398.8 1980.19   402.2 1983.79   405.2 1987.85
   409.1 1991.85     412 1993.91   418.5 1996.15   425.1 1999.58   432.6  2005.7
     458 2024.55   487.7 2045.73   517.9 2065.55   530.9 2073.19   562.7 2093.51
#Mann= 3 ,-1 , 0
       0      .1       0   367.9    .045       0     386      .1       0
#XS Ineff= 2 , 0
          320.08 1986.72
Permanent Ineff=
       F       F
Bank Sta=367.9,386
XS Rating Curve= 0 ,0
Exp/Cntr=0.3,0.1

Type RM Length L Ch R = 1 ,24970   ,253.6,250,245
XS GIS Cut Line= 3
     2108030.574      195319.676      2107978.28      195580.802
2107923.57801524195868.241020317
#Sta/Elev= 30
       0 2041.36    28.5 2032.61      72 2021.09    95.4 2013.73   142.3 2000.23
   205.8 1977.29   212.5 1975.65   229.3 1972.95     246  1972.4   256.51970.349
   262.7  1970.1   276.1 1970.35   280.1 1970.66   286.1 1972.54   296.1  1972.6
   302.8 1973.98   319.5 1983.76   322.8 1985.31   332.9 1988.42   359.6 2006.66
   391.8 2023.58     431 2046.96   466.5 2066.02   479.8 2075.02   486.5 2080.84
     502 2090.77   510.3 2095.26   539.9 2113.08   553.3 2120.21   558.9 2124.41
#Mann= 3 ,-1 , 0
       0      .1       0   256.5    .045       0   276.1      .1       0
Bank Sta=256.5,276.1
XS Rating Curve= 0 ,0
Exp/Cntr=0.3,0.1

Type RM Length L Ch R = 1 ,24720   ,253.6,249.7,243.2
XS GIS Cut Line= 3
2107715.62473095 195344.91524873     2107739.326      195555.354
     2107768.799      195871.851
#Sta/Elev= 30
       0 2007.64    22.5 2001.44    29.1 1998.37      39 1994.97    75.4 1986.75
    98.5 1982.52     115 1981.03   131.5 1978.36     148 1973.37   158.3 1971.41
   177.7 1969.45   191.8  1969.2   205.1 1967.33     211 1967.01   223.9 1967.37
   232.2 1970.32   237.1 1971.15   253.6 1970.36   268.6 1970.91   283.1 1974.78
   293.1 1976.19   345.8 2005.63   362.3 2013.72   382.1 2024.93   415.9  2040.8
   438.1 2048.75   444.7 2051.73     471 2067.34   500.7 2082.63   529.6 2099.24
#Mann= 3 ,-1 , 0
       0      .1       0   205.1    .045       0   223.9      .1       0
Bank Sta=205.1,223.9
XS Rating Curve= 0 ,0
Exp/Cntr=0.3,0.1

Type RM Length L Ch R = 1 ,24470   ,164.3,162.5,159.7
XS GIS Cut Line= 3
2107436.59274111 195438.82750254     2107495.962       195574.72
     2107668.134      195910.085
#Sta/Elev= 30
       0 2042.19    32.9  2025.5    47.3 2019.51    76.1 2004.51    97.4 1992.69
   109.2 1984.66   123.4  1973.7   140.4 1965.19   143.6 1964.86   158.6 1964.75
   162.9 1964.83   170.2 1966.55   184.4 1966.36   202.8 1968.93   214.6 1968.52
   243.4 1969.13   261.8 1968.02   276.6 1968.99   298.7 1969.21   309.8 1972.12
   324.5 1979.78   346.6 1994.56   384.7  2011.6   417.8 2030.55   431.5 2039.07
   448.1  2047.9   483.1 2069.69   497.8 2077.57   512.6  2084.5   525.3  2091.7
#Mann= 3 ,-1 , 0
       0      .1       0   143.6    .045       0   162.9      .1       0
#XS Ineff= 2 , 0
                          242.11         1973.53
Permanent Ineff=
       F       F
Bank Sta=143.6,162.9
XS Rating Curve= 0 ,0
Exp/Cntr=0.3,0.1

Type RM Length L Ch R = 1 ,24308   ,322,328.9,333.6
XS GIS Cut Line= 2
      2107252.96      195508.527     2107569.257       195953.47
#Sta/Elev= 30
       0 2031.16    24.1 2027.95    61.8 2020.72    84.4  2015.8   116.6 2007.42
   148.8 1993.72   177.2 1976.91   188.8 1967.18   199.4 1963.66   220.61963.277
   233.5 1963.15   261.5 1965.47   273.6  1964.8   294.7 1966.04   313.1 1964.89
     330 1967.06     337 1969.45   353.5 1977.97   386.3 1992.55   402.9  2003.7
     410 2007.58     417  2013.1   438.6 2026.68   462.7 2041.08   475.9  2048.2
     499  2062.7   510.5 2068.97     530 2081.27   535.2 2085.33   545.9 2091.64
#Mann= 4 ,-1 , 0
       0    .035       0      30      .1       0   199.4    .045       0
   220.6      .1       0
Bank Sta=199.4,220.6
XS Rating Curve= 0 ,0
Exp/Cntr=0.3,0.1

Type RM Length L Ch R = 1 ,23979   ,304.2,313.7,322.3
XS GIS Cut Line= 2
     2107054.594      195551.509      2107201.53      196101.473
#Sta/Elev= 30
       0 2018.26    53.8 2003.65    94.6 1993.71   124.9 1986.91   179.5 1977.47
   182.9 1976.69   199.7 1969.76   210.1 1968.41   220.2 1965.98   247.4 1964.05
   328.9 1960.25   335.6 1958.94   339.1  1958.8   357.71958.965   366.3  1960.9
   373.1 1963.81   376.5 1965.91   383.3    1974   386.6 1976.79   403.6 1987.16
   434.2 1998.87   444.4 2004.06   461.4 2010.21   481.7 2016.29   519.1 2023.61
   522.5  2023.9   536.1 2022.17   549.7 2022.17   563.2 2026.28   569.3  2027.2
#Mann= 5 ,-1 , 0
       0    .035       0      30      .1       0      70    .035       0
   335.6    .045       0   357.7      .1       0
#XS Ineff= 2 , 0
          273.19 1966.66
Permanent Ineff=
       F       F
Bank Sta=335.6,357.7
XS Rating Curve= 0 ,0
Exp/Cntr=0.3,0.1