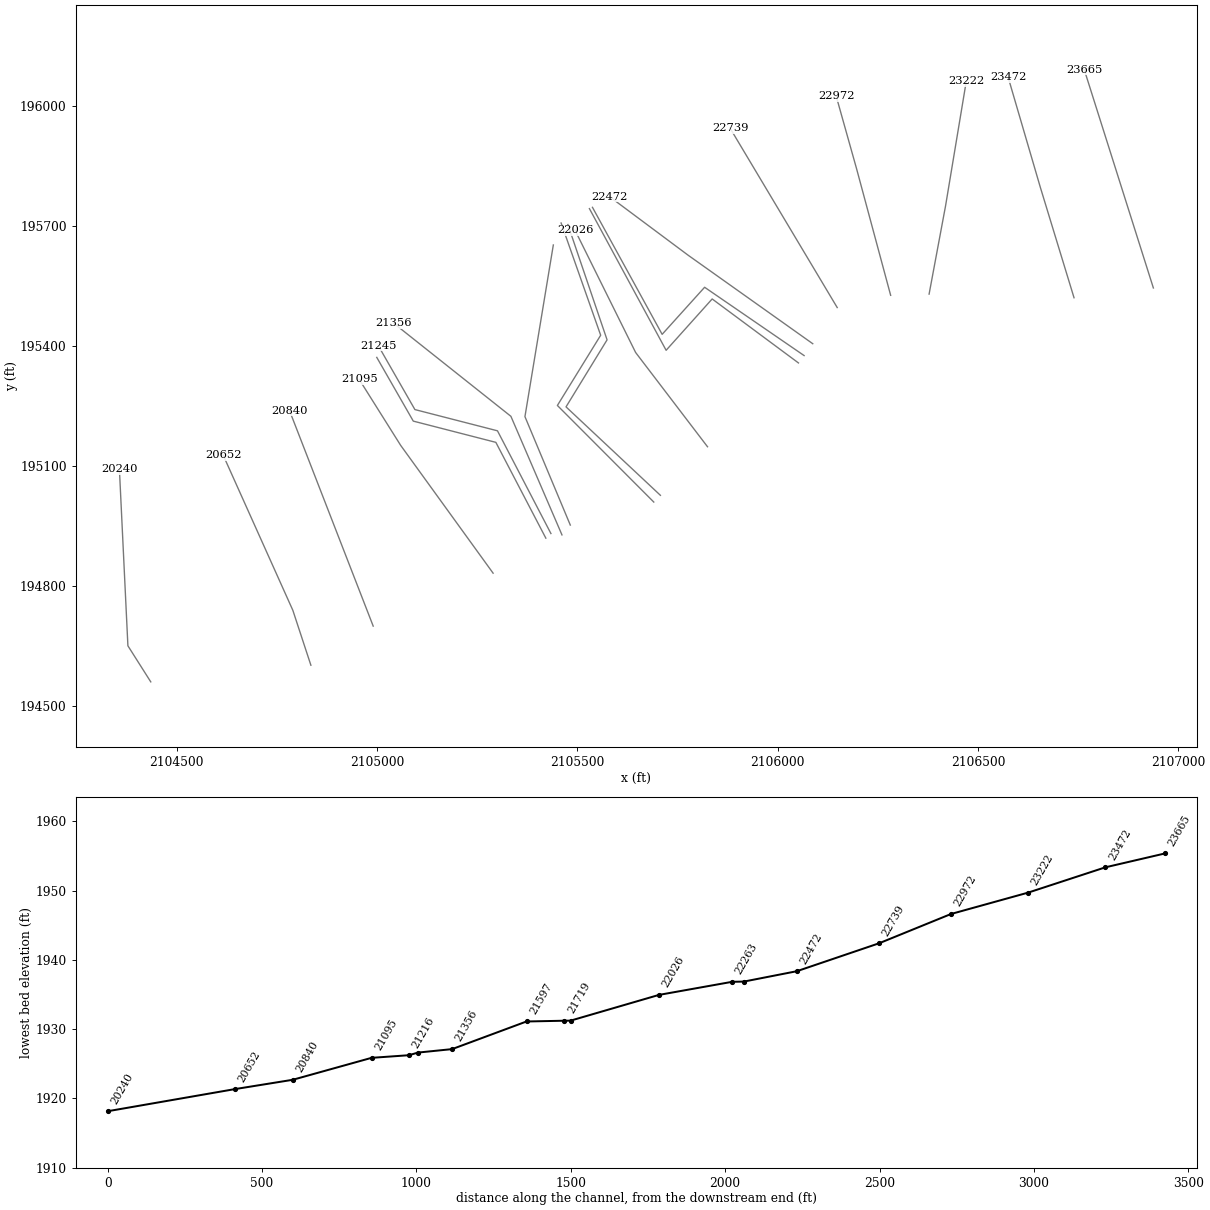
HEC-RAS study TRKYCK.prj: TRKYCK

--- TRKYCK.g01 (geometry) --- (continued)

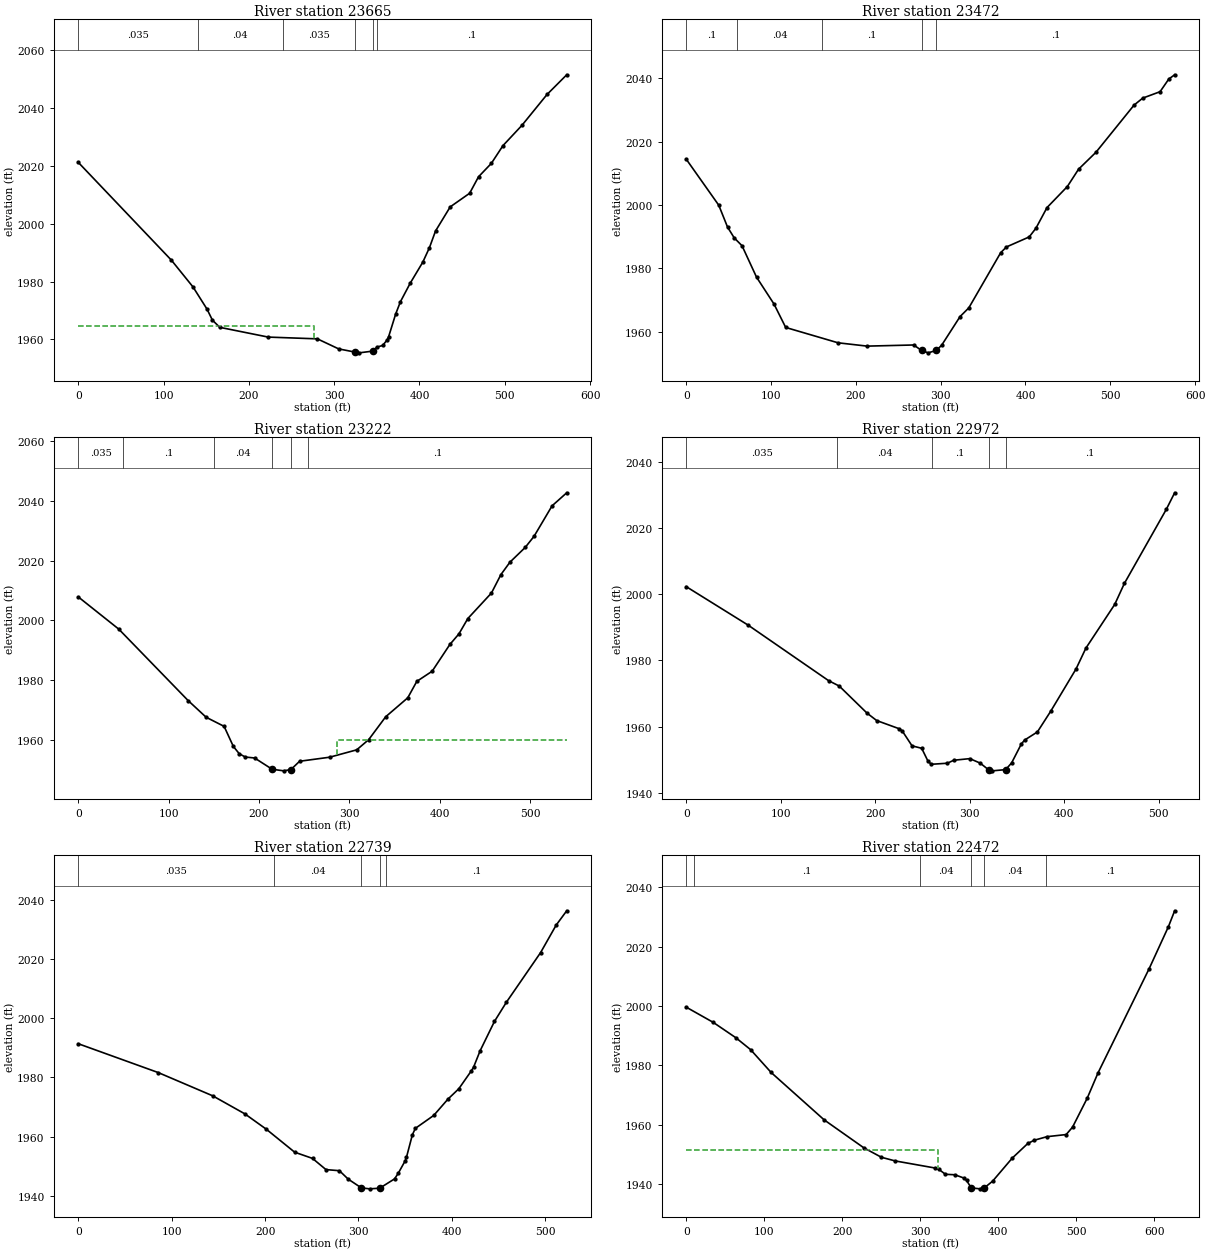
Type RM Length L Ch R = 1 ,23665   ,193.8,193.6,193.6
XS GIS Cut Line= 2
     2106938.057      195545.375     2106765.634        196091.4
#Sta/Elev= 30
       0 2021.17   109.2 1987.37   134.5 1978.13   150.9 1970.48   157.3 1966.64
   165.9 1964.18   222.7 1960.81   280.3  1960.2   305.3 1956.73   323.9 1955.66
   329.3 1955.37   345.6 1955.98     350 1957.34   356.9 1957.93   362.1 1959.86
   363.8 1960.93   372.1  1968.8   377.7 1973.06   389.2 1979.47   403.9 1986.71
   411.7 1991.73   418.8 1997.46     436 2005.79   458.8  2010.5   469.2 2016.19
   484.2 2020.81   497.9 2026.97     520 2033.93   549.5 2044.62   572.6 2051.43
#Mann= 6 ,-1 , 0
       0    .035       0     140     .04       0     240    .035       0
   323.9    .045       0   345.6    .035       0     350      .1       0
#XS Ineff= 2 , 0
          276.65  1964.6
Permanent Ineff=
       F       F
Bank Sta=323.9,345.6
XS Rating Curve= 0 ,0
Exp/Cntr=0.3,0.1

Type RM Length L Ch R = 1 ,23472   ,256.8,250,243
XS GIS Cut Line= 3
2106739.96696952195520.878730953     2106655.977      195796.825
      2106575.48      196072.731
#Sta/Elev= 30
       0 2014.48    38.4 1999.94    48.7 1993.06    56.6 1989.64    65.8 1987.16
    82.9 1977.25   103.5 1968.77   117.3 1961.37     179 1956.53   213.3 1955.48
   268.2 1955.84   277.51954.113   285.3 1953.36     2951954.134   301.2 1955.77
   322.9 1964.81   333.2 1967.55   370.8 1984.97   377.6 1986.78   404.4 1989.94
   412.3 1992.67   425.4  1999.2   449.4 2005.85   462.6 2011.31   483.1 2016.65
     528 2031.53   538.2 2033.74   558.7 2035.77     569 2039.77   575.9 2041.11
#Mann= 5 ,-1 , 0
       0      .1       0      60     .04       0     160      .1       0
   277.5    .045       0     295      .1       0
Bank Sta=277.5,295
XS Rating Curve= 0 ,0
Exp/Cntr=0.3,0.1

Type RM Length L Ch R = 1 ,23222   ,244.2,250,255.7
XS GIS Cut Line= 3
     2106378.101      195530.009     2106419.184      195750.684
     2106470.903      196062.463
#Sta/Elev= 30
       0 2007.88    44.8 1997.11   121.5 1973.23   141.5 1967.63   161.4 1964.58
   171.6 1957.87   178.2 1955.41   184.9 1954.32   195.1 1954.01   214.51950.245
   227.3 1949.71   235.3 1950.14   244.9 1952.91   278.2 1954.27   308.1 1956.73
   321.4 1960.16   340.2  1967.8   364.6 1974.14   374.6 1979.63   391.6 1983.03
   411.2 1991.98   421.2 1995.51   431.1 2000.66   457.2 2009.18   467.7 2015.36
   477.7 2019.51   494.5 2024.41   504.3 2028.13   524.3 2038.35   540.5 2042.71
#Mann= 6 ,-1 , 0
       0    .035       0      50      .1       0     150     .04       0
   214.5    .045       0   235.3     .04       0  254.47      .1       0
#XS Ineff= 2 , 0
                          286.79         1959.94
Permanent Ineff=
       F       F
Bank Sta=214.5,235.3
XS Rating Curve= 0 ,0
Exp/Cntr=0.3,0.1

Type RM Length L Ch R = 1 ,22972   ,226.8,232.4,234.4
XS GIS Cut Line= 3
2106282.12789443195527.019256857     2106197.067      195843.745
     2106146.173      196025.454
#Sta/Elev= 30
       0 2002.27    65.6 1990.62   150.6 1973.87   161.9 1972.23   191.3 1964.05
   201.5 1961.81   225.4 1959.33   228.7  1958.6   238.9 1954.17   249.1 1953.43
   255.9 1949.46   259.3  1948.6   276.3 1948.92     283 1949.82     300 1950.31
     311 1948.95   319.91946.927   323.8 1946.62   337.91946.985   344.2    1949
   354.5 1954.73   357.9  1955.9   371.5 1958.37   385.6 1964.63   412.4 1977.41
   422.8 1983.69   453.3 1996.89   463.5 2003.23   507.8 2025.58   516.7 2030.62
#Mann= 5 ,-1 , 0
       0    .035       0     160     .04       0     260      .1       0
   319.9    .045       0   337.9      .1       0
Bank Sta=319.9,337.9
XS Rating Curve= 0 ,0
Exp/Cntr=0.3,0.1

Type RM Length L Ch R = 1 ,22739   ,260.1,266.8,270.7
XS GIS Cut Line= 2
      2106148.72      195496.318     2105881.083      195945.648
#Sta/Elev= 30
       0 1991.36    85.7 1981.62   143.9 1973.79   178.3 1967.71   201.2 1962.55
   231.7 1954.76   250.8 1952.67   265.2 1948.89   279.6 1948.52     289 1945.68
   303.11942.724   311.9  1942.4   322.7 1942.61   338.6 1945.75   342.5 1947.59
   350.1  1951.9   351.4 1953.03   357.7 1960.61   360.9  1962.8   380.6 1967.17
   395.9  1972.7   407.4 1976.15   420.8 1982.18   423.2  1983.4   430.3 1989.01
   445.6 1998.88   458.4 2005.36     495  2022.1   511.7 2031.39     523 2036.22
#Mann= 5 ,-1 , 0
       0    .035       0     210     .04       0   303.1    .045       0
   322.7     .04       0     330      .1       0
Bank Sta=303.1,322.7
XS Rating Curve= 0 ,0
Exp/Cntr=0.3,0.1

Type RM Length L Ch R = 1 ,22472   ,146.3,171.8,190.3
XS GIS Cut Line= 3
     2106087.605      195405.867     2105776.667      195627.228
     2105580.847       195773.59
#Sta/Elev= 30
       0 1999.58    34.7 1994.44    63.6 1989.28    82.6 1985.25   108.9 1977.56
   176.8 1961.61   227.6  1952.2   250.3 1948.99   267.8 1947.77   319.4 1945.36
   323.9 1944.93   332.3 1943.26   344.4  1943.1   356.4 1941.96   359.4  1941.2
   365.41938.682   376.6 1938.36   381.7 1938.58   392.9 1940.97     418 1948.72
   437.9 1953.64   446.2 1954.74   462.6 1955.94   487.1 1956.65   495.3 1959.15
   514.1  1968.9     528 1977.45   593.6  2012.6   618.2 2026.69   626.2 2032.05
#Mann= 6 ,-1 , 0
       0    .035       0      10      .1       0     300     .04       0
   365.4    .045       0   381.7     .04       0  461.68      .1       0
#XS Ineff= 2 , 0
          323.13 1951.34
Permanent Ineff=
       F       F
Bank Sta=365.4,381.7
XS Rating Curve= 0 ,0
Exp/Cntr=0.5,0.3

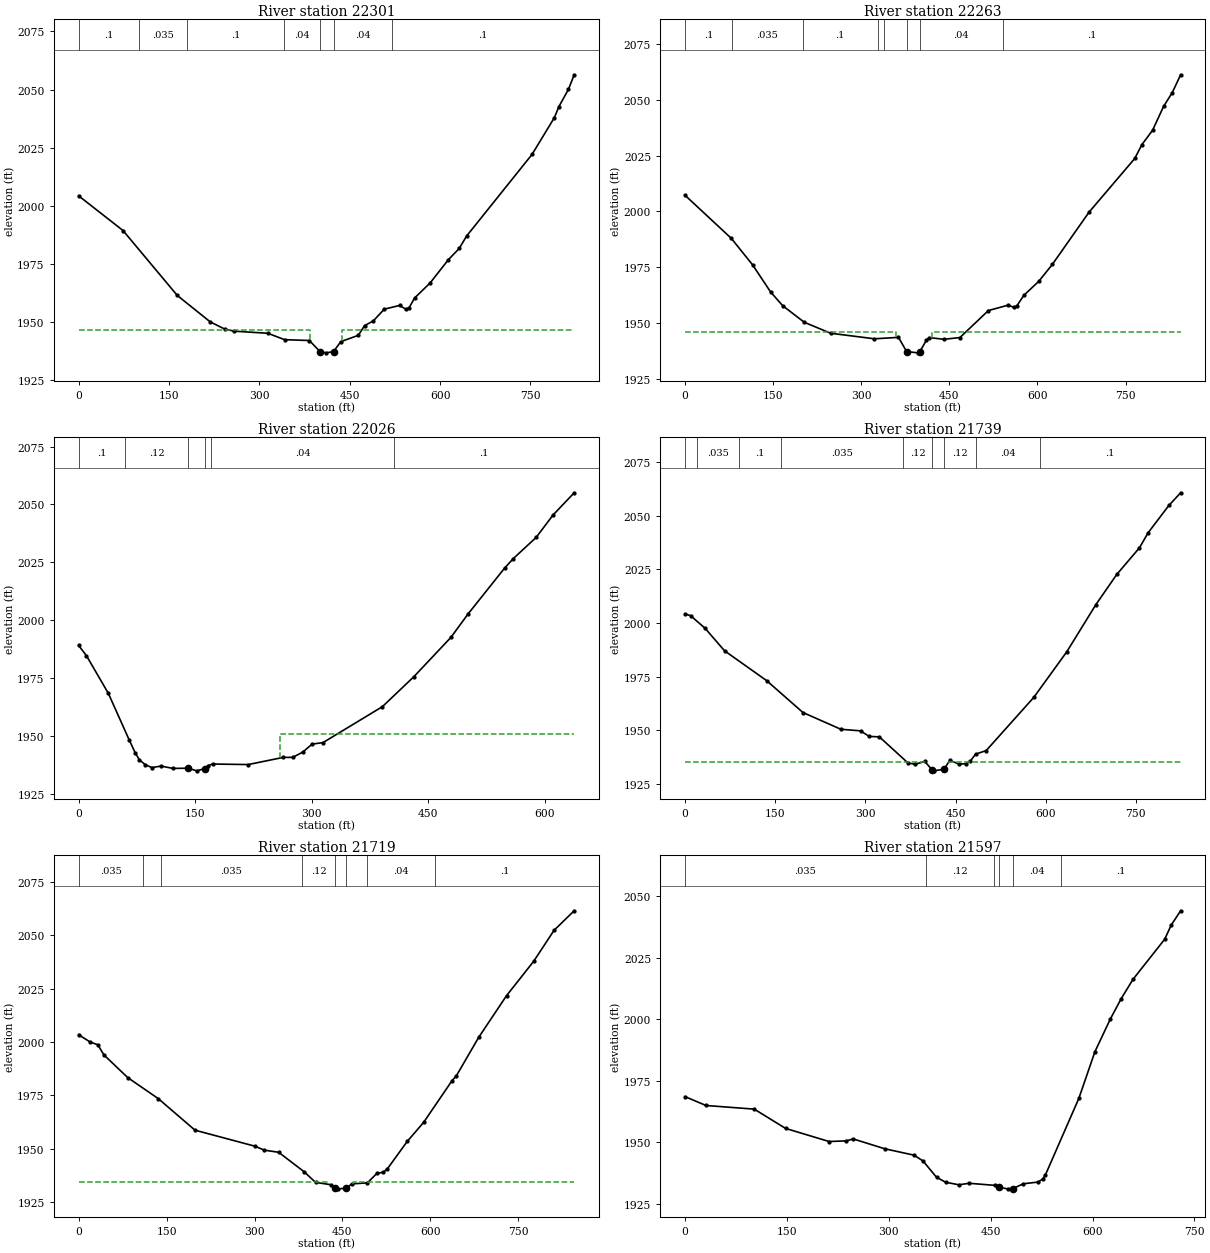
Type RM Length L Ch R = 1 ,22301   ,38.7,37.4,38.7
XS GIS Cut Line= 4
     2106066.059       195376.142105817.64011903195547.144220856
2105711.59377914195429.318441712      2105537.63      195747.233
#Sta/Elev= 30
       0 2004.36    73.7 1989.43   163.8 1961.51   218.8  1950.1   242.7 1947.06
   257.7 1946.18     314 1945.27   341.9 1942.52     383 1942.16   400.8 1937.36
   410.9 1936.86   423.1  1937.4   435.1 1941.67   464.2 1944.38   474.6 1948.55
   489.1 1950.58   507.2 1955.61   532.6 1957.24   542.8 1955.67   548.3 1956.17
   557.7 1960.45   583.4  1966.9   613.8 1976.93   631.7 1981.74   643.9 1987.05
   752.6 2022.17   789.6 2037.96   797.1 2042.69     813 2050.13   822.5 2056.39
#Mann= 7 ,-1 , 0
       0      .1       0     100    .035       0     180      .1       0
  341.59     .04       0   400.8    .045       0   423.1     .04       0
  520.11      .1       0
#XS Ineff= 2 , 0
           383.9 1946.49  436.53         1946.49
Permanent Ineff=
       F       F
Bank Sta=400.8,423.1
XS Rating Curve= 0 ,0
Exp/Cntr=0.5,0.3

Type RM Length L Ch R = 1 ,22263   ,261.7,237.2,206.6
XS GIS Cut Line= 4
     2106051.953      195357.6942105836.48758419195517.883389901
2105721.52803886195389.373974094     2105530.035      195743.978
#Sta/Elev= 30
       0  2007.2    78.7 1987.98   115.1 1976.09   145.7 1964.01   166.1 1957.91
     203 1950.48   247.9 1945.58   322.4 1943.11   363.4 1943.74   377.21937.412
   396.3 1936.83   399.51937.267     411 1942.46   415.9 1943.64   440.9 1942.88
     468 1943.66   516.5 1955.72   550.1 1958.14     560 1957.15   564.7 1957.73
     577 1962.55   602.3 1968.78   625.4 1976.33     688 1999.71   765.8 2023.68
   777.9 2029.86   796.2 2036.31   814.8  2046.9   829.7 2053.14   843.9 2061.07
#Mann= 8 ,-1 , 0
       0      .1       0      80    .035       0     200      .1       0
  328.49    .035       0  338.49     .04       0   377.2    .045       0
   399.5     .04       0  540.91      .1       0
#XS Ineff= 2 , 0
          358.89 1946.26  420.68          1946.1
Permanent Ineff=
       F       F
Bank Sta=377.2,399.5
XS Rating Curve= 0 ,0
Exp/Cntr=0.5,0.3

Type RM Length L Ch R = 1 ,22026   ,302.9,286.6,266.2
XS GIS Cut Line= 3
2105824.87992998195147.9245957052105645.39903158195383.855131501
2105493.97824771195690.163839572
#Sta/Elev= 30
       0 1989.09    10.1 1984.66    38.2 1968.44    65.4 1948.08    72.8 1942.76
    78.2 1939.68      86 1937.56    94.3 1936.35     106 1936.99   121.5 1935.99
   141.41936.075     152 1934.94   162.11935.871   166.9 1937.24   172.6 1937.88
   218.4 1937.65   263.3 1940.74   275.7 1940.77   288.7 1943.04   300.6 1946.49
   314.6 1947.12   391.2 1962.67   431.7 1975.61   479.5 1992.62   501.2 2002.59
   548.8 2022.61   559.8 2026.63   589.1 2035.74     611 2045.46   638.1 2055.03
#Mann= 6 ,-1 , 0
       0      .1       0      60     .12       0   141.4    .045       0
   162.1     .12       0     170     .04       0  406.44      .1       0
#XS Ineff= 2 , 0
                          259.69         1951.04
Permanent Ineff=
       F       F
Bank Sta=141.4,162.1
XS Rating Curve= 0 ,0
Exp/Cntr=0.5,0.3

Type RM Length L Ch R = 1 ,21739   ,20,19.9,19.9
XS GIS Cut Line= 4
2105707.25450695195026.3683399422105471.63482431195247.746429659
2105574.09860251195415.5161267852105476.22786268195704.131589137
#Sta/Elev= 30
       0 2004.23     9.2 2003.42    33.2 1997.58    65.6  1987.1   135.8 1973.18
   196.1 1958.36   259.2 1950.57   291.9 1949.83   306.3 1947.24   323.3 1947.03
   371.1 1934.84   382.7 1934.29   398.9 1935.59   411.11931.651   413.4 1931.22
   430.9 1931.96   440.3 1936.06   455.7  1934.4   467.2 1934.48   474.9 1935.87
   483.3 1938.96   501.1 1940.67   580.2 1965.39   635.3 1986.69   683.6  2008.6
   718.4 2022.65   756.1 2035.03   770.4 2041.97     805 2054.72   824.6 2060.62
#Mann= 9 ,-1 , 0
       0      .1       0      20    .035       0      90      .1       0
     160    .035       0   363.3     .12       0   411.1    .045       0
   430.9     .12       0   483.3     .04       0  589.89      .1       0
#XS Ineff= 2 , 0
          400.64 1935.47  438.16         1935.22
Permanent Ineff=
       F       F
Bank Sta=411.1,430.9
XS Rating Curve= 0 ,0
Exp/Cntr(USF)=0,0
Exp/Cntr=0.5,0.3

Type RM Length L Ch R = 1 ,21719   ,116.2,122.6,128
XS GIS Cut Line= 4
2105690.70182575195009.5218699572105450.06082575195251.276869957
2105558.13382575195427.0578699572105459.36982575195708.009869957
#Sta/Elev= 30
       0 2003.44    19.9 1999.97    32.7 1998.74    43.1 1993.99    83.6 1983.38
   135.9 1973.48   198.5  1958.7   300.6  1951.2   316.9 1949.32   341.1 1948.36
   384.9 1939.17   404.1 1934.23   429.8 1933.17   437.11931.648   441.7 1931.21
   456.81931.493   465.8 1933.52   492.7 1934.02   508.5  1938.4   519.7    1939
   526.6 1940.57   560.6 1953.46   588.5 1962.35   637.1 1981.97   644.1 1984.06
   682.3 2002.15   729.9 2021.73   776.3 2037.88     811 2052.37   845.3 2061.52
#Mann= 8 ,-1 , 0
       0    .035       0     110      .1       0     140    .035       0
  381.11     .12       0   437.1    .045       0   456.8     .12       0
  491.11     .04       0  607.45      .1       0
#XS Ineff= 2 , 0
          424.55 1934.36  467.77         1934.36
Permanent Ineff=
       F       F
Bank Sta=437.1,456.8
XS Rating Curve= 0 ,0
Exp/Cntr=0.5,0.3

Type RM Length L Ch R = 1 ,21597   ,222.8,241,254.2
XS GIS Cut Line= 3
     2105482.292      194951.8782105369.05464676195223.312904872
2105439.92061843195653.015568571
#Sta/Elev= 30
       0 1968.54    30.7 1964.95   101.8 1963.47     148 1955.63     212 1950.32
   237.4 1950.57   247.5 1951.37   294.1 1947.36     337 1944.78   350.3 1942.42
   370.2 1935.79   383.5 1933.79   403.1 1932.74     418 1933.36   456.7  1932.5
   461.71931.749   474.8  1931.1   482.41931.178   497.9 1933.15   519.9 1933.86
   526.5 1935.09   530.6 1936.82   579.7 1967.82   603.5 1986.86   626.1 2000.07
     642  2008.3   659.5 2016.19   706.1 2032.46     716 2038.36   729.6 2044.02
#Mann= 6 ,-1 , 0
       0    .035       0  354.11     .12       0  454.11     .04       0
   461.7    .045       0   482.4     .04       0  554.11      .1       0
Bank Sta=461.7,482.4
XS Rating Curve= 0 ,0
Exp/Cntr=0.3,0.1

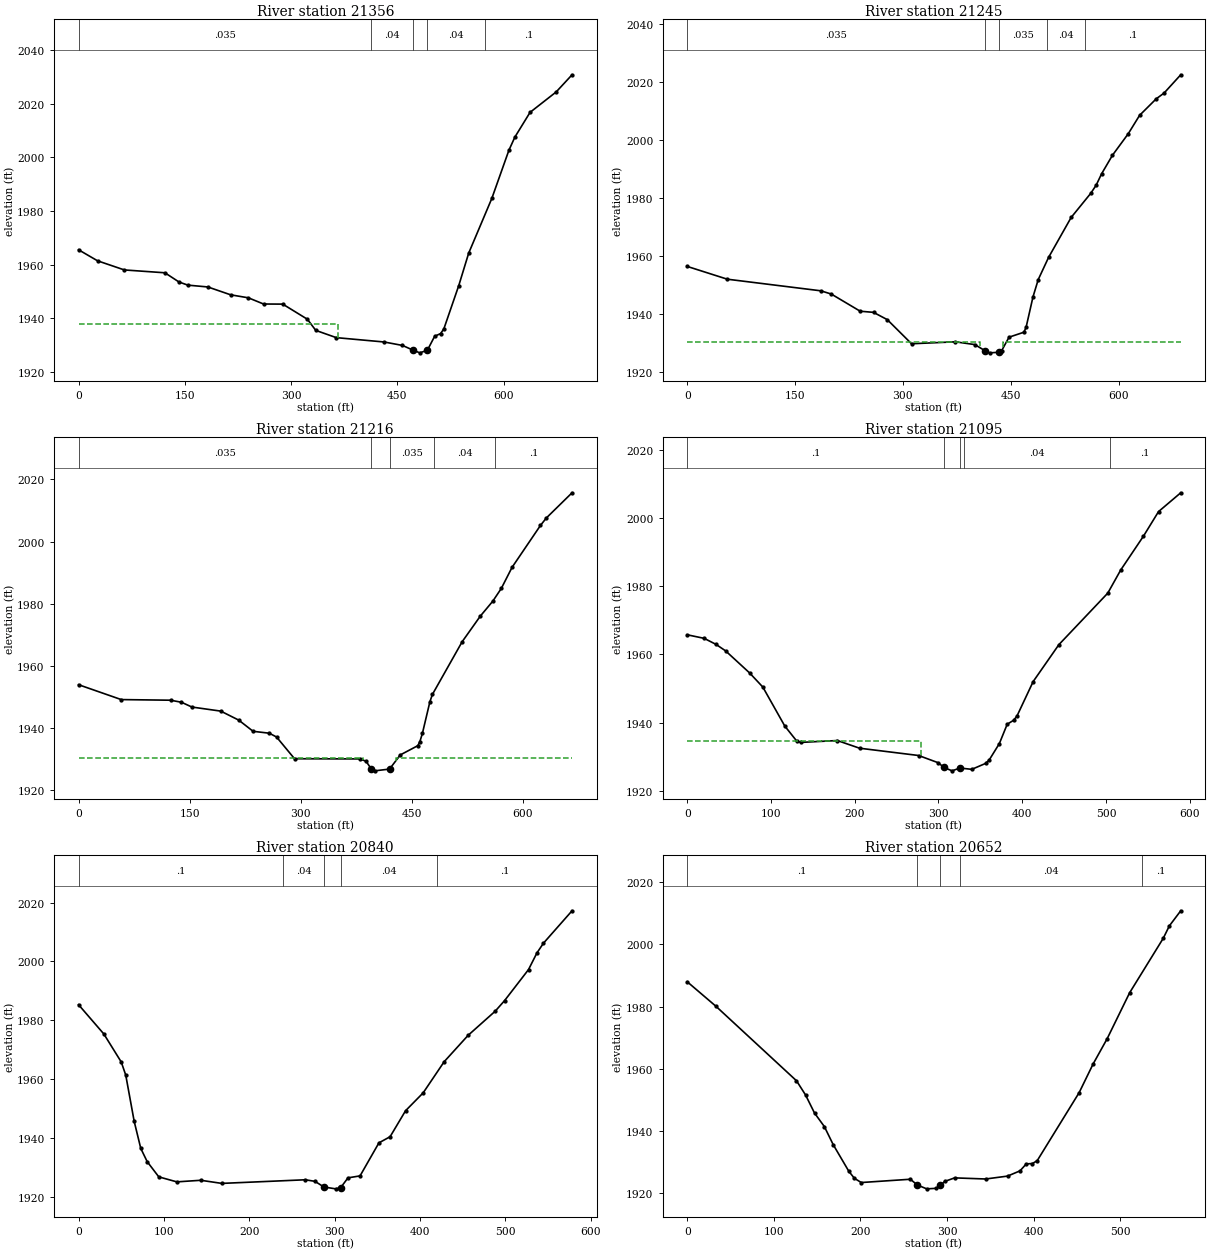
Type RM Length L Ch R = 1 ,21356   ,103.2,110.6,115.8
XS GIS Cut Line= 3
2105461.48274735194927.2825173852105334.00581894195224.108357995
2105041.83242097195456.730490135
#Sta/Elev= 30
       0 1965.57    26.9 1961.44    64.7 1958.04   121.9 1956.98   141.8 1953.54
   154.3 1952.37   182.5 1951.69   214.7 1948.76   239.7 1947.64   261.1 1945.33
   288.2 1945.29     323 1939.64   334.8 1935.49   363.8 1932.78   431.3 1931.16
   457.2 1929.87   472.41928.076   481.6 1927.11   492.31928.077   502.6  1933.3
     511  1934.3   515.6 1936.08   536.6  1952.2   550.6  1964.3   583.3 1984.75
   607.4 2002.72   615.8 2007.61   637.2 2016.83   674.1 2024.46   696.5 2030.86
#Mann= 5 ,-1 , 0
       0    .035       0  413.04     .04       0   472.4    .045       0
   492.3     .04       0  573.04      .1       0
#XS Ineff= 2 , 0
          366.27 1937.88
Permanent Ineff=
       F       F
Bank Sta=472.4,492.3
XS Rating Curve= 0 ,0
Exp/Cntr(USF)=0,0
Exp/Cntr=0.5,0.3

Type RM Length L Ch R = 1 ,21245   ,29,29.2,29
XS GIS Cut Line= 4
2105433.93011412194930.6698908012105300.46611412195187.831890801
2105094.30311412195240.9998908012105003.15711412195400.504890801
#Sta/Elev= 30
       0 1956.41    55.8    1952   185.8    1948   200.4 1946.88   240.6 1940.96
   259.1 1940.57   278.3 1938.05     312 1929.74     373 1930.41   400.1 1929.45
   414.4  1927.3   420.5 1926.61   433.91926.806   437.4  1927.4   447.6 1932.01
   468.3 1933.72   471.3  1935.4   480.9 1945.89   488.2 1951.87   502.6 1959.52
     534  1973.3   561.2  1981.6   568.8 1984.43   576.3 1988.33   591.4 1994.73
   613.4 2002.16   629.2 2008.51   652.3  2014.2   663.2 2016.18   686.4 2022.49
#Mann= 5 ,-1 , 0
       0    .035       0   414.4    .045       0   433.9    .035       0
  499.73     .04       0  552.64      .1       0
#XS Ineff= 2 , 0
          407.71 1930.31  439.75         1930.38
Permanent Ineff=
       F       F
Bank Sta=414.4,433.9
XS Rating Curve= 0 ,0
Exp/Cntr=0.5,0.3

Type RM Length L Ch R = 1 ,21216   ,131.7,121.1,111.4
XS GIS Cut Line= 4
2105421.21222781194919.1377124422105296.42922781195158.937712442
2105090.26622781195212.1057124422104999.12022781195371.611712442
#Sta/Elev= 30
       0 1953.95    57.7 1949.16   124.3 1948.96   139.1  1948.3   153.2 1946.76
   192.2 1945.45   216.5 1942.55   235.9 1938.95   257.8 1938.34   267.6 1937.11
   291.9 1930.12   379.9 1930.07   388.5 1929.32   395.3 1926.94   400.3 1926.23
   420.3  1926.8   434.7 1931.34   458.5 1934.33   461.3 1935.66   464.7 1938.31
   474.8 1948.47   478.2 1950.82   518.4 1967.78   542.9 1976.01   559.8 1980.83
   571.3 1984.93   585.8 1991.71   624.2  2005.2   632.1 2007.59   666.9 2015.71
#Mann= 5 ,-1 , 0
       0    .035       0   395.3    .045       0   420.3    .035       0
  480.32     .04       0  563.23      .1       0
#XS Ineff= 2 , 0
          384.71 1930.48  428.39         1930.37
Permanent Ineff=
       F       F
Bank Sta=395.3,420.3
XS Rating Curve= 0 ,0
Exp/Cntr=0.5,0.3

Type RM Length L Ch R = 1 ,21095   ,258.7,255.3,251.6
XS GIS Cut Line= 3
 2105289.5560921194831.4876915542105058.87317166195151.251034881
 2104955.2790921195316.472691554
#Sta/Elev= 30
       0 1965.77    20.2 1964.73    34.3 1962.97    45.8 1961.06    74.4  1954.6
    90.3 1950.43   116.5    1939   130.6 1934.64   135.3 1934.19   179.3 1934.74
   205.8 1932.49   276.3 1930.35   299.8 1928.22   306.51926.845   316.3 1925.85
   325.61926.676   339.8 1926.29   356.2 1928.02   360.4 1928.96   372.7 1933.84
   382.1 1939.53   389.7 1940.68   393.7  1941.9   413.1 1952.05   443.8 1962.88
   502.2    1978   517.6 1984.77   544.8 1994.72   562.8 2001.92   589.3 2007.44
#Mann= 5 ,-1 , 0
       0      .1       0   306.5    .045       0   325.6      .1       0
     330     .04       0  504.29      .1       0
#XS Ineff= 2 , 0
           279.2 1934.49
Permanent Ineff=
       F       F
Bank Sta=306.5,325.6
XS Rating Curve= 0 ,0
Exp/Cntr=0.3,0.1

Type RM Length L Ch R = 1 ,20840   ,189,187.9,188.7
XS GIS Cut Line= 2
     2104990.174      194698.985     2104781.411      195238.004
#Sta/Elev= 30
       0 1985.28    29.7  1975.3      50 1965.81    55.3 1961.35    65.2  1945.6
    72.9 1936.42    80.4 1931.93      94 1926.75   115.1 1925.05   143.2 1925.59
   167.8 1924.53   265.6 1925.76   276.9 1925.23   287.41923.306   301.1 1922.68
     3071923.092   315.6 1926.42   329.7 1927.08   351.8 1938.31   364.9  1940.4
     383 1949.23   403.6  1955.3   428.2 1965.89   456.3 1974.87     488 1983.07
   498.9 1986.64     527 1997.21   536.9 2002.89   544.5 2006.18     578  2017.2
#Mann= 5 ,-1 , 0
       0      .1       0     240     .04       0   287.4    .045       0
     307     .04       0     420      .1       0
Bank Sta=287.4,307
XS Rating Curve= 0 ,0
Exp/Cntr=0.3,0.1

Type RM Length L Ch R = 1 ,20652   ,415.9,411.5,404.9
XS GIS Cut Line= 3
2104834.63118318194601.0406478972104789.53527824194738.582561609
2104615.74347715195126.622323949
#Sta/Elev= 30
       0    1988      33 1980.15   126.2 1956.12   136.6 1951.58     147 1945.74
   158.4 1941.36   168.6 1935.55   186.6 1926.99   193.1 1924.71     201 1923.36
   257.7 1924.42   265.7 1922.58   276.5 1921.33   287.5 1921.49   292.21922.442
   297.4 1923.72   308.8 1924.86   344.6  1924.5   369.9 1925.43   384.3 1927.12
   391.5 1929.35   398.7 1929.48   404.2 1930.42   452.6 1952.31   468.7 1961.52
     485  1969.7   510.9 1984.46   549.7 2001.99   556.8 2006.01   569.9 2010.85
#Mann= 5 ,-1 , 0
       0      .1       0   265.7    .045       0   292.2      .1       0
  314.75     .04       0  524.75      .1       0
Bank Sta=265.7,292.2
XS Rating Curve= 0 ,0
Exp/Cntr=0.3,0.1

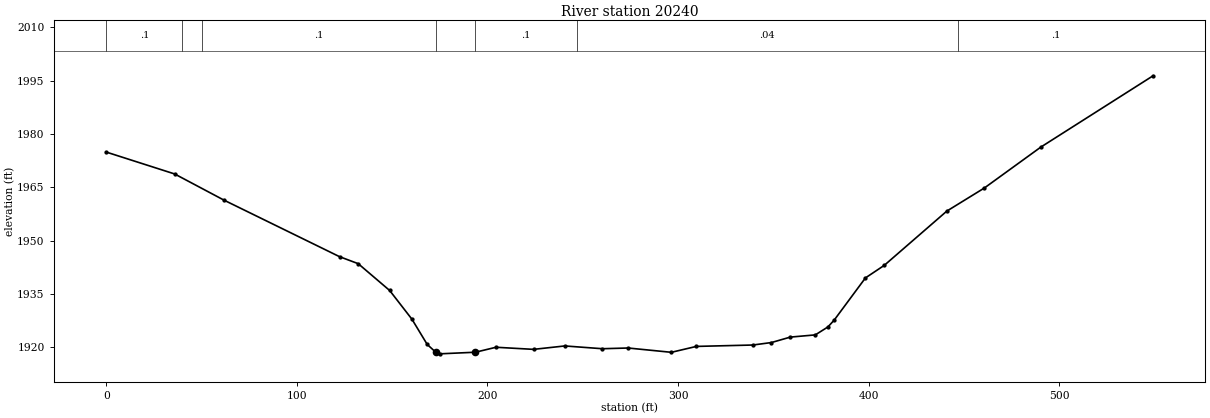
Type RM Length L Ch R = 1 ,20240   ,256.6,264.4,260
XS GIS Cut Line= 3
     2104434.857      194559.379      2104377.76      194649.647
2104356.54284836195091.526681791
#Sta/Elev= 30
       0 1974.91    35.9 1968.75    61.8 1961.38   122.4 1945.48   132.2 1943.51
   148.7 1935.97   160.4 1927.88   168.4 1920.79   172.9 1918.59   174.9 1918.14
   193.71918.594   204.5 1919.99   224.2  1919.4   240.6 1920.36   260.3 1919.58
   273.8 1919.78   296.5 1918.57   309.6 1920.23   339.2 1920.62     349 1921.32
   358.9 1922.85     372 1923.47   378.6  1925.7   381.9 1927.62   398.3  1939.5
   408.2 1943.04     441  1958.3   460.7  1964.8   490.3  1976.3   549.2 1996.37
#Mann= 7 ,-1 , 0
       0      .1       0      40    .035       0      50      .1       0
   172.9    .045       0   193.7      .1       0  246.81     .04       0
  446.81      .1       0
Bank Sta=172.9,193.7
XS Rating Curve= 0 ,0
Exp/Cntr=0.3,0.1