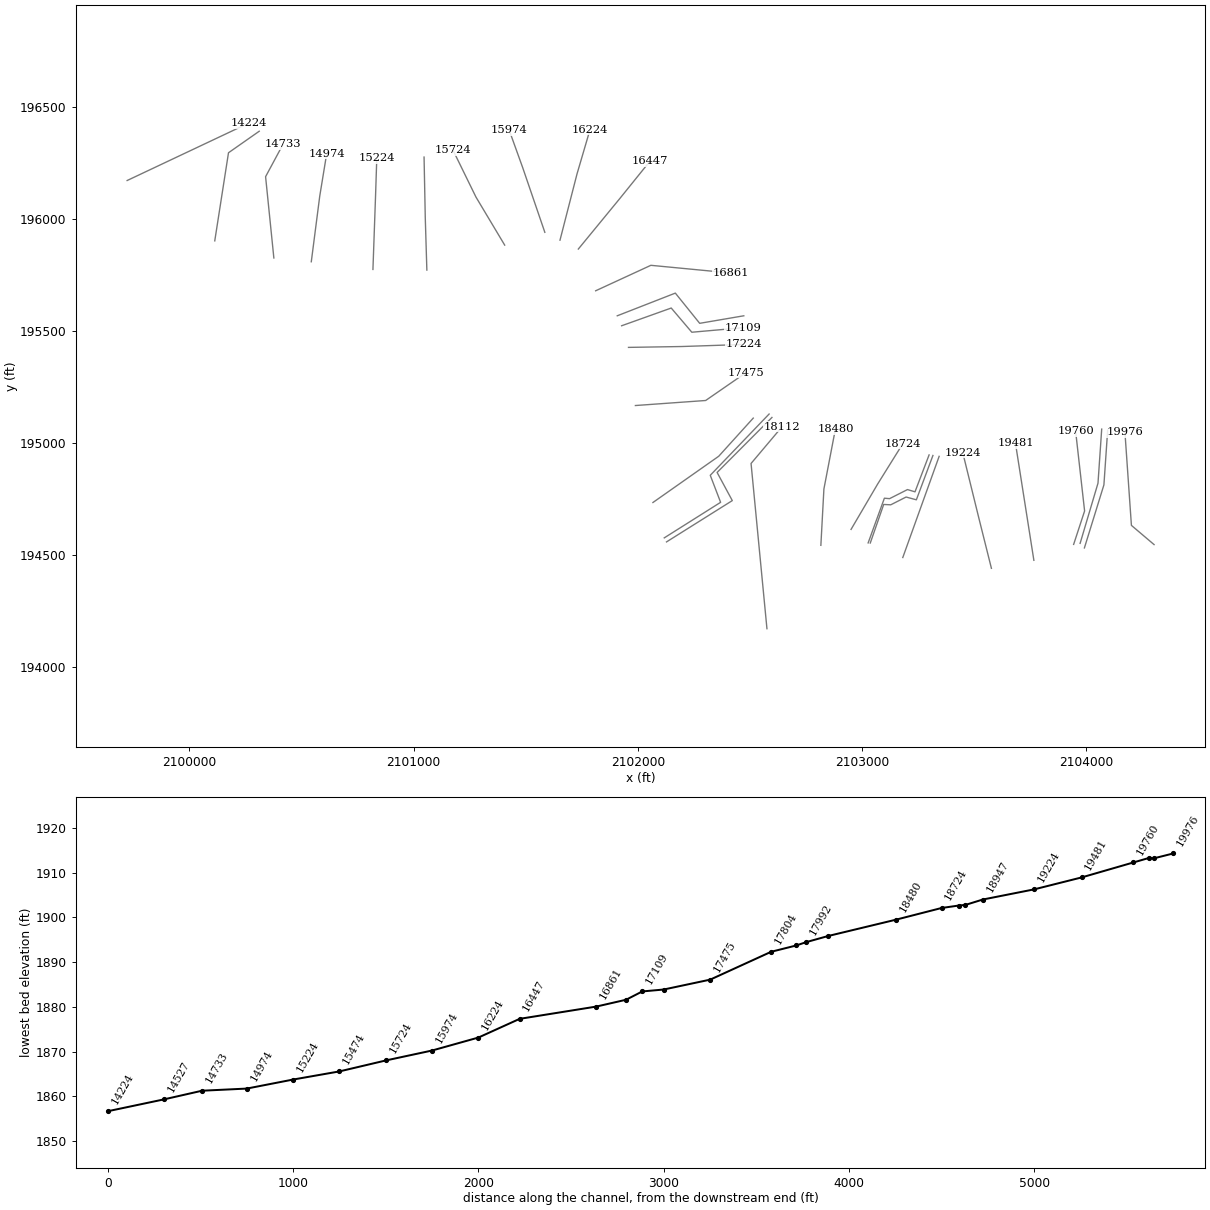
HEC-RAS study TRKYCK.prj: TRKYCK

--- TRKYCK.g01 (geometry) --- (continued)

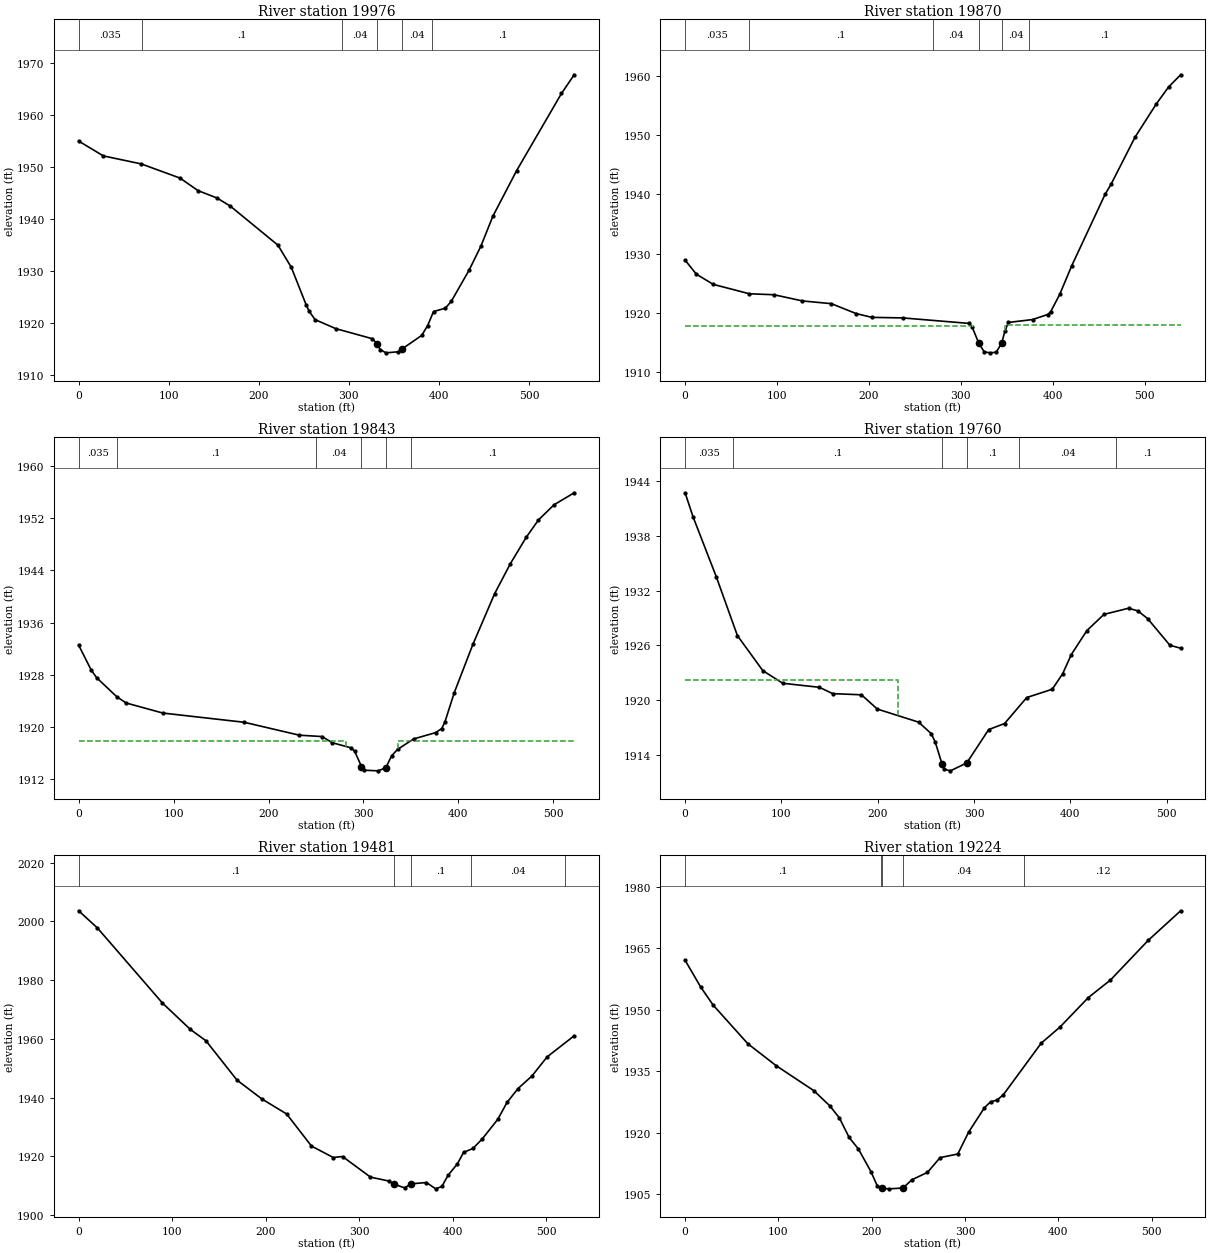
Type RM Length L Ch R = 1 ,19976   ,108.7,106.3,104.2
XS GIS Cut Line= 3
     2104301.683       194548.32     2104200.677      194634.022
2104171.69351374195050.514693134
#Sta/Elev= 30
       0    1955    27.4 1952.15    69.5 1950.61   112.5 1947.89   132.5 1945.48
   153.6 1944.06   168.3 1942.51   221.3 1934.99   236.1 1930.72   252.5 1923.55
   255.8 1922.33   262.4  1920.7   285.4 1918.97   325.8 1917.04   331.5 1916.03
   334.7 1914.94   341.2 1914.32   354.5 1914.52   359.2 1915.09   380.8 1917.67
   387.4 1919.57   393.9 1922.25   407.1  1922.9   413.7 1924.24   433.5 1930.24
   446.6 1934.86   459.7 1940.54     486 1949.28   535.9 1964.14     550 1967.73
#Mann= 6 ,-1 , 0
       0    .035       0      70      .1       0  292.47     .04       0
   331.5    .045       0   359.2     .04       0  392.47      .1       0
Bank Sta=331.5,359.2
XS Rating Curve= 0 ,0
Exp/Cntr=0.5,0.3

Type RM Length L Ch R = 1 ,19870   ,26.9,27,26.9
XS GIS Cut Line= 3
2103991.03560601194533.4043484982104078.02467328194814.772586832
2104094.78021459195058.967695708
#Sta/Elev= 30
       0 1928.89    12.3 1926.51    30.7 1924.79      70  1923.2    96.8 1923.04
   127.7 1921.99   159.2 1921.53     186 1919.86   203.2 1919.21   236.8 1919.12
     309 1918.19   312.3 1917.62   319.61914.852   325.5 1913.38     332 1913.21
   338.6 1913.32  344.54 1914.86   348.1 1916.91   351.8 1918.35   378.1 1918.84
   394.5 1919.69   397.8 1920.15   407.7 1923.09   420.8 1927.95     457    1940
   463.6 1941.74   489.7  1949.7   512.9 1955.34   526.1 1958.17   539.3 1960.25
#Mann= 6 ,-1 , 0
       0    .035       0      70      .1       0     270     .04       0
   319.6    .045       0  344.54     .04       0  374.51      .1       0
#XS Ineff= 2 , 0
          313.51 1917.74  348.22         1917.86
Permanent Ineff=
       F       F
Bank Sta=319.6,344.54
XS Rating Curve= 0 ,0
Exp/Cntr=0.5,0.3

Type RM Length L Ch R = 1 ,19843   ,81.5,82.5,84.4
XS GIS Cut Line= 3
2103971.96004163 194553.90426266 2104051.6453235194822.309543913
2104068.16669313       195063.64
#Sta/Elev= 30
       0 1932.55    13.4 1928.68    19.2 1927.52    40.3 1924.62    50.1 1923.68
    88.7 1922.14   174.3 1920.73   232.5 1918.75   256.4 1918.54   267.2 1917.59
   287.3  1916.8   290.8 1916.26   297.9 1913.95   300.1 1913.39   315.5 1913.29
   323.6 1913.77   329.6 1915.59   335.9 1916.57   352.7 1918.17   375.9 1919.14
   382.3 1919.75   385.6  1920.7   395.5 1925.22   415.2 1932.65   438.2 1940.45
   454.7 1945.02   471.3 1949.04   484.3 1951.72   500.7 1954.04   521.9 1955.88
#Mann= 6 ,-1 , 0
       0    .035       0      40      .1       0     250     .04       0
   297.9    .045       0   323.6     .04       0  349.98      .1       0
#XS Ineff= 2 , 0
          282.03 1917.89  335.96         1917.89
Permanent Ineff=
       F       F
Bank Sta=297.9,323.6
XS Rating Curve= 0 ,0
Exp/Cntr=0.5,0.3

Type RM Length L Ch R = 1 ,19760   ,276.2,279.5,278.7
XS GIS Cut Line= 3
2103943.05185786194549.1509127142103991.94724726194698.340557253
  2103951.961995195053.591389857
#Sta/Elev= 30
       0 1942.69     8.2 1940.08    32.6 1933.45    54.3 1927.08    80.7 1923.25
   101.4 1921.87   139.4 1921.43   153.2 1920.74   183.1 1920.61   199.6 1919.05
   242.5 1917.62   255.7 1916.35   259.8 1915.42   266.9    1913   268.9 1912.48
   275.5  1912.3   292.5 1913.17   315.2 1916.81   331.7 1917.47   354.7 1920.31
   381.2 1921.22     392 1922.91     401 1925.01   417.1 1927.62   434.9  1929.4
   460.4 1930.07   470.1 1929.78   480.2 1928.94   503.3 1926.03   514.5  1925.7
#Mann= 6 ,-1 , 0
       0    .035       0      50      .1       0   266.9    .045       0
   292.5      .1       0     347     .04       0     447      .1       0
#XS Ineff= 2 , 0
          221.21 1922.28
Permanent Ineff=
       F       F
Bank Sta=266.9,292.5
XS Rating Curve= 0 ,0
Exp/Cntr=0.3,0.1

Type RM Length L Ch R = 1 ,19481   ,256.9,256.1,257.2
XS GIS Cut Line= 2
     2103765.721      194478.173     2103683.453      195001.801
#Sta/Elev= 30
       0 2003.58      20 1997.76    89.7 1972.17   119.6 1963.18   136.2 1959.34
   169.4 1945.96     196 1939.54   222.5 1934.43   249.1  1923.5   272.4 1919.61
   282.3 1919.95   312.2 1912.94   332.1 1911.59     3371910.572   348.7 1909.29
   355.81910.653     372  1911.1     382 1908.95   388.6 1909.77   395.2 1913.56
   405.2 1917.46   411.8 1921.37   421.8 1922.68   431.8 1925.96   448.4 1932.61
   458.3 1938.38   470.1 1943.09   484.9 1947.35   501.2 1953.87   530.1 1961.03
#Mann= 5 ,-1 , 0
       0      .1       0     337    .045       0   355.8      .1       0
     420     .04       0     520      .1       0
Bank Sta=337,355.8
XS Rating Curve= 0 ,0
Exp/Cntr=0.3,0.1

Type RM Length L Ch R = 1 ,19224   ,287.2,277.8,267
XS GIS Cut Line= 3
     2103576.419      194442.443     2103522.144      194659.544
     2103448.744      194958.059
#Sta/Elev= 30
       0 1962.08    16.6  1955.6    30.1 1951.13    67.3  1941.7    97.7 1936.34
     138 1930.25   155.2 1926.53   165.4 1923.59   175.8 1918.84   185.7 1916.03
   199.2  1910.5     206 1907.02   210.81906.397   219.1 1906.28   233.61906.486
   243.1 1908.49   259.8  1910.3   273.4 1913.91   292.3 1914.78   303.9 1920.11
   320.8 1926.06   327.5 1927.54   334.4 1927.95   341.1 1929.24   381.8 1941.86
   401.9 1945.79   432.3 1952.99     456 1957.27   496.5 1966.96   531.2 1974.17
#Mann= 5 ,-1 , 0
       0      .1       0     210     .04       0   210.8    .045       0
   233.6     .04       0  363.78     .12       0
Bank Sta=210.8,233.6
XS Rating Curve= 0 ,0
Exp/Cntr=0.3,0.1

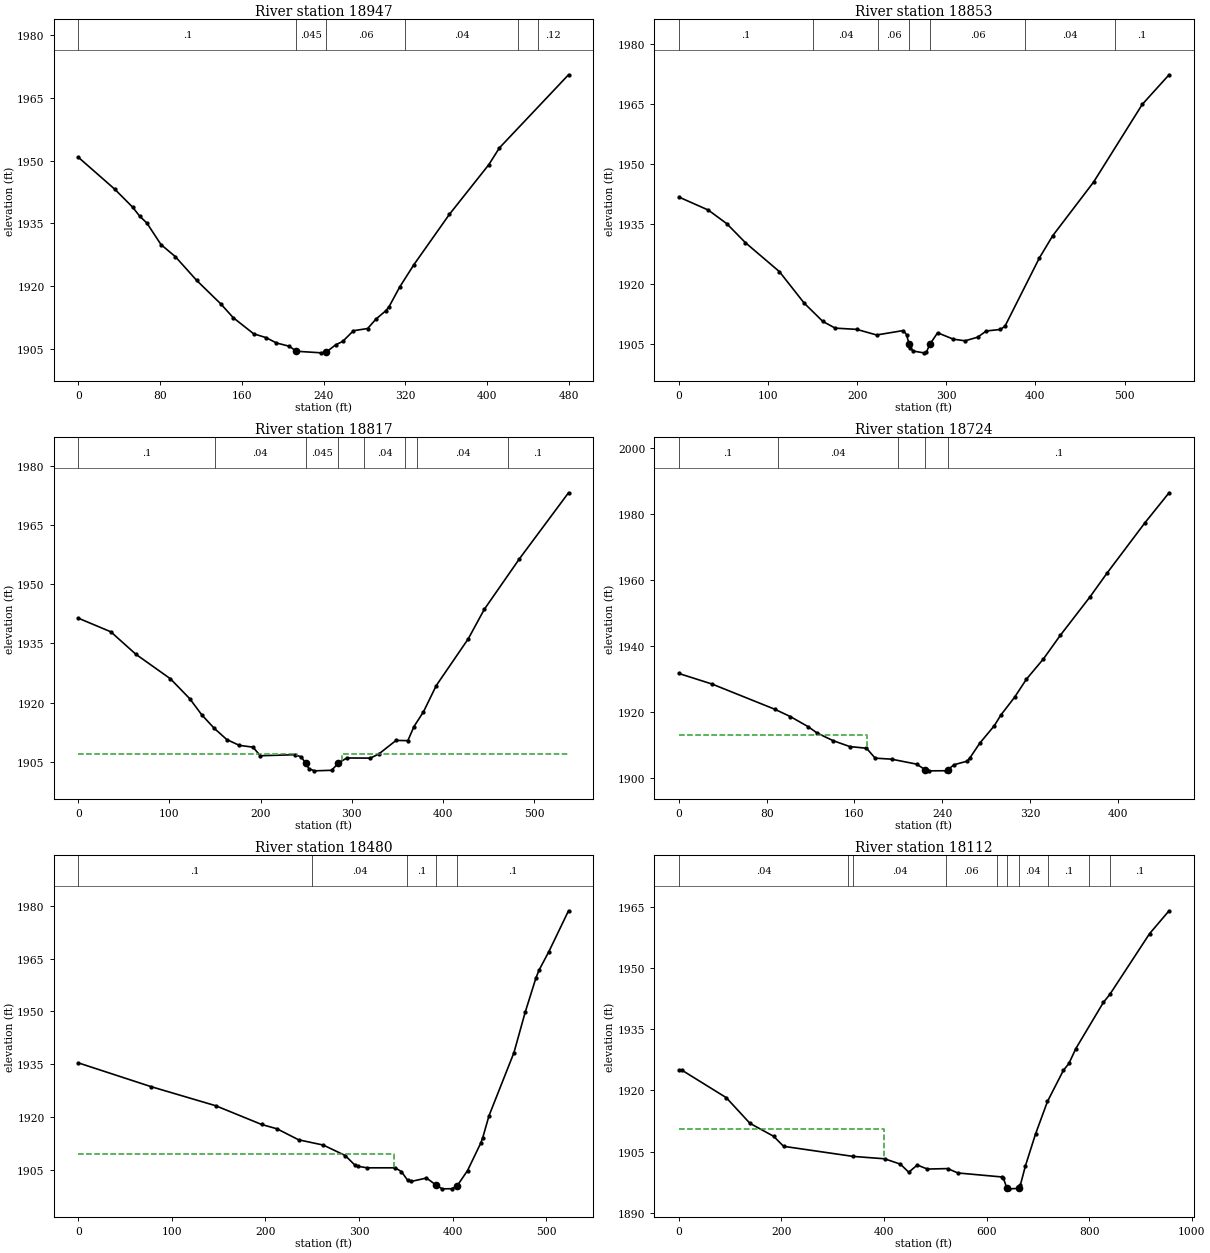
Type RM Length L Ch R = 1 ,18947   ,103.4,93.4,79.9
XS GIS Cut Line= 2
     2103181.242      194490.603 2103343.3225127194942.068803704
#Sta/Elev= 30
       0  1950.8    35.6 1943.17    53.1 1938.87      60 1936.72      67 1935.08
    80.9  1929.9    94.9 1927.03   115.8 1921.33   139.4 1915.71   151.5 1912.43
   171.6 1908.55   183.6 1907.65   193.9 1906.36   206.4 1905.58   213.4 1904.38
   237.8    1904   242.6 1904.17   251.8 1905.92   258.7 1906.73   269.2 1909.29
   283.1 1909.82   291.3 1912.09   300.6 1914.01     304 1915.01   314.4 1919.72
   328.4 1925.11   363.1 1937.14   401.7 1949.04   412.1 1953.06   479.7 1970.55
#Mann= 6 ,-1 , 0
       0      .1       0   213.4    .045       0   242.6     .06       0
     320     .04       0     430      .1       0     450     .12       0
Bank Sta=213.4,242.6
XS Rating Curve= 0 ,0
Exp/Cntr=0.5,0.3

Type RM Length L Ch R = 1 ,18853   ,37.6,36,33.2
XS GIS Cut Line= 6
2103036.26478726194555.3546883232103096.12207859194727.366028364
2103127.58961914194725.8434054342103195.96029354194760.526652217
2103241.78633889194748.175208407 2103315.6017206194945.943918471
#Sta/Elev= 30
       01941.715  32.9491938.474  53.7921935.054  74.6351930.321 112.8471923.071
 140.6371915.202  161.481910.647 175.3751908.973 199.5371908.661 221.8161907.261
 251.6771908.365 255.5181907.329  258.11 1905.01  259.361904.004 263.2011903.234
 274.724  1902.8 277.6491902.962  281.65 1904.96 290.2661907.812  307.881906.218
 321.0861905.801 335.2511906.715 344.8561908.256 360.8251908.649 365.8681909.463
 404.389 1926.48 419.4771932.076 465.3791945.488 519.9521964.885 549.9521972.263
#Mann= 7 ,-1 , 0
       0      .1       0     150     .04       0  223.63     .06       0
  258.11    .045       0  281.65     .06       0  388.86     .04       0
  488.86      .1       0
#XS Ineff= 2 , 0
          250.31    1907  291.13            1907
Permanent Ineff=
       F       F
Bank Sta=258.11,281.65
XS Rating Curve= 0 ,0
Exp/Cntr=0.5,0.3

Type RM Length L Ch R = 1 ,18817   ,83.6,92.8,104.9
XS GIS Cut Line= 6
     2103026.779      194555.8272103099.16732445 194755.28078208
     2103122.266       194753.312103202.19814271194793.853896305
2103235.69584717194783.7030767722103298.50281868194948.446394055
#Sta/Elev= 30
       01941.413  35.5851937.958  63.1141932.253 100.967 1926.04 122.2761920.965
 135.3791916.889 149.1431913.449 162.9081910.602 176.6721909.126 191.6191908.671
 199.7121906.493 237.2811906.752 244.6491906.205 249.4131904.594 253.0921903.206
 258.9421902.658     2781902.797  285.23  1904.6 294.6121905.922 320.517 1905.89
 329.7461906.938 348.6851910.383 361.6251910.324 368.3411913.905 378.7751917.657
 392.8191924.317 427.9311936.188 445.4871943.654  484.111956.504 537.934 1973.25
#Mann= 8 ,-1 , 0
       0      .1       0     150     .04       0 249.413    .045       0
  285.23     .06       0  313.63     .04       0  358.69     .06       0
  371.62     .04       0  471.62      .1       0
#XS Ineff= 2 , 0
          240.41    1907  289.07            1907
Permanent Ineff=
       F       F
Bank Sta=249.413,285.23
XS Rating Curve= 0 ,0
Exp/Cntr=0.5,0.3

Type RM Length L Ch R = 1 ,18724   ,239.3,244.7,250.7
XS GIS Cut Line= 3
2102950.56142643194616.110105228     2103069.254      194818.666
2103181.33569501  194998.6494197
#Sta/Elev= 30
       0 1931.64    30.3 1928.43    87.3 1920.81   101.7 1918.55   117.8 1915.51
   126.2 1913.54   140.6 1911.26   155.8 1909.47     171 1908.97   178.9 1905.96
   193.8 1905.65   216.6 1904.15   224.31902.503     228 1902.11   243.4 1902.14
   245.3  1902.5   250.8 1903.96   262.7 1905.04   265.1 1905.95   274.3 1910.52
   287.5 1915.79   293.6 1919.09   306.1 1924.48   316.8 1929.92   332.3 1936.07
   347.7 1943.23   374.8 1954.91   390.2 1962.06     425 1977.44   446.8 1986.46
#Mann= 5 ,-1 , 0
       0      .1       0      90     .04       0     200      .1       0
   224.3    .045       0   245.3      .1       0
#XS Ineff= 2 , 0
          171.26 1913.11
Permanent Ineff=
       F       F
Bank Sta=224.3,245.3
XS Rating Curve= 0 ,0
Exp/Cntr=0.3,0.1

Type RM Length L Ch R = 1 ,18480   ,364.1,367.8,373.2
XS GIS Cut Line= 3
     2102815.959      194545.0172102829.50282834194796.303278465
     2102880.721      195063.715
#Sta/Elev= 30
       0 1935.34    77.7 1928.58   146.7 1923.16   195.9 1917.82   212.4 1916.58
   235.4 1913.46   261.8 1911.96   285.2 1908.99   295.2 1906.36   298.6 1905.94
   308.6 1905.49   338.6 1905.49   345.3 1904.42     352 1901.92   355.4  1901.6
   372.1 1902.58   381.91900.677   388.8 1899.51   399.1 1899.54   404.61900.267
     416 1904.72     430 1912.47   432.2 1914.04   438.9 1920.29   465.6 1938.27
   477.6 1949.76   489.1 1959.51   492.3 1961.68   502.9 1966.99   523.9 1978.61
#Mann= 5 ,-1 , 0
       0      .1       0     250     .04       0  351.65      .1       0
   381.9    .045       0   404.6      .1       0
#XS Ineff= 2 , 0
          337.61 1909.48
Permanent Ineff=
       F       F
Bank Sta=381.9,404.6
XS Rating Curve= 0 ,0
Exp/Cntr=0.3,0.1

Type RM Length L Ch R = 1 ,18112   ,111.1,119.9,125.6
XS GIS Cut Line= 3
2102575.53097691194172.9906303382102504.69240545194910.295422888
     2102643.386      195074.805
#Sta/Elev= 30
       0 1924.92     6.7 1924.91    92.4 1918.23   138.5 1911.93   184.7 1908.75
   204.2 1906.28     340  1903.8   401.1 1903.22   431.9 1901.91   448.3 1899.91
   464.8 1901.69   484.6  1900.7   524.2 1900.81   543.9 1899.74   629.6 1898.76
   632.9 1898.46   639.5 1896.02   642.8 1895.84   662.6 1895.94   665.9 1896.75
   675.8 1901.49   695.5  1909.3   718.8  1917.3   749.7  1924.9   760.7 1926.64
   774.1 1930.28   827.8 1941.61   840.7 1943.64   917.9  1958.5   955.9 1964.12
#Mann= 10 ,-1 , 0
       0     .04       0     330     .06       0     340     .04       0
     520     .06       0     620     .04       0   639.5    .045       0
   662.6     .04       0     720      .1       0   800.7     .04       0
   840.7      .1       0
#XS Ineff= 2 , 0
             400 1910.53
Permanent Ineff=
       F       F
Bank Sta=639.5,662.6
XS Rating Curve= 0 ,0
Exp/Cntr=0.5,0.3

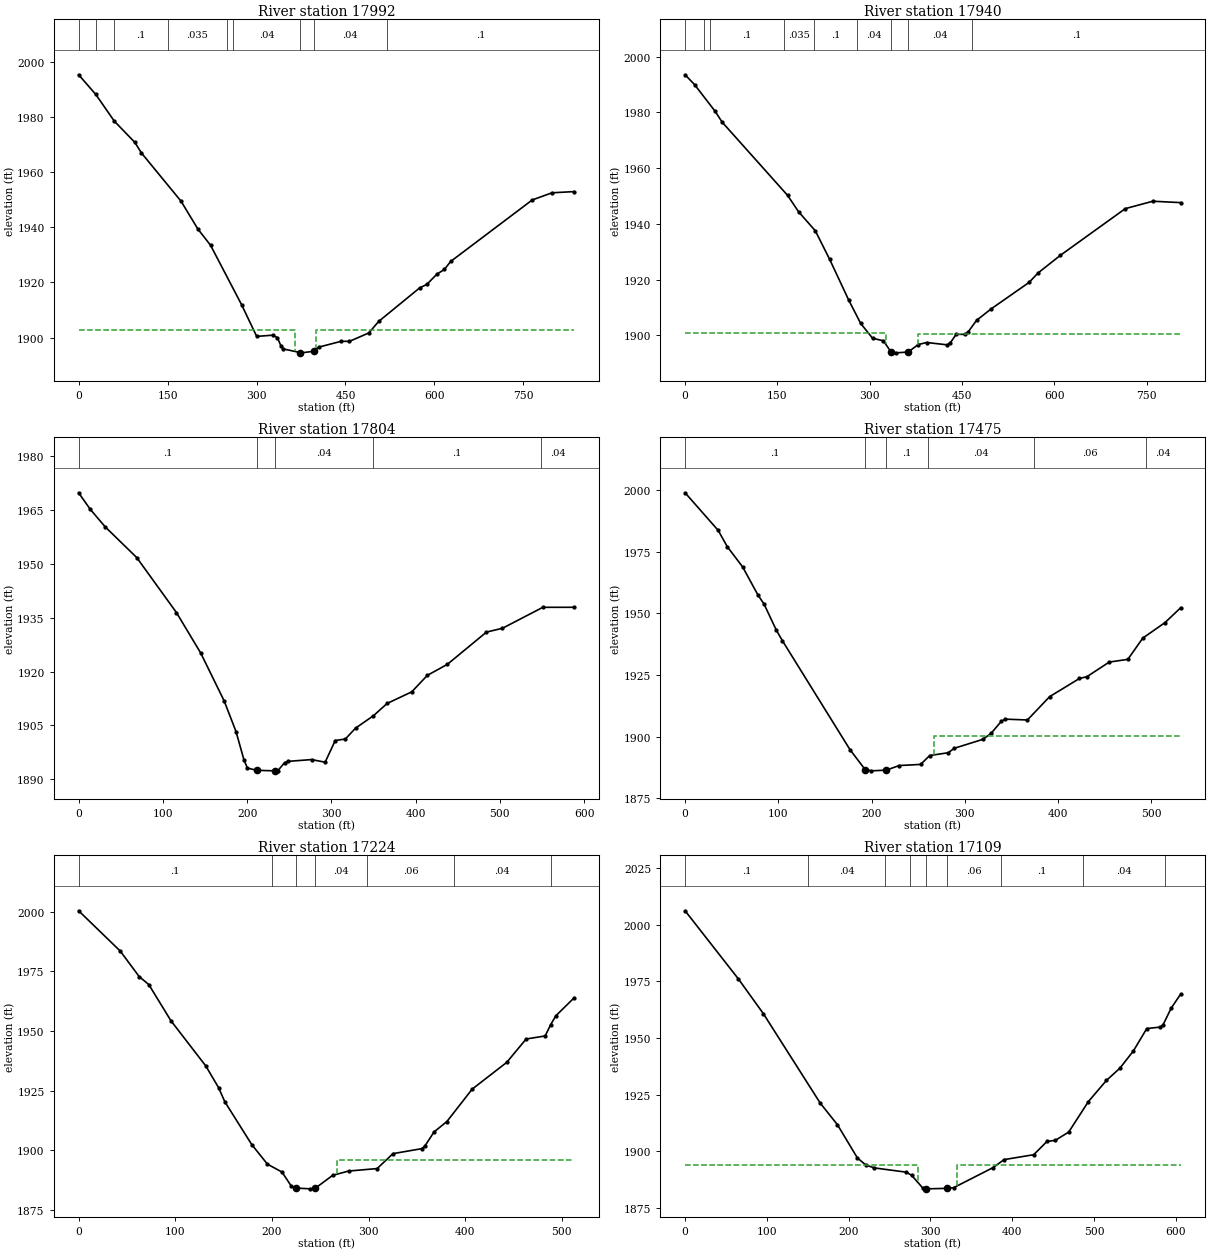
Type RM Length L Ch R = 1 ,17992   ,53.6,51.5,53.4
XS GIS Cut Line= 4
     2102127.669      194560.253 2102421.0535092194744.624902888
2102353.29797874194870.214898241     2102597.818      195115.582
#Sta/Elev= 30
       0 1995.35      29  1988.2      60 1978.57    94.9 1970.79   105.8 1967.01
   172.5 1949.53     201  1939.4   222.4  1933.5   274.8 1911.91   300.2 1900.42
   327.1 1900.85   335.1 1899.97   341.4 1896.84   345.2 1895.86   373.21894.573
   375.6 1894.45   396.21895.011   405.4 1896.55   442.7 1898.64   456.6 1898.62
   489.2 1901.65     506 1905.86     575 1918.01   587.2 1919.29   604.1    1923
   616.7  1924.7   627.3  1927.6   764.9 1949.93   798.3 1952.53   835.6 1952.96
#Mann= 9 ,-1 , 0
       0      .1       0      30    .035       0      60      .1       0
     150    .035       0     250      .1       0     260     .04       0
   373.2    .045       0   396.2     .04       0  519.21      .1       0
#XS Ineff= 2 , 0
          364.91 1902.78  399.54         1902.84
Permanent Ineff=
       F       F
Bank Sta=373.2,396.2
XS Rating Curve= 0 ,0
Exp/Cntr=0.5,0.3

Type RM Length L Ch R = 1 ,17940   ,155.3,136.3,109.1
XS GIS Cut Line= 4
2102117.64551147194578.3073967572102368.92206883194736.915534414
2102322.79009177194857.453977057     2102585.156      195130.914
#Sta/Elev= 30
       0 1993.51    15.3    1990    48.7 1980.43    60.3 1976.49   166.6 1950.22
   184.4 1944.35   211.6 1937.52   234.9 1927.28   265.9 1912.64   285.3 1904.28
   304.7 1898.95   322.2 1898.06   334.81893.992   343.5 1893.73   362.51894.027
   378.9 1896.71   392.5 1897.44   426.3 1896.59     431 1897.33   440.5 1900.37
   455.3 1900.36   459.9 1901.22   473.5 1905.37   496.8 1909.42     559 1919.01
   573.5 1922.39   609.9 1928.74   715.3 1945.48     760 1948.13   805.2 1947.64
#Mann= 9 ,-1 , 0
       0      .1       0      30    .035       0      40      .1       0
     160    .035       0     210      .1       0     280     .04       0
   334.8    .045       0   362.5     .04       0  466.21      .1       0
#XS Ineff= 2 , 0
          325.73 1900.91  378.48          1900.5
Permanent Ineff=
       F       F
Bank Sta=334.8,362.5
XS Rating Curve= 0 ,0
Exp/Cntr=0.5,0.3

Type RM Length L Ch R = 1 ,17804   ,335.9,328.9,318.4
XS GIS Cut Line= 3
2102067.14698476194736.1131293942102360.55776363 194942.54341112
2102514.42035844195112.710328329
#Sta/Elev= 30
       0 1969.87    13.6 1965.32    31.4  1960.4      69 1951.79   116.1 1936.46
   144.8 1925.22   172.7 1911.84   186.8 1903.27   196.2  1895.4   200.3  1893.1
   211.2 1892.46   232.4 1892.31   232.81892.314   236.4 1892.35   244.4 1894.56
   248.4 1894.95   276.5 1895.45   292.6 1894.72   304.6 1900.77   316.6 1901.19
   328.7 1904.22     350 1907.69   366.1  1911.1   395.4 1914.34   413.9 1918.94
   437.7 1922.02   484.1 1931.01   503.1 1932.08     551 1937.92   588.2 1937.93
#Mann= 5 ,-1 , 0
       0      .1       0   211.2    .045       0   232.8     .04       0
     350      .1       0  548.75     .04       0
Bank Sta=211.2,232.8
XS Rating Curve= 0 ,0
Exp/Cntr=0.3,0.1

Type RM Length L Ch R = 1 ,17475   ,251,250.8,249.2
XS GIS Cut Line= 3
     2101989.007      195168.838      2102302.24      195191.313
     2102480.966      195314.866
#Sta/Elev= 30
       0 1998.89    35.4 1983.67    45.2 1977.04    61.7 1968.81    78.1 1957.42
    84.7  1953.7    97.9 1943.08   104.4 1938.83   176.8 1894.67     1931886.612
   199.8 1886.08   215.91886.367   229.4 1888.22   252.5 1888.69   262.3  1892.3
   282.1 1893.42   288.6 1895.23   319.1 1898.84     328 1901.25   339.1  1906.2
   343.1 1907.06     367 1906.71   390.9 1916.19   422.8 1923.55   430.8 1924.27
   454.7  1930.2   474.7 1931.31   490.7 1939.92   514.6 1946.24   531.3 1952.23
#Mann= 6 ,-1 , 0
       0      .1       0     193    .045       0   215.9      .1       0
     260     .04       0  374.04     .06       0  494.04     .04       0
#XS Ineff= 2 , 0
                          267.36         1900.36
Permanent Ineff=
       F       F
Bank Sta=193,215.9
XS Rating Curve= 0 ,0
Exp/Cntr=0.3,0.1

Type RM Length L Ch R = 1 ,17224   ,132.6,115.7,100.4
XS GIS Cut Line= 3
     2101958.269      195428.268     2102196.634      195432.171
     2102470.847      195441.352
#Sta/Elev= 30
       0 2000.46      43  1983.6    62.7 1972.85    72.6 1969.53    95.5 1954.37
   131.6 1935.39   144.8 1926.31   151.3 1920.37   179.1 1902.46   195.4 1894.21
   210.4 1890.93   220.2 1884.94   225.31884.182   239.9 1883.87   244.91884.125
   262.9 1889.53   279.3 1891.33   308.9 1892.37   325.3 1898.63     355 1900.71
   358.1 1901.71   367.9 1907.77   381.1  1912.1   407.3  1925.7     443 1936.89
   463.1  1946.7   482.8 1947.97   488.4 1952.65   493.9 1956.45   512.8 1963.98
#Mann= 7 ,-1 , 0
       0      .1       0     200     .04       0   225.3    .045       0
   244.9     .04       0   298.4     .06       0   388.4     .04       0
   488.4      .1       0
#XS Ineff= 2 , 0
                          267.46         1896.02
Permanent Ineff=
       F       F
Bank Sta=225.3,244.9
XS Rating Curve= 0 ,0
Exp/Cntr=0.5,0.3

Type RM Length L Ch R = 1 ,17109   ,101.9,87.6,85.9
XS GIS Cut Line= 4
     2101927.604      195524.7942102148.73276681195603.909241297
2102240.54107773195495.884973296     2102469.054      195516.114
#Sta/Elev= 30
       0 2006.17    65.3 1976.03    95.7 1960.77   165.3 1921.26   186.3 1911.74
   210.7 1897.08   221.1 1893.93   231.6 1892.67   270.6 1890.79   277.2 1889.35
   290.9  1883.7   294.81883.478   295.8 1883.44   320.6 1883.66   328.4 1883.95
   376.6 1892.81   390.1 1896.34   426.3  1898.5   442.6 1904.39   452.6 1904.81
   469.1 1908.49   493.2 1921.96   515.2 1931.27   531.7 1936.69   548.2  1944.3
   564.6 1954.19   581.1 1954.83   584.4 1955.76   594.4 1963.18     606 1969.37
#Mann= 9 ,-1 , 0
       0      .1       0     150     .04       0  244.86      .1       0
  274.86     .06       0   294.8    .045       0   320.6     .06       0
  386.62      .1       0  486.62     .04       0  586.62      .1       0
#XS Ineff= 2 , 0
          285.22 1893.93   332.4         1893.78
Permanent Ineff=
       F       F
Bank Sta=294.8,320.6
XS Rating Curve= 0 ,0
Exp/Cntr=0.5,0.3

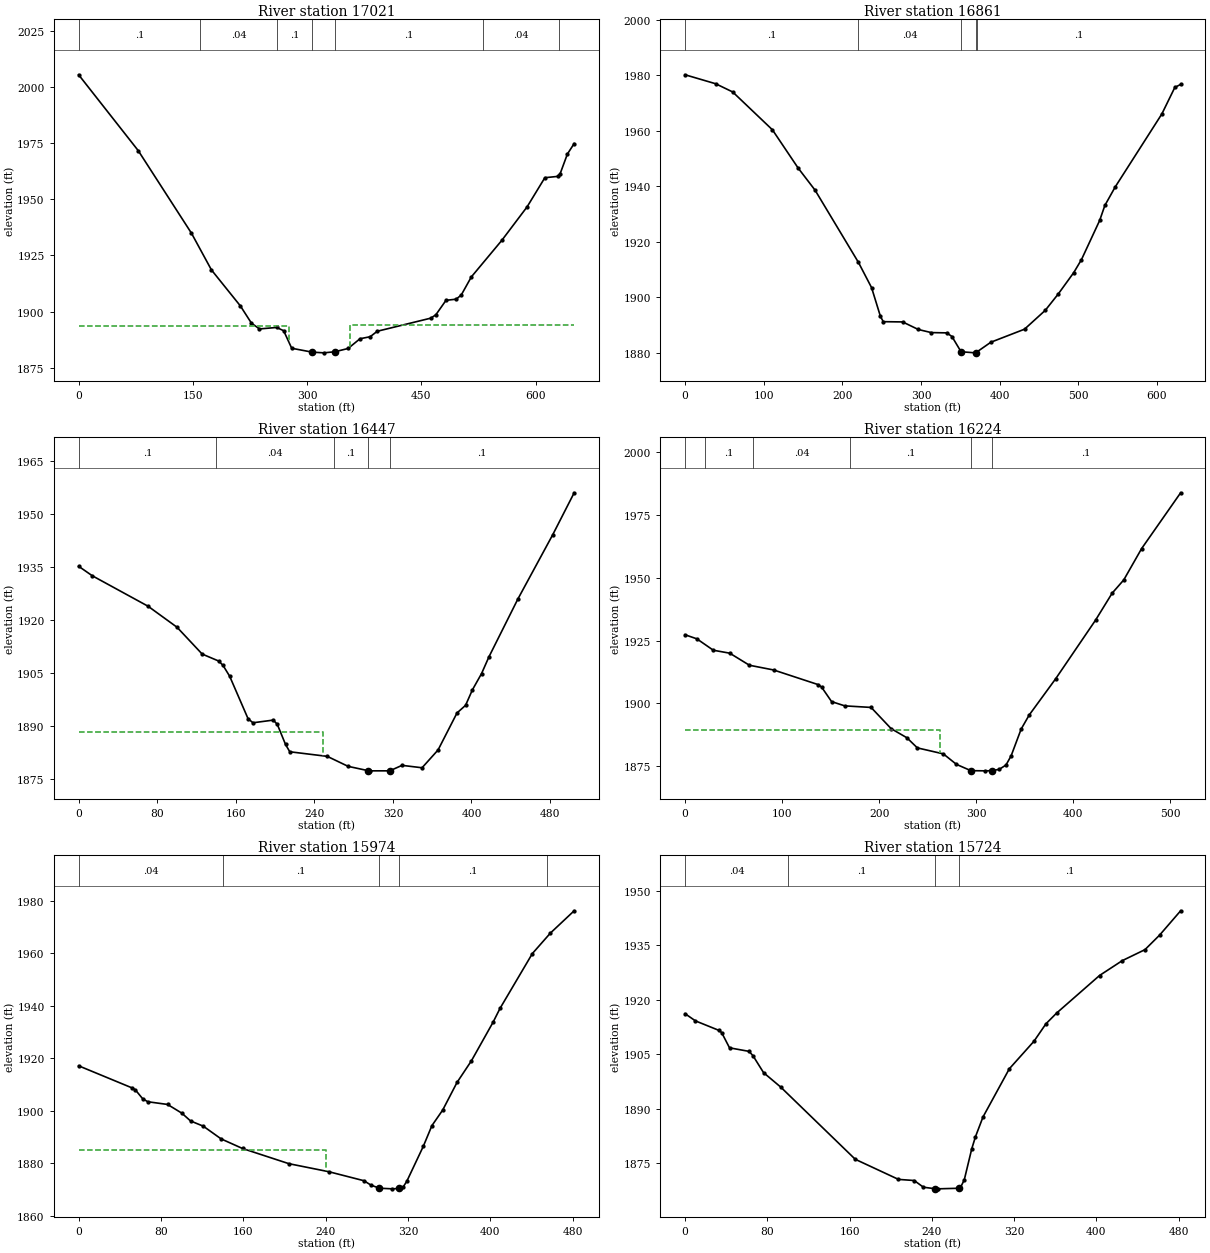
Type RM Length L Ch R = 1 ,17021   ,129.9,159.9,174.2
XS GIS Cut Line= 4
     2101908.073      195569.2822102167.06268097195670.477276108
2102275.61878541195535.653938485     2102472.309      195569.282
#Sta/Elev= 30
       0  2005.6    78.2  1971.8   148.2 1934.92   174.4 1918.56   212.4  1902.5
   226.9 1894.83   237.5 1892.24     260  1892.9   269.2 1891.45   279.8 1883.62
   306.61881.894   321.9 1881.58   336.41882.057   353.8 1883.52   369.5 1887.87
   382.8 1888.76   392.1  1891.2   462.4 1897.05   469.1 1898.57   482.4    1905
   495.7 1905.51   502.4 1907.36   515.7 1915.46   555.6 1931.71   588.9  1946.7
   612.2 1959.69   628.9 1960.27   632.2  1961.4   641.8 1970.25   650.7 1974.93
#Mann= 7 ,-1 , 0
       0      .1       0     160     .04       0     260      .1       0
   306.6    .045       0   336.4      .1       0  531.15     .04       0
  631.15      .1       0
#XS Ineff= 2 , 0
          276.65 1893.64  356.64         1893.96
Permanent Ineff=
       F       F
Bank Sta=306.6,336.4
XS Rating Curve= 0 ,0
Exp/Cntr=0.5,0.3

Type RM Length L Ch R = 1 ,16861   ,399.8,414.2,428.6
XS GIS Cut Line= 3
 2101811.8242194195680.8618753092102057.96175291195794.516921518
2102415.49471129195760.156889245
#Sta/Elev= 30
       0 1980.18    38.9 1976.95    60.5    1974   111.1 1960.36   143.8 1946.59
   165.3 1938.64   220.5 1912.62   237.2 1903.53   248.5 1893.15   252.1 1891.28
   276.7 1891.19   296.6 1888.47   313.1 1887.35   332.8 1887.25   339.4 1885.94
     3511880.451   369.1 1880.06   369.61880.074   388.9 1883.88   431.7 1888.57
   458.1 1895.36   474.6 1901.24   494.4 1908.98   504.2 1913.65   527.3 1927.72
   533.9 1933.12   547.1 1939.81   606.4 1966.07   622.9 1975.63   630.3 1976.71
#Mann= 5 ,-1 , 0
       0      .1       0     220     .04       0     351    .045       0
   369.6     .04       0  371.11      .1       0
Bank Sta=351,369.6
XS Rating Curve= 0 ,0
Exp/Cntr=0.3,0.1

Type RM Length L Ch R = 1 ,16447   ,216.7,223.1,229.8
XS GIS Cut Line= 3
     2101734.518       195867.13     2101919.095      196092.039
     2102053.185      196258.358
#Sta/Elev= 30
       0 1935.12    13.9 1932.44    70.7 1923.83   100.2 1917.89   125.8 1910.31
   142.8 1908.32   147.1 1907.08   153.8 1904.04   172.5 1892.06   177.5 1890.89
   198.2 1891.65   202.3 1890.45   210.7 1884.76     215  1882.7   253.2  1881.4
   274.4 1878.58   294.21877.394   296.5 1877.31   316.81877.311   329.3 1878.86
   349.7 1878.18     366 1883.21   385.3 1893.67     394 1895.82     401 1900.21
   410.3  1904.8   417.8 1909.52   447.3 1925.88   482.7    1944   504.6 1955.89
#Mann= 5 ,-1 , 0
       0      .1       0     140     .04       0     260      .1       0
   294.2    .045       0   316.8      .1       0
#XS Ineff= 2 , 0
          248.41 1888.25
Permanent Ineff=
       F       F
Bank Sta=294.2,316.8
XS Rating Curve= 0 ,0
Exp/Cntr=0.3,0.1

Type RM Length L Ch R = 1 ,16224   ,239.5,250,257.6
XS GIS Cut Line= 3
     2101652.747       195906.74     2101728.713      196202.542
2101786.55098256196399.617902998
#Sta/Elev= 30
       0 1927.34    12.1 1925.73    29.1 1921.18      46 1920.01    66.3  1915.2
    91.2 1913.32   137.5 1907.44   140.9 1906.39     151 1900.71   164.6 1899.01
   191.7 1898.39   212.4 1889.93   228.6 1886.31   239.4 1882.27   266.2 1879.88
   279.7  1875.7   294.61873.188   309.4 1873.12   316.2 1873.17   323.9 1873.73
   330.8 1875.45   336.1 1879.13   346.4 1889.76   354.7 1895.37   382.1 1909.88
   423.1 1933.18   440.2 1943.92   452.2 1949.22   470.6 1961.71   510.8 1983.93
#Mann= 6 ,-1 , 0
       0     .04       0      20      .1       0      70     .04       0
     170      .1       0   294.6    .045       0   316.2      .1       0
#XS Ineff= 2 , 0
          262.82 1889.59
Permanent Ineff=
       F       F
Bank Sta=294.6,316.2
XS Rating Curve= 0 ,0
Exp/Cntr=0.3,0.1

Type RM Length L Ch R = 1 ,15974   ,245.6,249.4,249.8
XS GIS Cut Line= 3
2101585.15207466195941.734440329     2101486.437      196230.363
     2101426.715      196396.257
#Sta/Elev= 30
       0 1917.09    52.3 1908.61    55.2 1907.88    62.2 1904.55    67.2  1903.4
    86.4 1902.37   100.3 1899.04   108.7 1896.09   121.1 1894.09   138.4 1889.25
   159.2 1885.59   204.3  1879.8   243.1 1876.74   277.1 1873.32     284 1871.64
   292.21870.461   304.8 1870.22   311.51870.369   315.3 1870.95   318.8 1873.09
   334.8 1886.39   343.2  1894.3   353.7 1900.25   367.6 1910.76   381.6 1919.01
   402.6 1933.69   409.4 1938.99   440.8 1959.86   458.3 1967.65   481.4 1976.15
#Mann= 5 ,-1 , 0
       0     .04       0     140      .1       0   292.2    .045       0
   311.5      .1       0  455.04     .08       0
#XS Ineff= 2 , 0
           240.3 1885.18
Permanent Ineff=
       F       F
Bank Sta=292.2,311.5
XS Rating Curve= 0 ,0
Exp/Cntr=0.3,0.1

Type RM Length L Ch R = 1 ,15724   ,258,250.3,243.5
XS GIS Cut Line= 3
2101406.12061689195884.696039781     2101278.005      196099.131
     2101176.034      196307.693
#Sta/Elev= 30
       0  1916.2    10.1 1914.22    33.2 1911.58    35.6 1910.98    43.2 1906.81
    62.3 1905.83    66.1  1904.6    76.3 1899.98    92.9 1896.03   165.5 1876.13
   207.5  1870.6   222.8 1870.29   231.8 1868.44   243.31868.028   245.7    1868
   266.11868.159   267.8 1868.36   271.5 1870.49   278.8 1879.06   282.4 1882.36
   289.7 1887.78   315.3 1901.04   339.3 1908.63   350.9 1913.42   361.3 1916.38
     403 1926.71   425.1  1930.8   447.2 1933.83   461.4 1937.82   481.9 1944.53
#Mann= 4 ,-1 , 0
       0     .04       0     100      .1       0   243.3    .045       0
   266.1      .1       0
Bank Sta=243.3,266.1
XS Rating Curve= 0 ,0
Exp/Cntr=0.3,0.1

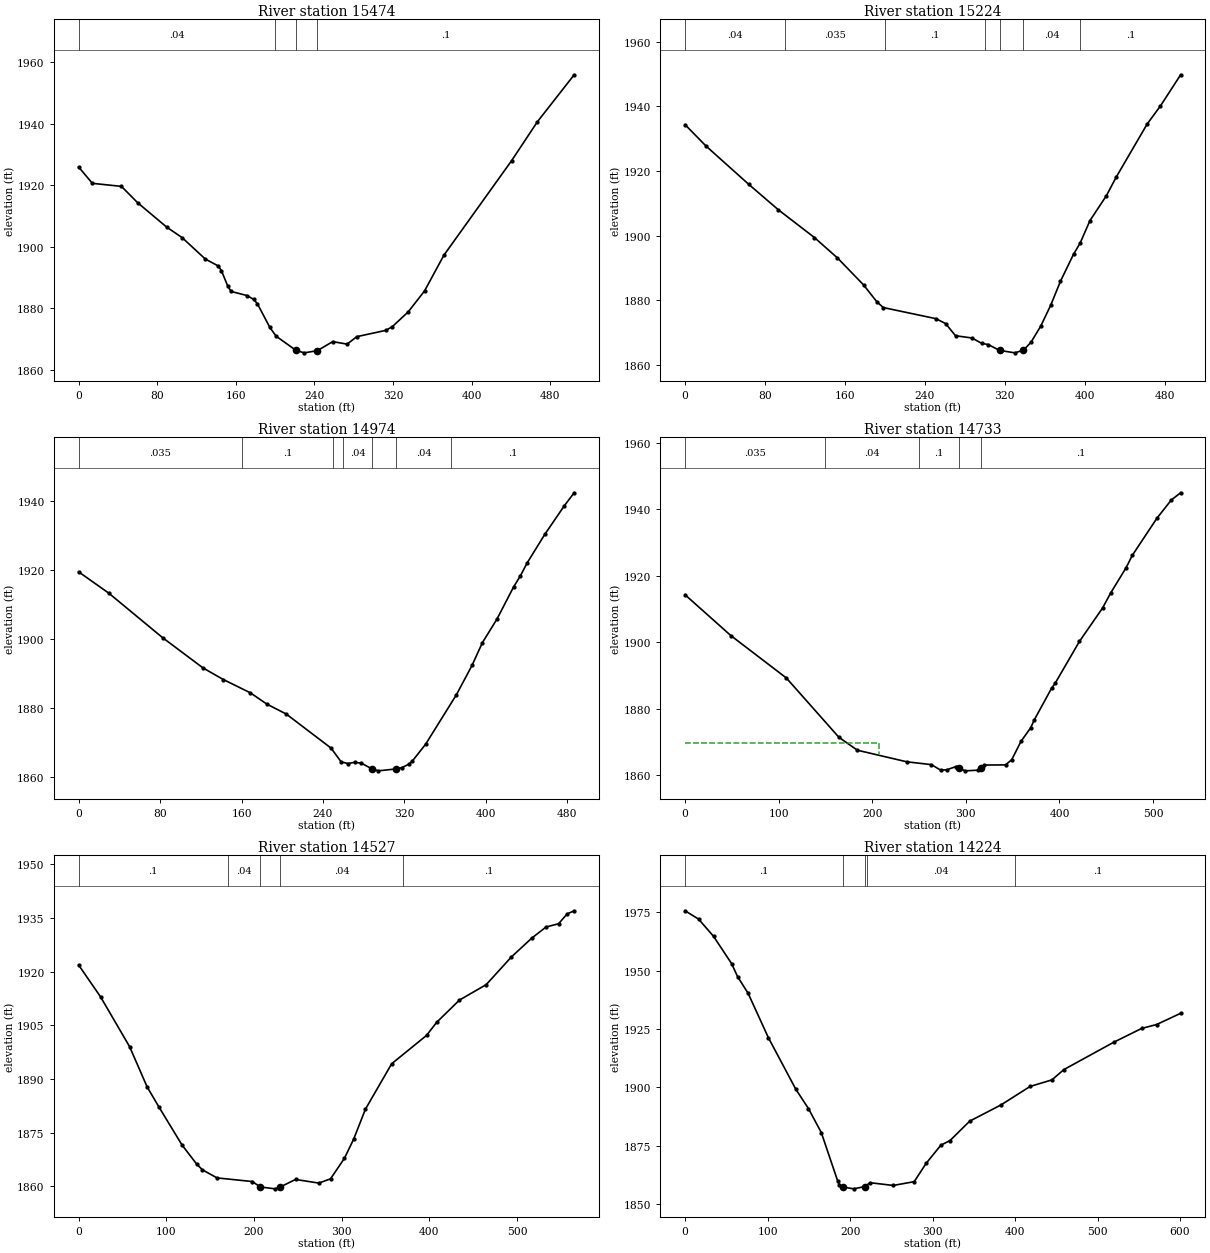
Type RM Length L Ch R = 1 ,15474   ,250.7,250,249.9
XS GIS Cut Line= 3
2101059.09636567195773.220788556     2101052.051      196006.309
     2101046.646      196277.462
#Sta/Elev= 30
       0 1925.88      14 1920.59    43.6  1919.6      60 1914.31    89.5 1906.41
   105.4 1902.95   128.9 1896.02   142.1 1893.77   145.3 1892.25   151.9 1887.15
   155.2 1885.49   171.6 1884.13   178.2 1882.89   181.9 1881.54   194.6 1873.82
     201 1870.96   221.4 1866.32   229.7 1865.55     2431866.255   258.6 1869.19
   273.3 1868.38   283.2 1870.81   312.7 1872.85   319.3 1874.05   335.5 1878.86
   352.1 1885.65   371.8 1897.26   440.7 1927.94   466.9 1940.56   504.4 1955.84
#Mann= 4 ,-1 , 0
       0     .04       0     200      .1       0   221.4    .045       0
     243      .1       0
Bank Sta=221.4,243
XS Rating Curve= 0 ,0
Exp/Cntr=0.3,0.1

Type RM Length L Ch R = 1 ,15224   ,250.9,250,246.9
XS GIS Cut Line= 3
 2100818.6640921195776.043097002     2100830.211      196101.256
     2100835.789      196271.659
#Sta/Elev= 30
       0 1934.31    21.1 1927.66    63.7 1915.86    93.3 1907.99   129.4  1899.4
   152.4 1893.11   178.7 1884.71   191.8 1879.55   198.3 1877.74   250.9 1874.31
   260.7 1872.79   270.6 1869.02     287 1868.33   296.8 1866.67   303.4 1866.28
   314.71864.481     330 1863.73   338.61864.557   346.1 1866.98   355.9 1871.99
   365.8  1878.4   375.6 1885.84   388.7 1894.22   395.3 1897.66   405.2 1904.67
   421.6 1912.34   431.4 1918.08   462.3 1934.47   475.6 1940.07   495.9 1949.75
#Mann= 7 ,-1 , 0
       0     .04       0     100    .035       0     200      .1       0
     300     .04       0   314.7    .045       0   338.6     .04       0
  395.42      .1       0
Bank Sta=314.7,338.6
XS Rating Curve= 0 ,0
Exp/Cntr=0.3,0.1

Type RM Length L Ch R = 1 ,14974   ,238,241.5,245.5
XS GIS Cut Line= 3
     2100543.791      195810.376     2100581.568      196103.792
     2100612.386      196292.164
#Sta/Elev= 30
       0 1919.52    29.6 1913.33    82.5 1900.39   122.2  1891.6   142.1 1888.24
   168.6 1884.38   185.1 1881.06   203.9 1878.22   247.9 1868.32   257.9  1864.3
   264.4 1863.84   271.1 1864.18   277.7 1863.94   287.91862.303   294.3 1861.71
     3121862.269   317.5 1862.63   324.2 1863.63   327.5 1864.46   340.8 1869.44
   370.9 1883.74   386.4 1892.35   396.6 1898.97   410.9 1905.81   427.2 1915.14
   433.9 1918.36   440.5 1922.11   457.9 1930.43   477.1 1938.75   486.7 1942.49
#Mann= 7 ,-1 , 0
       0    .035       0     160      .1       0     250    .035       0
     260     .04       0   287.9    .045       0     312     .04       0
  365.84      .1       0
Bank Sta=287.9,312
XS Rating Curve= 0 ,0
Exp/Cntr=0.3,0.1

Type RM Length L Ch R = 1 ,14733   ,209.6,206,201.6
XS GIS Cut Line= 3
     2100376.871      195827.208        2100340.      196190.011
     2100418.075      196335.182
#Sta/Elev= 30
       0 1914.26    48.9 1901.97   108.2  1889.2   164.3 1871.35   184.1 1867.44
   236.9 1863.95   263.2  1863.1   273.1 1861.44   279.7 1861.55   289.5 1862.53
     2931861.953   299.5 1861.23   312.7 1861.42   315.81861.973   319.3 1862.97
   342.4 1863.02     349 1864.58   358.9  1870.1   369.3 1874.21     373 1876.52
   391.6 1886.12   395.4  1887.6   421.4 1900.23   446.1 1910.29     455 1914.93
   471.1 1922.36     478 1926.21   504.2 1937.34   519.6 1942.84   529.5 1944.99
#Mann= 5 ,-1 , 0
       0    .035       0     150     .04       0     250      .1       0
     293    .045       0   315.8      .1       0
#XS Ineff= 2 , 0
          206.91  1869.6
Permanent Ineff=
       F       F
Bank Sta=293,315.8
XS Rating Curve= 0 ,0
Exp/Cntr=0.3,0.1

Type RM Length L Ch R = 1 ,14527   ,318.8,303,285.4
XS GIS Cut Line= 3
     2100113.372      195903.674     2100174.635      196296.782
      2100311.65      196392.804
#Sta/Elev= 30
       0 1921.85      25 1912.96    58.2    1899    78.1 1887.79    91.8 1882.08
   117.9 1871.55   134.5 1866.25   141.2  1864.6   157.8 1862.35   198.1 1861.33
   207.21859.814   224.2 1859.29     2301859.816   247.4 1861.91     274  1860.9
   287.3 1862.09   303.2 1867.84   313.8 1873.24   327.1 1881.55     357 1894.24
   396.8 1902.17   408.4 1905.84   434.3 1912.04   464.9 1916.37   493.3 1924.03
   516.7 1929.34   533.1 1932.47   547.4 1933.39   557.2 1936.14   565.2 1937.01
#Mann= 5 ,-1 , 0
       0      .1       0     170     .04       0   207.2    .045       0
     230     .04       0     370      .1       0
Bank Sta=207.2,230
XS Rating Curve= 0 ,0
Exp/Cntr=0.3,0.1

Type RM Length L Ch R = 1 ,14224   ,249.9,246.7,240.2
XS GIS Cut Line= 2
2099722.66977112196172.866708994     2100265.769      196429.508
#Sta/Elev= 30
       0 1975.54    16.4 1971.96    34.6 1964.56    56.4 1952.93    63.6 1947.39
    76.4 1940.24     101 1921.24   134.1  1899.3   149.5 1890.98   165.1 1880.71
   184.8 1860.16     187 1858.26   191.71857.377   204.5 1856.64   217.71857.612
   224.2 1859.26   252.3 1858.09   277.7 1859.71   292.2 1867.54     310 1875.29
   321.2 1877.31     345 1885.58   382.9 1892.52   418.2 1900.42   444.6 1903.22
   459.1 1907.62   519.9 1919.38   553.5 1925.24   571.7 1926.91   600.7 1931.71
#Mann= 5 ,-1 , 0
       0      .1       0   191.7    .045       0   217.7      .1       0
     220     .04       0     400      .1       0
Bank Sta=191.7,217.7
XS Rating Curve= 0 ,0
Exp/Cntr=0.3,0.1