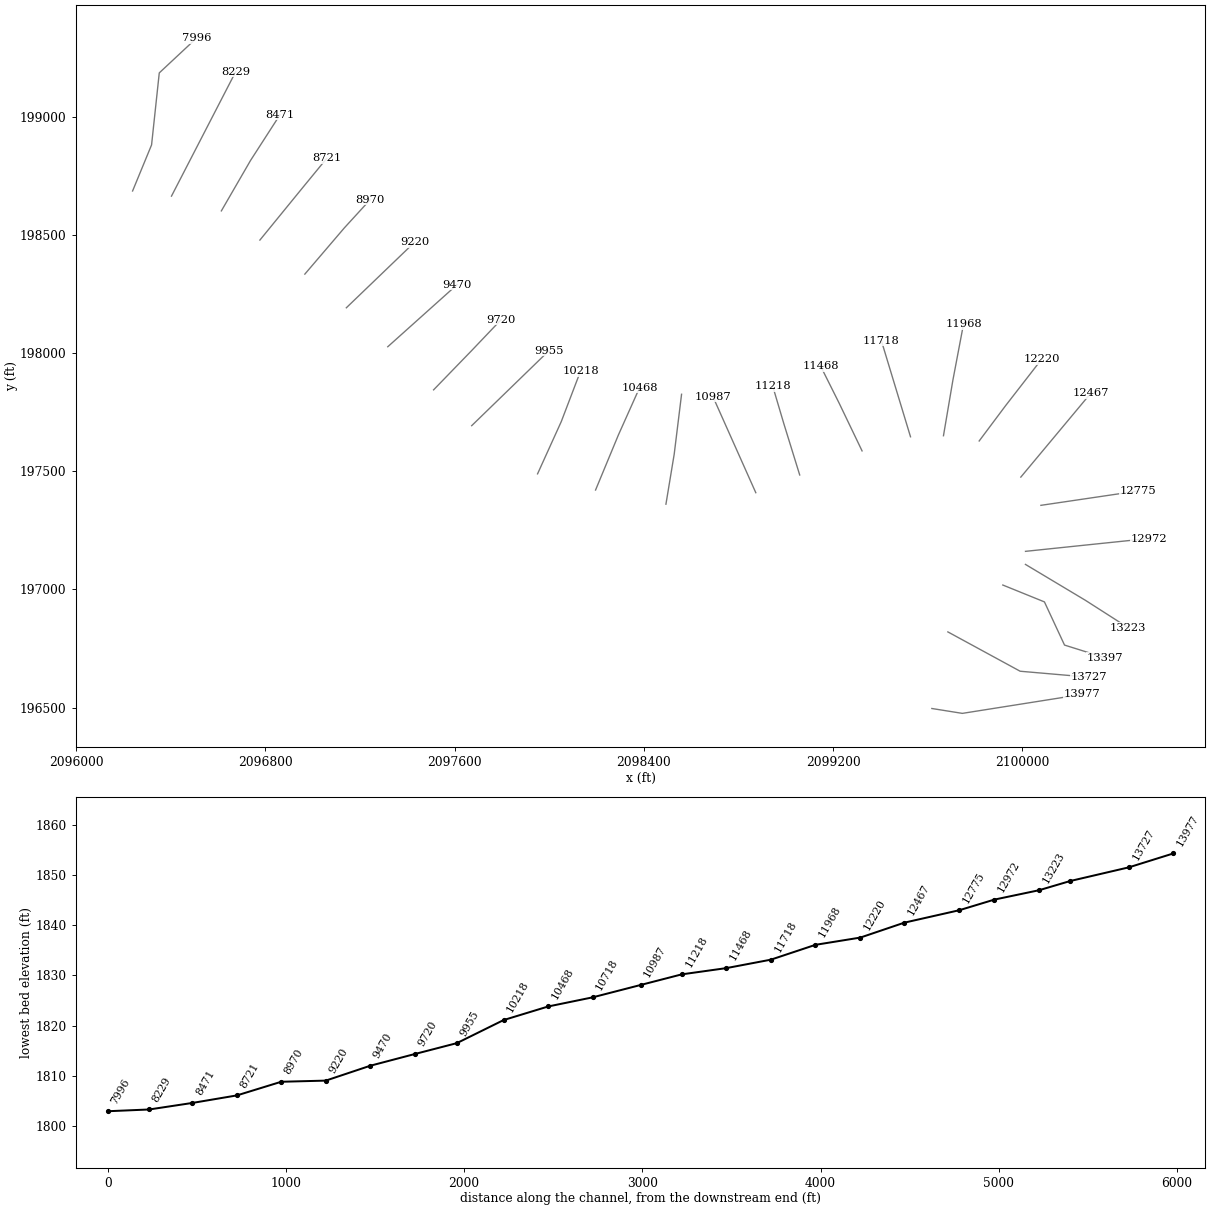
HEC-RAS study TRKYCK.prj: TRKYCK

--- TRKYCK.g01 (geometry) --- (continued)

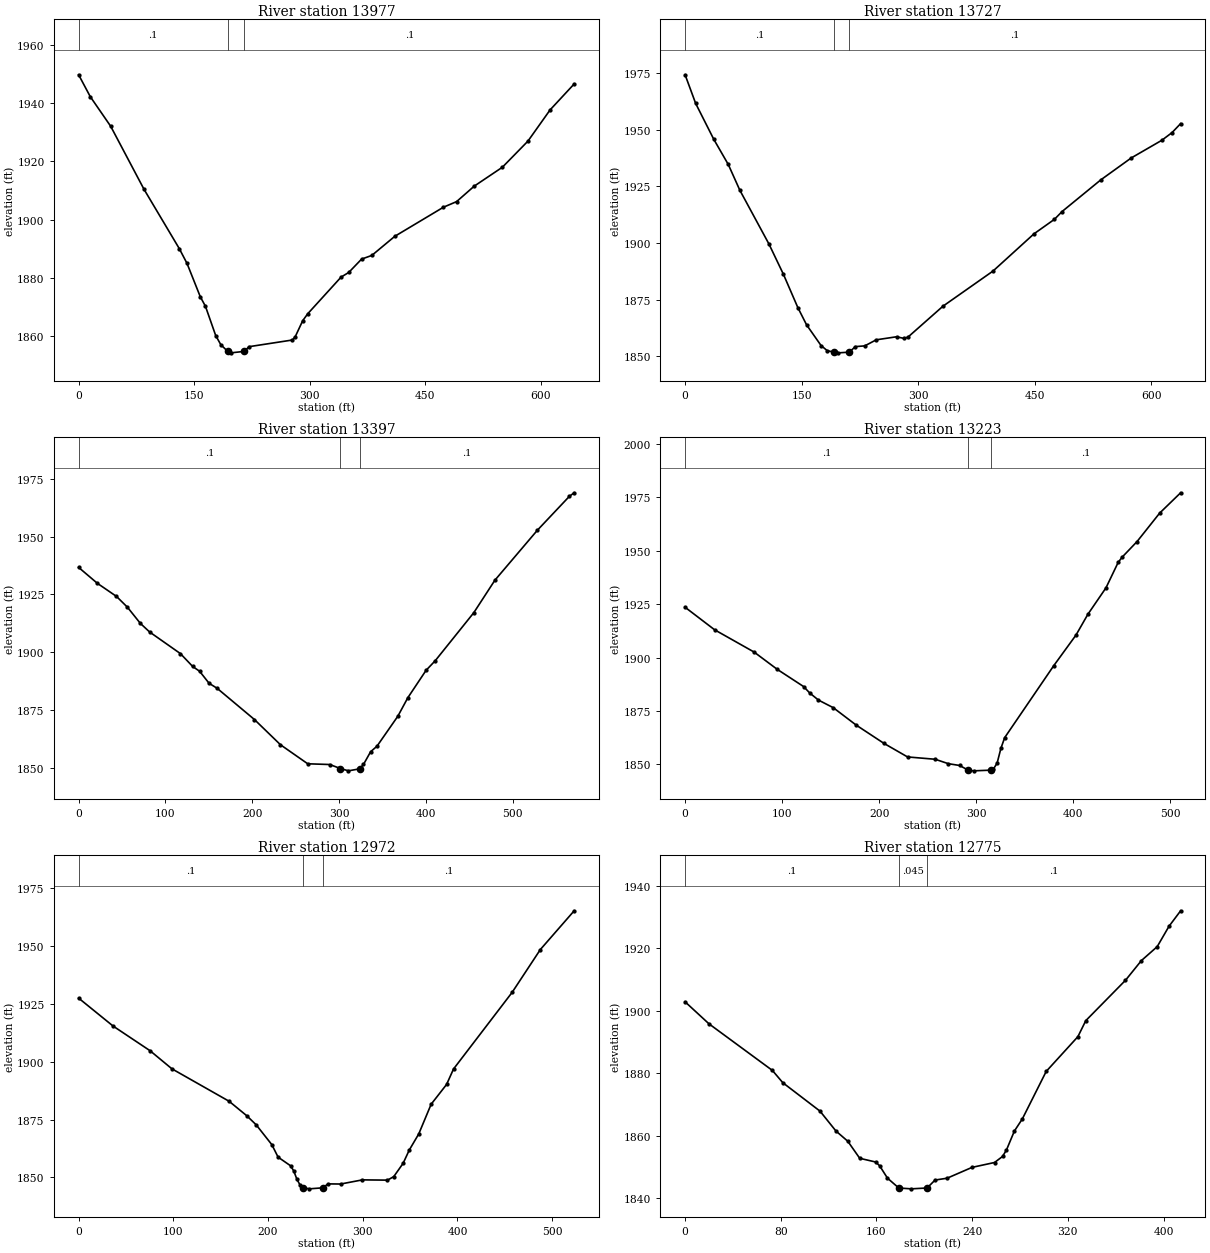
Type RM Length L Ch R = 1 ,13977   ,258,250.1,237.3
XS GIS Cut Line= 3
     2099617.674      196495.9222099746.61485068196475.290885558
      2100252.86       196555.52
#Sta/Elev= 30
       0 1949.79    15.1 1942.28    41.6  1932.1    84.8 1910.47   130.6 1890.08
   140.7 1884.96   157.9 1873.52   164.6 1870.24   177.9 1860.19   184.5 1857.07
   193.31854.797   197.8 1854.26   215.2 1854.77     221 1856.37   277.5 1858.67
   281.2 1859.86   290.8  1865.3   297.4 1867.71   340.6 1880.28   350.6 1881.89
   367.2 1886.46   380.5 1887.73   410.4 1894.31   473.5  1904.3   490.5 1906.21
   513.4 1911.53   549.9 1918.02   583.1    1927   611.9 1937.74   643.1 1946.64
#Mann= 3 ,-1 , 0
       0      .1       0   193.3    .045       0   215.2      .1       0
Bank Sta=193.3,215.2
XS Rating Curve= 0 ,0
Exp/Cntr=0.3,0.1

Type RM Length L Ch R = 1 ,13727   ,339.2,330.3,320.5
XS GIS Cut Line= 3
     2099685.433       196819.94     2099991.042      196653.553
     2100280.027      196628.529
#Sta/Elev= 30
       0 1974.24    13.6 1961.59    36.9 1945.77    55.6 1934.64    70.5 1923.26
   107.9 1899.57   126.6 1886.16   145.2 1871.43   156.4 1863.85   175.1 1854.69
     183 1852.46   191.41851.797   197.5 1851.49   211.41851.787   219.2 1854.24
   231.3 1854.56   246.1 1857.24   272.2 1858.58   282.1 1857.84     287 1858.45
     332 1872.08   396.5 1887.61   449.2 1904.03   475.5 1910.43   485.4 1913.88
   535.2 1927.85   574.3  1937.5   613.8 1945.33     627 1948.74     638 1952.69
#Mann= 3 ,-1 , 0
       0      .1       0   191.4    .045       0   211.4      .1       0
Bank Sta=191.4,211.4
XS Rating Curve= 0 ,0
Exp/Cntr=0.3,0.1

Type RM Length L Ch R = 1 ,13397   ,164.2,173.7,182.7
XS GIS Cut Line= 4
     2099917.665       197018.262100093.58203978196946.911823437
     2100178.542       196764.23     2100349.572      196710.543
#Sta/Elev= 30
       0 1936.69    21.6 1929.81    43.6 1924.15    56.2 1919.48    71.1 1912.49
    81.8 1908.76   117.2 1899.43   131.3 1893.88   139.3  1891.8   150.2 1886.61
   159.5 1884.43   202.4 1870.95   232.4 1860.04   263.8 1851.81   289.2 1851.49
   301.51849.749   310.7 1848.76   323.51849.624     328 1851.52   336.2 1857.01
   343.5 1859.39   367.5 1872.33   379.1 1880.39   400.1 1892.22   410.6 1896.35
   455.1 1917.16   479.3 1931.15   528.3 1952.79   565.2 1967.46   570.6 1968.95
#Mann= 3 ,-1 , 0
       0      .1       0   301.5    .045       0   323.5      .1       0
Bank Sta=301.5,323.5
XS Rating Curve= 0 ,0
Exp/Cntr=0.3,0.1

Type RM Length L Ch R = 1 ,13223   ,240.2,251.4,262.1
XS GIS Cut Line= 3
     2100013.353      197105.504     2100266.563      196953.754
2100447.92369155196837.586691554
#Sta/Elev= 30
       0 1923.52    30.4 1912.98    71.1 1902.55      95 1894.44   122.1  1886.4
   128.5 1883.35   137.4 1880.07   152.7  1876.5   176.3 1868.35     205 1859.77
   229.2 1853.45   257.7 1852.36   271.3 1850.28   282.8 1849.46   291.91847.213
   297.4 1846.94   314.71847.255   317.6 1847.73   321.5 1850.55   325.4 1857.46
   329.3 1862.49   379.9  1896.2   402.8 1910.52     415 1920.22   433.7 1932.64
   446.2  1944.5   450.3 1946.97   465.7 1954.29     489 1967.61   510.6 1977.12
#Mann= 3 ,-1 , 0
       0      .1       0   291.9    .045       0   314.7      .1       0
Bank Sta=291.9,314.7
XS Rating Curve= 0 ,0
Exp/Cntr=0.3,0.1

Type RM Length L Ch R = 1 ,12972   ,196.6,196.7,198.5
XS GIS Cut Line= 3
2100013.62402234197160.772907898     2100261.488      197186.656
  2100534.053903197214.976616892
#Sta/Elev= 30
       0 1927.51    36.4 1915.43    75.4 1904.78    98.5 1896.95   158.9 1882.92
   177.6 1876.64   187.5 1872.73     204 1864.16   210.6 1858.77   223.8 1855.03
   227.1 1852.83   230.4 1849.27   233.7 1846.77   236.81845.577   243.6 1845.07
   257.5  1845.5   263.4 1847.21   276.6 1847.15   299.7 1848.95   326.1 1848.83
   332.7 1850.35   342.6  1856.1   349.1 1861.85   359.1  1868.8   372.2 1881.65
   388.5  1890.2   395.8 1896.86   457.7    1930   487.5 1948.52   523.2 1965.27
#Mann= 3 ,-1 , 0
       0      .1       0   236.8    .045       0   257.5      .1       0
Bank Sta=236.8,257.5
XS Rating Curve= 0 ,0
Exp/Cntr=0.3,0.1

Type RM Length L Ch R = 1 ,12775   ,297.5,308,321
XS GIS Cut Line= 2
     2100078.678      197355.406     2100488.566       197416.01
#Sta/Elev= 30
       0 1902.89      20 1895.83      73  1880.9    81.7 1876.97   112.8 1867.86
   126.1  1861.5     136 1858.22     146 1852.75   159.3 1851.56   162.6 1850.37
   169.2 1846.38   178.71843.222   189.1 1842.96   202.3 1843.23     209 1845.78
     219 1846.36   239.9 1849.84   258.7  1851.4   265.4 1853.34   268.7 1855.43
   275.3 1861.48     282  1865.4   301.9 1880.59   328.4 1891.73     335 1896.86
   368.2  1909.8   381.5 1916.11   394.7 1920.57   404.6 1927.12   414.3 1932.07
#Mann= 3 ,-1 , 0
       0      .1       0   178.7    .045       0   202.3      .1       0
Bank Sta=178.7,202.3
XS Rating Curve= 0 ,0
Exp/Cntr=0.3,0.1

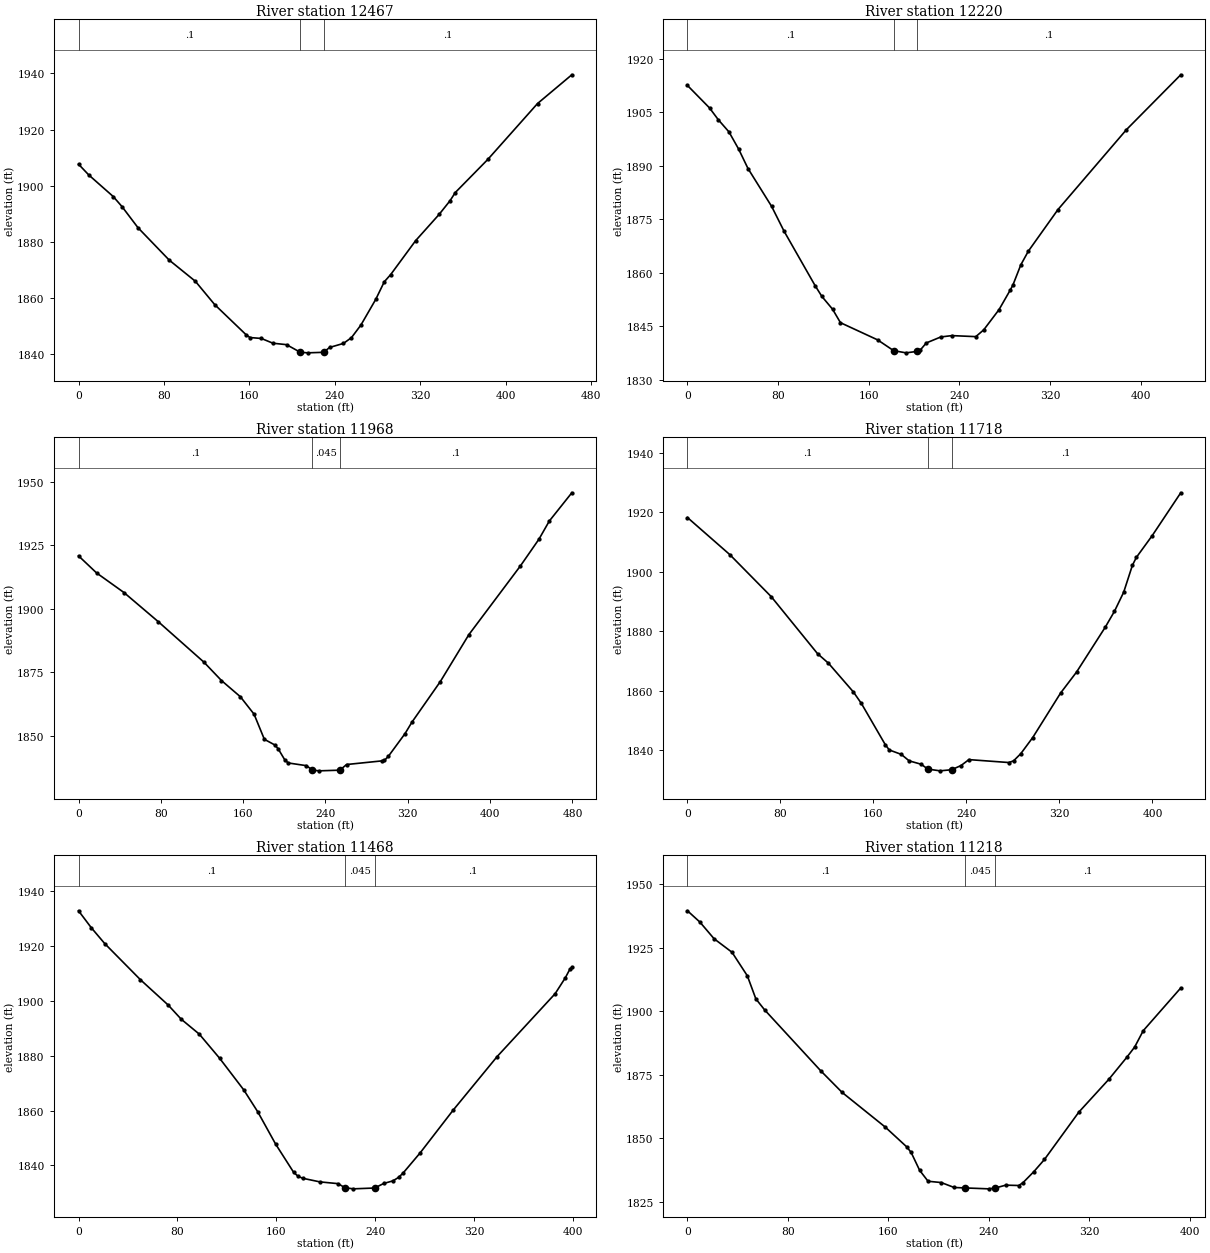
Type RM Length L Ch R = 1 ,12467   ,246.3,247.3,247.5
XS GIS Cut Line= 2
2099993.83732589 197474.88698256     2100289.572      197829.725
#Sta/Elev= 30
       0 1907.68     9.6 1903.84    32.5 1896.16    40.7 1892.58    55.7 1885.05
      85 1873.49   109.4 1865.98   127.5 1857.67   157.2 1846.83   160.6 1845.94
   171.2 1845.61     182 1843.92   194.8  1843.4   207.6  1840.7   214.6 1840.49
   229.4 1840.68   235.1 1842.41   248.1 1843.85   255.6 1845.92   264.4 1850.38
   278.3 1859.53   286.3  1865.8   292.3 1868.37   315.6 1880.42   337.6 1889.77
   347.8 1894.63   352.8 1897.59   383.2 1909.36   429.8 1929.28   461.9 1939.52
#Mann= 3 ,-1 , 0
       0      .1       0   207.6    .045       0   229.4      .1       0
Bank Sta=207.6,229.4
XS Rating Curve= 0 ,0
Exp/Cntr=0.3,0.1

Type RM Length L Ch R = 1 ,12220   ,243.6,251.7,259.7
XS GIS Cut Line= 3
     2099817.735       197627.66     2099929.193      197776.744
     2100081.814      197973.546
#Sta/Elev= 30
       0 1912.47    19.5 1906.16    27.2 1902.87    36.6 1899.46    45.2 1894.61
    53.4 1889.19    74.3 1878.55    85.2 1871.64   112.6 1856.37   118.6 1853.33
     128 1849.76     135 1845.97   167.8 1841.15   181.9 1838.13   192.8 1837.52
   202.9 1837.93   205.3 1838.26   210.7 1840.29   223.5 1841.97   233.3 1842.35
   254.4 1842.06   261.4 1843.97   274.9 1849.64   284.8 1855.13   287.1  1856.5
   294.1 1862.18   300.7    1866   326.9 1877.69   387.3 1900.08   435.2 1915.46
#Mann= 3 ,-1 , 0
       0      .1       0   181.9    .045       0   202.9      .1       0
Bank Sta=181.9,202.9
XS Rating Curve= 0 ,0
Exp/Cntr=0.3,0.1

Type RM Length L Ch R = 1 ,11968   ,241.6,250,258.2
XS GIS Cut Line= 3
     2099666.813      197649.864     2099706.842      197886.067
2099751.48603978 198121.74548011
#Sta/Elev= 30
       0 1920.84    17.6 1914.09    44.2 1906.37    77.5 1894.89   121.9 1878.92
   138.9 1871.69   157.3 1865.29   170.6 1858.42   180.6 1848.51   190.6 1846.32
   193.9 1844.85   200.6  1840.3   203.9 1839.18   221.5 1838.12   227.2 1836.39
   227.2 1836.37   233.9 1836.08   253.9 1836.34   260.5 1838.57   294.7    1840
   297.3 1840.21   301.1  1841.8   317.3 1850.75     324 1855.26   351.6 1871.27
   379.3 1889.75   429.5 1916.91   447.5 1927.44   457.5 1934.56   479.4 1945.71
#Mann= 3 ,-1 , 0
       0      .1       0   227.2    .045       0   253.9      .1       0
Bank Sta=227.2,253.9
XS Rating Curve= 0 ,0
Exp/Cntr=0.3,0.1

Type RM Length L Ch R = 1 ,11718   ,247.8,250,253.6
XS GIS Cut Line= 3
     2099527.473      197645.425     2099463.447      197856.713
     2099404.434      198051.459
#Sta/Elev= 30
       0 1918.18    36.4 1905.74    72.1  1891.6   111.9 1872.47   121.3 1869.26
   142.7 1859.63   149.6 1855.76   170.1 1841.96   173.6 1840.14   183.9 1838.66
   190.7 1836.48     201 1835.35   206.8 1833.71   217.3 1833.13   227.2  1833.5
   235.3 1834.91   242.1  1836.9   276.4 1835.92   280.5 1836.48   286.7 1838.89
     297 1844.32     321 1859.28   334.7 1866.31   359.4 1881.38   367.3 1886.71
   375.2 1893.09   382.7 1902.12   386.1 1904.78   399.8 1912.13   424.3 1926.49
#Mann= 3 ,-1 , 0
       0      .1       0   206.8    .045       0   227.2      .1       0
Bank Sta=206.8,227.2
XS Rating Curve= 0 ,0
Exp/Cntr=0.3,0.1

Type RM Length L Ch R = 1 ,11468   ,252,250,246.4
XS GIS Cut Line= 3
     2099322.691      197585.697     2099225.215      197788.811
     2099147.466       197944.31
#Sta/Elev= 30
       0 1932.79    10.3 1926.63    21.2 1920.84    50.1 1907.66    72.5 1898.45
    83.1 1893.27    97.7 1887.84   114.1 1879.07   133.7  1867.5     145 1859.53
   159.5 1847.73   174.1 1837.43   177.7    1836   181.4  1835.3   195.2 1833.99
     210 1833.34   215.51831.871   222.3 1831.45   239.51831.747     247 1833.42
   254.4 1834.36     259 1835.64   262.6 1837.21   276.4 1844.56     303 1860.08
   338.7 1879.67   385.6 1902.57   393.8 1908.34   397.4 1911.39   399.1 1912.18
#Mann= 3 ,-1 , 0
       0      .1       0   215.5    .045       0   239.5      .1       0
Bank Sta=215.5,239.5
XS Rating Curve= 0 ,0
Exp/Cntr=0.3,0.1

Type RM Length L Ch R = 1 ,11218   ,229.6,230.6,233.9
XS GIS Cut Line= 3
     2099059.048      197483.835     2098991.808      197701.381
     2098944.897      197859.844
#Sta/Elev= 30
       0 1939.47     9.9 1935.04    21.2 1928.49    35.5 1923.17    47.7 1913.93
    54.5 1904.86    61.4 1900.58     106 1876.69   123.2 1868.11   157.6 1854.47
   174.7  1846.7   178.2 1844.52     185 1837.47   191.7 1833.19   202.2 1832.68
   212.5 1830.74   221.21830.565   239.9 1830.21     245 1830.51   253.6 1831.66
   263.9 1831.52   267.3 1832.62     276 1836.98   284.4 1841.74   311.8 1860.35
   335.7 1873.24   349.9 1881.82   356.3 1885.94   363.1 1892.34     393 1909.14
#Mann= 3 ,-1 , 0
       0      .1       0   221.2    .045       0     245      .1       0
Bank Sta=221.2,245
XS Rating Curve= 0 ,0
Exp/Cntr=0.3,0.1

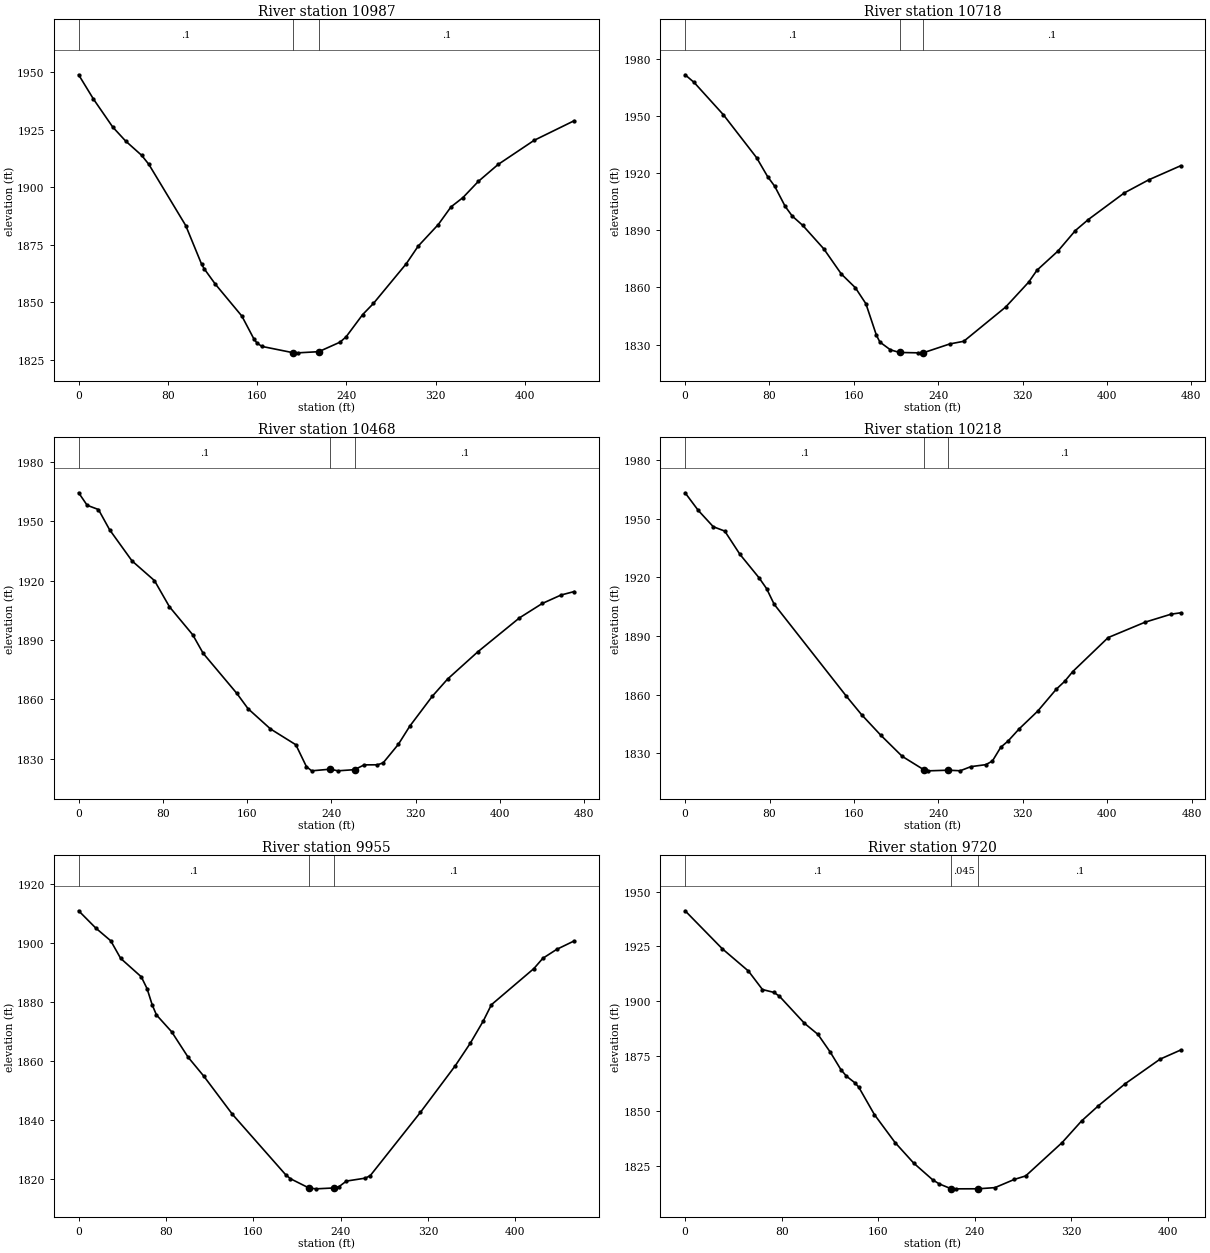
Type RM Length L Ch R = 1 ,10987   ,279.1,269.4,260.7
XS GIS Cut Line= 2
     2098873.405      197408.926      2098692.48      197814.553
#Sta/Elev= 30
       0 1948.88    13.3 1938.32    30.6 1926.15    42.1 1920.11    56.5 1913.88
    62.9 1909.99      96 1883.37   110.3 1866.48   112.6 1864.57   122.5 1857.94
   146.3 1844.06     157 1834.21   159.8 1832.38   164.2  1830.9   192.1 1828.16
   196.6  1828.1   215.21828.603   234.3 1832.75   239.7 1835.05   254.6 1844.75
   264.2 1849.55   293.6 1866.79   304.3 1874.45   322.3 1883.82   333.7 1891.49
   344.4 1895.53   358.2 1902.56   375.9 1909.91   408.2  1920.4   444.1 1928.92
#Mann= 3 ,-1 , 0
       0      .1       0   192.1    .045       0   215.2      .1       0
Bank Sta=192.1,215.2
XS Rating Curve= 0 ,0
Exp/Cntr=0.3,0.1

Type RM Length L Ch R = 1 ,10718   ,253.7,250,245.1
XS GIS Cut Line= 3
     2098493.573       197360.26     2098528.541      197572.058
     2098559.657      197825.296
#Sta/Elev= 30
       0 1971.64     8.5 1967.65    36.3 1950.65    67.7 1928.18    78.3 1918.12
      85 1913.08    94.9 1902.52   101.6 1897.45   111.6 1892.52   131.5 1880.23
   148.1 1867.04   161.4 1859.84   171.4 1851.44   181.4 1834.85   184.7 1831.28
   194.7  1827.2   203.31825.837   221.2 1825.64     2261825.707     251 1830.32
   264.2 1831.71   303.9 1849.68   325.8 1862.81   333.6 1869.02   353.5 1879.09
     370 1889.85   382.3 1895.64   416.3 1909.58   439.4 1916.44   469.8 1923.87
#Mann= 3 ,-1 , 0
       0      .1       0   203.3    .045       0     226      .1       0
Bank Sta=203.3,226
XS Rating Curve= 0 ,0
Exp/Cntr=0.3,0.1

Type RM Length L Ch R = 1 ,10468   ,251,250,251.2
XS GIS Cut Line= 3
     2098196.087      197420.191     2098292.602      197653.094
     2098381.805      197852.368
#Sta/Elev= 30
       0 1964.35     8.1 1958.03    18.8 1955.89    29.4 1945.67    50.7 1929.91
      72 1919.96    86.2 1906.75   108.3 1892.59   118.2 1883.23   150.2 1862.95
   160.8 1855.24   182.1    1845   206.2    1837   216.2 1825.98   221.2 1823.82
     239 1824.67     246 1823.83   261.91824.411   271.1 1826.84   283.7 1826.87
   289.1 1827.87   303.5 1837.22   314.3 1846.36   335.7  1861.5   350.2 1870.19
     379 1884.01   418.5 1901.14   440.1  1908.4     458 1912.69   470.4 1914.42
#Mann= 3 ,-1 , 0
       0      .1       0     239    .045       0   261.9      .1       0
Bank Sta=239,261.9
XS Rating Curve= 0 ,0
Exp/Cntr=0.3,0.1

Type RM Length L Ch R = 1 ,10218   ,268.6,262.6,255.9
XS GIS Cut Line= 3
       2097950.9      197488.616     2098051.234      197709.953
     2098131.973      197921.638
#Sta/Elev= 30
       0 1963.26    12.4  1954.3    26.7 1945.91    37.6 1943.67      52 1931.77
      70 1919.85    77.2  1914.3    84.4 1906.28   152.8 1859.29   167.2 1849.86
   185.2 1839.46   205.7 1828.55   226.81821.484   230.5 1821.12   249.51821.445
   260.7 1821.16   270.8 1823.26     285 1824.28   291.2 1826.12   299.1 1833.14
   306.1 1836.38   316.6 1842.58   334.2 1851.67   351.7 1862.82   359.8 1866.92
   367.4 1871.88   400.9 1889.24     436 1897.13   460.6 1901.21   469.6  1901.9
#Mann= 3 ,-1 , 0
       0      .1       0   226.8    .045       0   249.5      .1       0
Bank Sta=226.8,249.5
XS Rating Curve= 0 ,0
Exp/Cntr=0.3,0.1

Type RM Length L Ch R = 1 ,9955    ,232.3,235.4,233.6
XS GIS Cut Line= 2
      2097672.49       197692.42     2097998.058      198008.645
#Sta/Elev= 30
       0 1910.99    15.7 1905.12    29.4  1900.8    38.5 1894.82    57.4 1888.55
    62.7 1884.53    67.4 1879.01    71.3  1875.6    85.2 1869.89   100.3 1861.24
   114.5 1854.88   140.9 1841.83   189.6 1821.34     194 1819.97     2111816.814
   217.5 1816.53   233.71816.828   238.4 1817.25   245.3 1819.17   262.7 1820.17
   267.2 1821.05     313 1842.49   345.1 1858.41   358.7 1865.98   370.6 1873.52
   378.1 1879.08     417 1891.36   425.2 1894.85   437.9 1897.88   453.9 1900.75
#Mann= 3 ,-1 , 0
       0      .1       0     211    .045       0   233.7      .1       0
Bank Sta=211,233.7
XS Rating Curve= 0 ,0
Exp/Cntr=0.3,0.1

Type RM Length L Ch R = 1 ,9720    ,251,250,248.6
XS GIS Cut Line= 3
     2097511.427      197843.982      2097672.43      198010.246
      2097795.96      198139.952
#Sta/Elev= 30
       0 1941.23    30.7 1923.96    52.5 1913.72    64.1  1905.3    73.6 1903.99
    78.1 1902.28    98.9  1889.9   110.1 1884.82   120.4 1876.65   129.1 1868.75
   133.7 1865.77   140.7 1862.74   143.9 1860.75   156.9 1848.21     174 1835.48
   189.4 1826.12   205.2 1818.46   210.6 1816.62     2201814.505   224.1 1814.37
   242.91814.393   256.7 1814.92   272.9 1818.69   282.2 1820.26   312.4 1835.48
   328.5 1845.33   342.5 1852.29   364.8 1862.38   393.6 1873.55   410.6 1877.69
#Mann= 3 ,-1 , 0
       0      .1       0     220    .045       0   242.9      .1       0
Bank Sta=220,242.9
XS Rating Curve= 0 ,0
Exp/Cntr=0.3,0.1

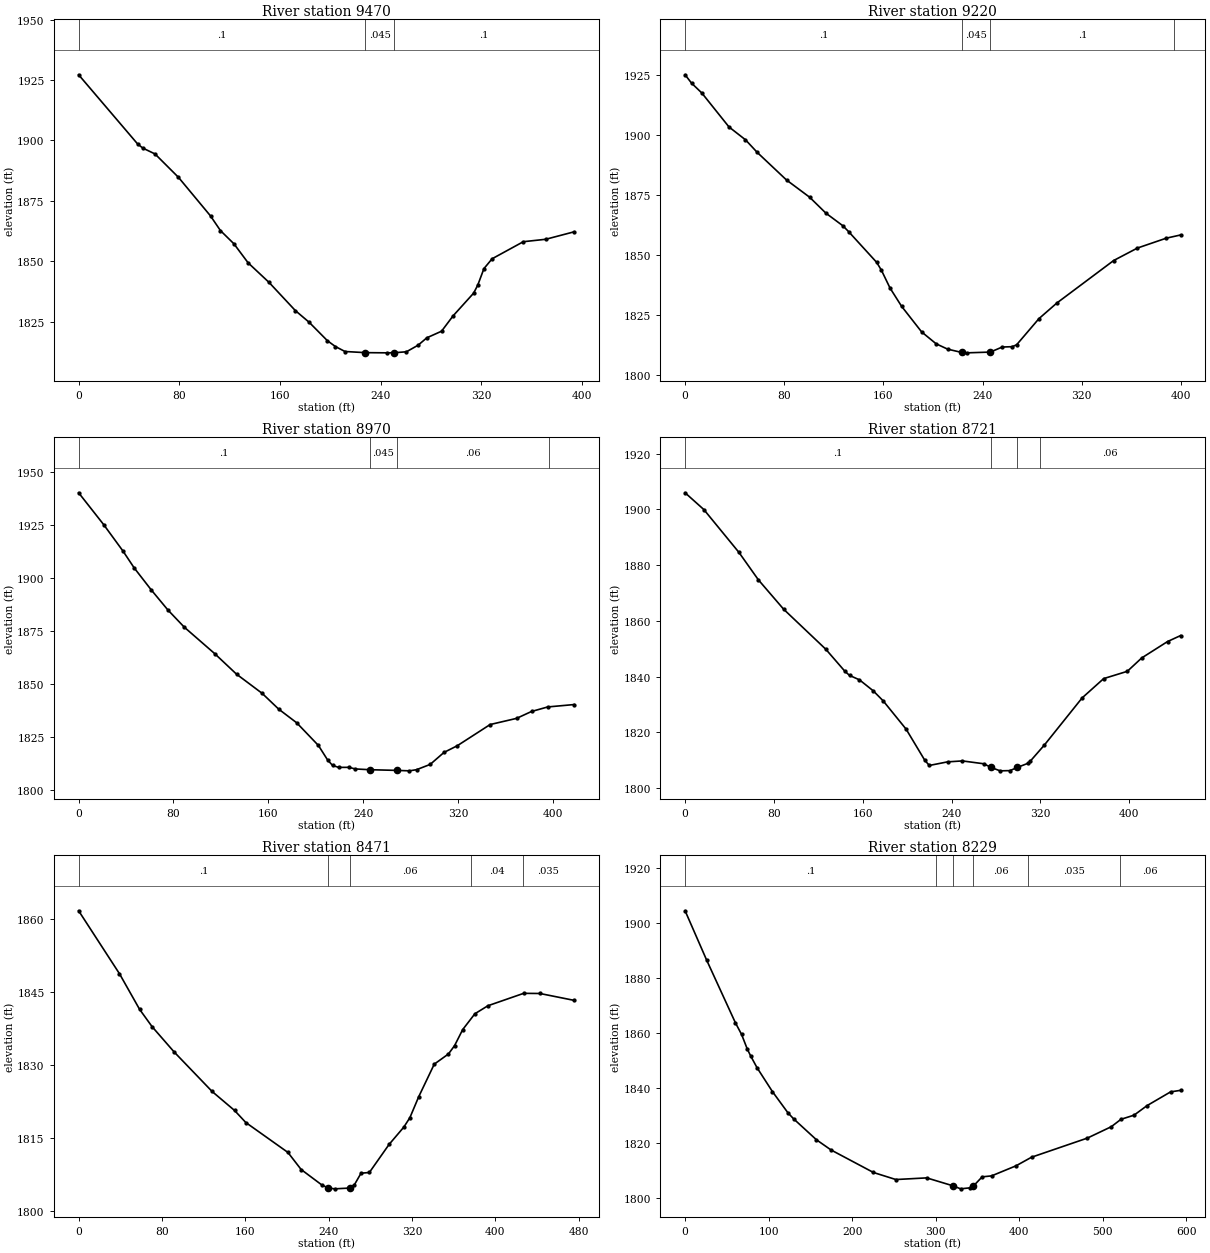
Type RM Length L Ch R = 1 ,9470    ,249.2,250,250.3
XS GIS Cut Line= 3
     2097317.674      198026.306     2097495.851       198186.05
     2097610.863      198289.164
#Sta/Elev= 30
       0 1927.13    46.9 1898.48      51 1896.79    60.7 1894.36    79.3  1884.7
   104.8 1868.71   112.7 1862.64   123.4 1857.18   134.7 1849.29   151.3  1841.2
   172.2 1829.54   183.2 1824.69   197.7 1817.06   204.1 1814.63   211.7 1812.59
   227.81812.123   244.9 1812.04   250.81812.083   260.5 1812.48   269.8 1815.21
   276.7 1818.26   288.4 1820.99   297.6 1827.36   313.9 1836.75   317.2 1840.09
   322.1 1846.91   328.6 1850.98   353.4 1858.04   371.2 1859.04   393.8 1862.14
#Mann= 3 ,-1 , 0
       0      .1       0   227.8    .045       0   250.8      .1       0
Bank Sta=227.8,250.8
XS Rating Curve= 0 ,0
Exp/Cntr=0.3,0.1

Type RM Length L Ch R = 1 ,9220    ,248.3,250,251
XS GIS Cut Line= 3
     2097142.515      198191.132     2097311.673      198353.782
     2097430.666      198468.198
#Sta/Elev= 30
       0  1924.9     5.2 1921.42    13.5 1917.31    35.4 1903.17    48.7 1897.82
    58.2 1892.56    81.8 1881.07   100.4 1873.92   113.6 1867.25   127.3 1861.99
   131.8 1859.62   154.6 1846.72   158.4 1843.43   165.3 1836.07   174.6 1828.48
   190.8 1817.79   202.5 1812.84   211.8 1810.61   223.21809.234   227.4 1809.08
   246.21809.394   255.8  1811.5   263.8 1811.64   267.4 1812.43   285.4 1823.32
   299.9 1829.85   345.7 1847.54   364.9 1852.74   388.1 1856.84   399.7 1858.18
#Mann= 4 ,-1 , 0
       0      .1       0   223.2    .045       0   246.2      .1       0
  394.67    .035       0
Bank Sta=223.2,246.2
XS Rating Curve= 0 ,0
Exp/Cntr=0.3,0.1

Type RM Length L Ch R = 1 ,8970    ,247.2,248.5,248.7
XS GIS Cut Line= 3
     2096967.141      198333.579     2097134.148      198529.149
     2097242.739      198647.877
#Sta/Elev= 30
       0 1939.97    21.1 1924.98    37.5 1912.43    46.9 1904.52    61.2 1894.22
    75.2 1884.78    89.1 1876.62   114.7 1864.17   133.2 1854.45   154.8 1845.41
   168.8 1837.95     184  1831.5   202.3 1820.82   210.1 1813.95   214.3 1811.37
   219.4 1810.48   228.1  1810.5   233.4 1809.74   245.61809.389   268.71809.054
   279.1 1808.85   285.1 1809.39   296.6 1811.88   308.3 1817.55   319.4 1820.66
   347.2 1830.68   369.5 1833.59   382.1 1836.84   395.8 1838.98   418.1 1840.11
#Mann= 4 ,-1 , 0
       0      .1       0   245.6    .045       0   268.7     .06       0
  397.17    .035       0
Bank Sta=245.6,268.7
XS Rating Curve= 0 ,0
Exp/Cntr=0.3,0.1

Type RM Length L Ch R = 1 ,8721    ,246.3,250,251
XS GIS Cut Line= 3
     2096777.124      198477.582     2096960.032        198701.9
     2097059.487      198823.087
#Sta/Elev= 30
       0 1905.96    16.9 1899.93    48.5 1884.55      66  1874.7    88.8 1864.13
   126.7 1849.79   143.9 1841.87   148.1 1840.39     157 1838.81   169.3  1834.9
   178.3 1831.29     199 1821.11   215.8 1809.95   219.9 1808.07   236.3 1809.36
   249.7  1809.7   268.9 1808.68   275.31807.405   283.6 1806.14   292.5 1806.22
   299.2 1807.37     309 1808.89   310.9 1809.65   323.5  1815.4   357.5 1832.32
   376.9 1839.25   398.2 1841.87   411.1 1846.65   434.4 1852.55   446.2 1854.71
#Mann= 4 ,-1 , 0
       0      .1       0   275.3    .045       0   299.2      .1       0
  319.44     .06       0
Bank Sta=275.3,299.2
XS Rating Curve= 0 ,0
Exp/Cntr=0.3,0.1

Type RM Length L Ch R = 1 ,8471    ,239.7,242.5,242.4
XS GIS Cut Line= 3
     2096614.216      198601.042     2096737.469      198814.246
2096861.74167411 199007.16548011
#Sta/Elev= 30
       0 1861.59    39.2  1848.7    58.5 1841.41    70.5 1837.86    91.7 1832.67
   128.1 1824.59   149.7 1820.69   160.5 1818.22   200.9  1812.1   213.6  1808.6
   233.8 1805.38   239.81804.812   245.8 1804.64   260.3  1804.8   264.8  1805.5
   271.1 1807.84   279.1 1807.99     298 1813.73   312.2 1817.29     318 1819.22
   326.5 1823.52   341.4 1830.18     355 1832.26   360.9 1833.97   368.7 1837.26
   380.4  1840.5   392.9 1842.14   427.2 1844.68   442.8 1844.65   475.7 1843.24
#Mann= 5 ,-1 , 0
       0      .1       0   239.8    .045       0   260.3     .06       0
  376.27     .04       0  426.27    .035       0
Bank Sta=239.8,260.3
XS Rating Curve= 0 ,0
Exp/Cntr=0.3,0.1

Type RM Length L Ch R = 1 ,8229    ,225.4,232.5,237.9
XS GIS Cut Line= 2
     2096403.381      198663.532     2096675.179      199190.529
#Sta/Elev= 30
       0 1904.36    25.7  1886.5    60.2 1863.67    67.6 1859.43    74.4 1854.13
    78.7 1851.49      86 1847.39   104.5 1838.67   123.1 1830.95     130 1828.73
   157.2 1821.16   174.6 1817.47   225.4 1809.28   252.2 1806.72   289.1 1807.32
     321  1804.4   329.7 1803.34   340.8  1803.7     3451804.367   355.5  1807.7
   366.7 1808.04   395.9 1811.69   414.6 1814.83   481.4 1821.78     510 1825.91
   521.6  1828.6   537.2  1830.1   552.9 1833.59     581 1838.57     593 1839.13
#Mann= 6 ,-1 , 0
       0      .1       0     300     .06       0     321    .045       0
     345     .06       0     410    .035       0     520     .06       0
Bank Sta=321,345
XS Rating Curve= 0 ,0
Exp/Cntr=0.3,0.1

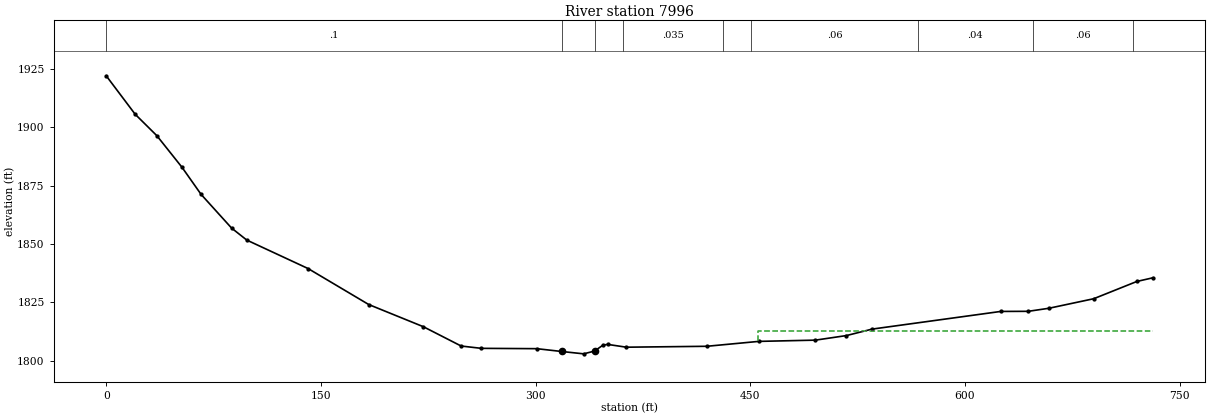
Type RM Length L Ch R = 1 ,7996    ,571,558.8,547.2
XS GIS Cut Line= 4
     2096238.918      198685.227     2096319.167      198880.115
     2096351.719      199184.803     2096508.221      199331.024
#Sta/Elev= 30
       0 1921.94    20.2 1905.51    35.4  1896.3      53 1882.76    66.3  1871.2
    87.6 1856.79    98.2 1851.66   141.1 1839.46   183.4 1824.09   221.6 1814.59
     248 1806.33   262.1 1805.34   300.8  1805.2   318.21803.998   333.6 1802.99
   341.21804.186     347 1806.69   350.3 1807.03   363.4 1805.83   419.6 1806.22
     456 1808.32   495.5 1808.85   517.2 1810.81   535.1 1813.57     625 1821.13
   644.2 1821.18   658.6 1822.48   689.9 1826.56   720.1 1833.96   731.4 1835.54
#Mann= 9 ,-1 , 0
       0      .1       0   318.2    .045       0   341.2      .1       0
  360.76    .035       0  430.76     .08       0  450.76     .06       0
  567.19     .04       0  647.19     .06       0  717.19    .035       0
#XS Ineff= 2 , 0
                          455.47         1812.67
Permanent Ineff=
       F       F
Bank Sta=318.2,341.2
XS Rating Curve= 0 ,0
Exp/Cntr=0.3,0.1