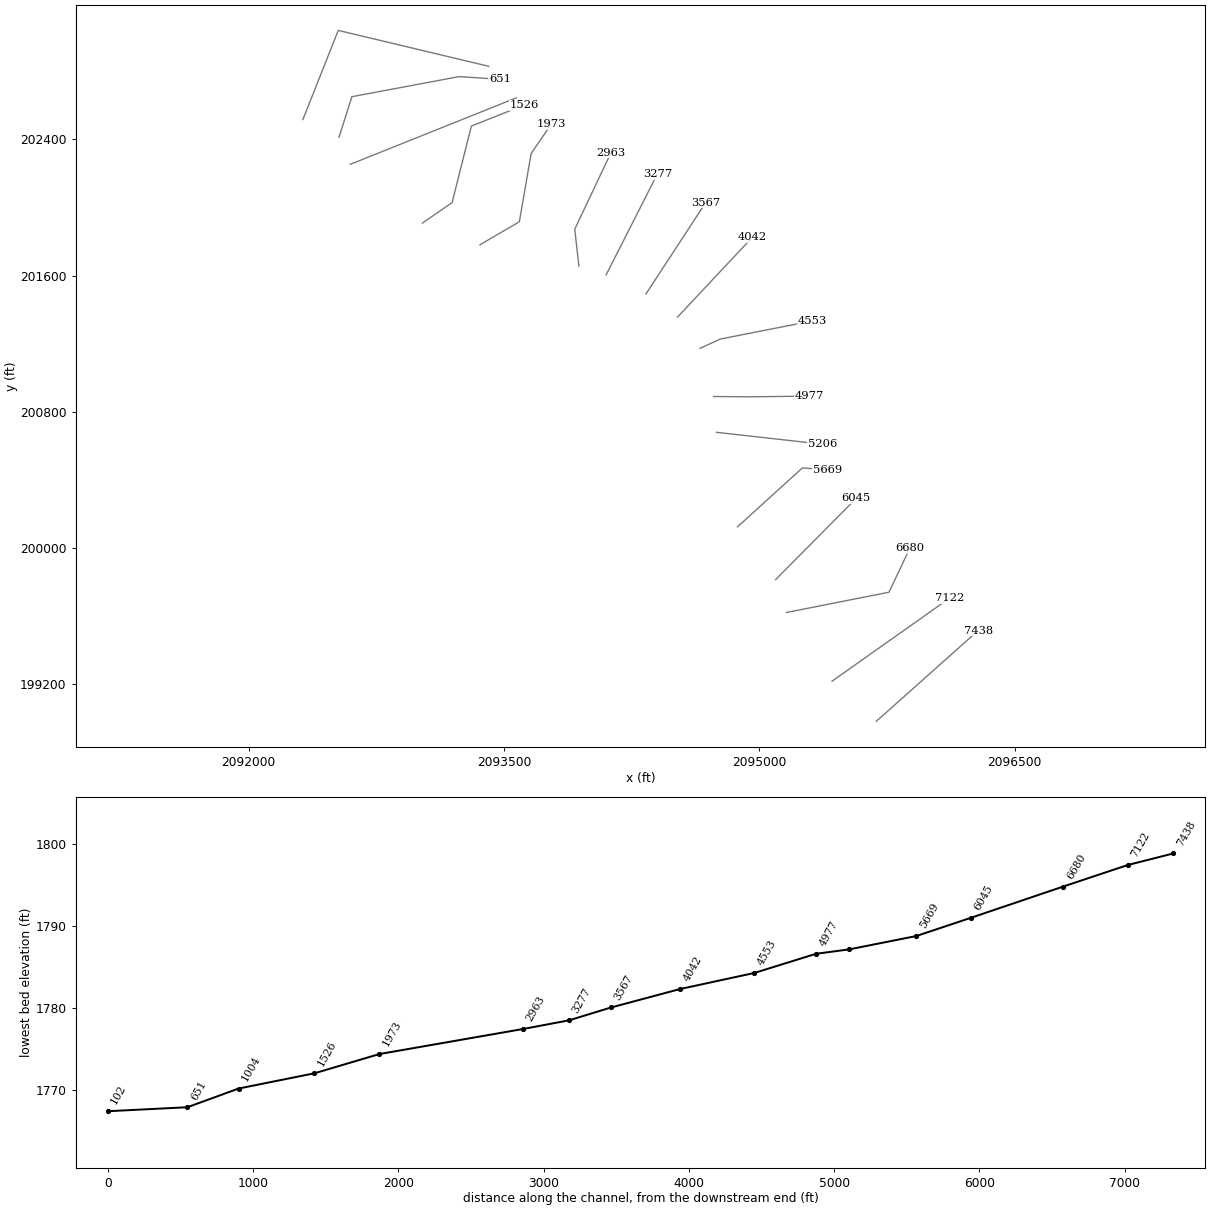
HEC-RAS study TRKYCK.prj: TRKYCK

--- TRKYCK.g01 (geometry) --- (continued)

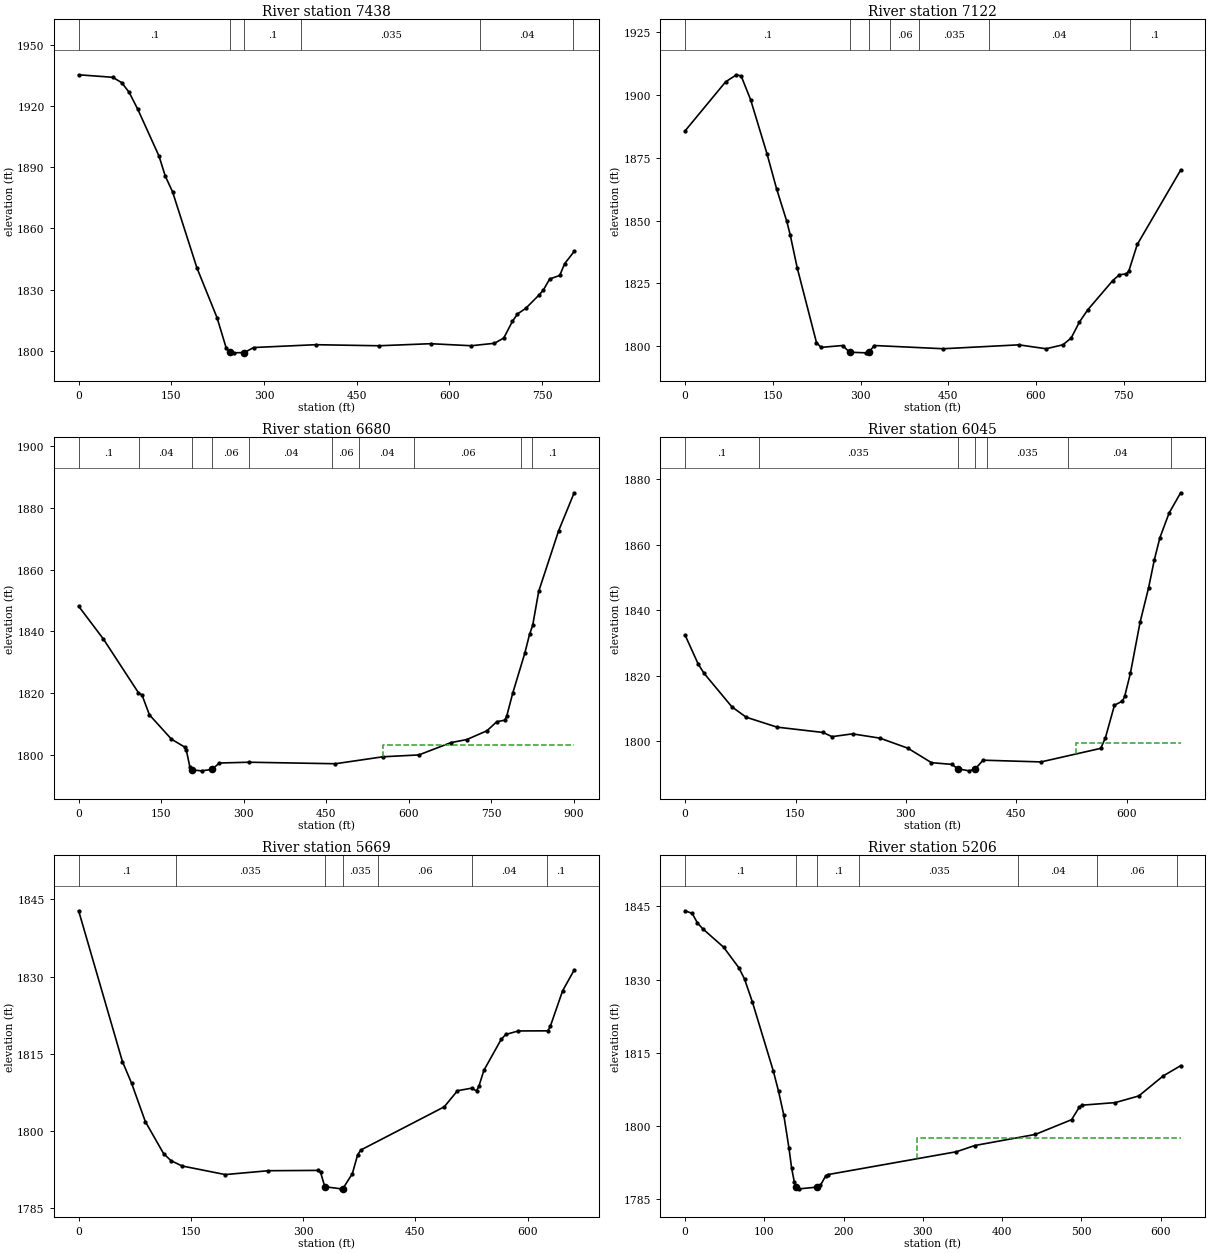
Type RM Length L Ch R = 1 ,7438    ,318.4,315.2,313.5
XS GIS Cut Line= 2
     2095687.121      198981.446     2096285.701       199514.76
#Sta/Elev= 30
       0 1935.56    55.2 1934.32    69.7 1931.69    81.6 1926.99    95.7  1918.6
   130.1 1895.56   140.1  1885.8   151.9 1878.06   191.4 1840.62     224 1816.08
   238.8 1801.19   245.41799.069   250.9 1798.87   268.3 1799.03   283.1 1801.48
   383.4 1802.87   485.9 1802.35   569.3 1803.36   635.3 1802.36   672.8 1803.57
   687.8 1806.16   701.7  1814.3     710 1817.99   723.1 1820.67   745.1 1827.38
   751.7 1829.67   762.1 1835.19   778.4 1836.92   786.2 1842.67   801.7 1848.73
#Mann= 6 ,-1 , 0
       0      .1       0   245.4    .045       0   268.3      .1       0
     360    .035       0     650     .04       0     800      .1       0
Bank Sta=245.4,268.3
XS Rating Curve= 0 ,0
Exp/Cntr=0.3,0.1

Type RM Length L Ch R = 1 ,7122    ,440.6,442.8,419.1
XS GIS Cut Line= 2
 2095426.9290887199217.1111592752096119.08834979199706.056610874
#Sta/Elev= 30
       0 1885.64    69.3 1905.12    87.9 1907.92    95.9 1907.43     112 1898.04
     140 1876.58   156.4 1862.66   173.9 1849.67   179.6 1844.46   191.7 1831.24
   224.7  1801.5   232.5 1799.62   269.4 1800.36   281.2  1797.7   309.4 1797.45
     3141797.638   323.6 1800.36   441.4 1799.08   570.7 1800.63   617.4 1799.07
   646.1 1800.65   660.2 1803.34   674.3 1809.68   688.4  1814.5   731.1  1826.1
   742.5 1828.46   754.3 1828.83   758.7 1829.89   773.2  1840.5   847.4 1870.04
#Mann= 7 ,-1 , 0
       0      .1       0   281.2    .045       0     314      .1       0
     350     .06       0     400    .035       0     520     .04       0
     760      .1       0
Bank Sta=281.2,314
XS Rating Curve= 0 ,0
Exp/Cntr=0.3,0.1

Type RM Length L Ch R = 1 ,6680    ,616.6,634.6,616.5
XS GIS Cut Line= 3
     2095159.196      199620.799     2095761.658      199739.924
      2095884.46      199999.073
#Sta/Elev= 30
       0 1848.19    45.1 1837.53   108.6 1820.18   115.3 1819.38   128.7 1812.98
   168.8 1805.09   192.7 1802.55   195.6  1801.7   202.3 1796.01   205.81795.123
   223.4 1794.83   242.4 1795.28   255.8 1797.37     310 1797.62   466.7 1797.13
   553.4 1799.39   618.6 1799.99   676.7 1803.97   705.7 1804.97   742.4 1807.82
   760.2 1810.76   774.7 1811.24   778.3  1812.6   789.2 1820.01     811 1832.87
   819.8 1839.08   825.5 1841.99   836.4    1853   872.7 1872.67   900.9 1884.95
#Mann= 10 ,-1 , 0
       0      .1       0     110     .04       0   205.8    .045       0
   242.4     .06       0     310     .04       0     460     .06       0
     510     .04       0     610     .06       0  804.13     .04       0
  824.13      .1       0
#XS Ineff= 2 , 0
                          552.78         1803.33
Permanent Ineff=
       F       F
Bank Sta=205.8,242.4
XS Rating Curve= 0 ,0
Exp/Cntr=0.3,0.1

Type RM Length L Ch R = 1 ,6045    ,374,376.5,372.9
XS GIS Cut Line= 2
     2095095.747      199814.117     2095569.705      200292.137
#Sta/Elev= 30
       0 1832.43    17.8 1823.59    25.9 1820.73    63.6 1810.54      83 1807.38
     125 1804.35   187.6 1802.72   199.5 1801.45   227.5  1802.3   264.8 1800.99
   302.6 1797.93   334.7 1793.51   362.6 1792.99   370.21791.651   385.9 1791.02
   393.9 1791.55   404.8 1794.27   483.5 1793.74   564.7 1797.88   571.1 1801.17
   583.3 1811.05   594.2  1812.3   597.2 1813.78   604.9 1820.73   618.1 1836.36
   629.7  1846.9   637.5 1855.44     645 1862.13   657.5 1869.66   673.2 1875.85
#Mann= 7 ,-1 , 0
       0      .1       0     100    .035       0   370.2    .045       0
   393.9     .06       0     410    .035       0     520     .04       0
     660      .1       0
#XS Ineff= 2 , 0
                          531.07         1799.61
Permanent Ineff=
       F       F
Bank Sta=370.2,393.9
XS Rating Curve= 0 ,0
Exp/Cntr=0.3,0.1

Type RM Length L Ch R = 1 ,5669    ,476.9,462.3,446.3
XS GIS Cut Line= 3
 2094871.3963521200123.648494699      2095252.76      200470.176
     2095399.223      200459.715
#Sta/Elev= 30
       0  1842.8    58.5 1813.52    70.8 1809.29    89.1 1801.86   113.5 1795.64
   123.3 1794.27   138.3 1793.23   195.9 1791.56   253.6 1792.31   319.3 1792.37
   323.3 1791.99   328.9  1789.2   351.1 1788.79   353.11788.847   365.7 1791.72
   372.7 1795.37   376.9 1796.32   488.5 1804.72   506.2 1807.85     525 1808.34
   531.6 1807.82   534.9 1808.77   541.5 1811.82   564.5  1817.8   570.6 1818.77
   587.5 1819.46     627 1819.48   630.3 1820.39   646.7 1827.27   662.1 1831.29
#Mann= 7 ,-1 , 0
       0      .1       0     130    .035       0   328.9    .045       0
   353.1    .035       0     400     .06       0  525.29     .04       0
  625.29      .1       0
Bank Sta=328.9,353.1
XS Rating Curve= 0 ,0
Exp/Cntr=0.3,0.1

Type RM Length L Ch R = 1 ,5206    ,227.1,228.7,231
XS GIS Cut Line= 2
      2094748.35      200679.372     2095369.628      200609.663
#Sta/Elev= 30
       0  1844.1     8.9 1843.57    15.5 1841.63    22.1 1840.44    48.6 1836.64
    67.8 1832.44      75 1830.12    84.9 1825.42   111.3 1811.29   117.9 1807.13
   124.5 1802.28   131.1 1795.45   134.4  1791.4   137.7 1788.64   140.41787.535
   144.3 1787.16   166.91787.525   170.7 1787.86   177.3  1789.8   180.6 1790.09
   342.4 1794.76   365.5 1796.03   441.8  1798.3   487.6 1801.32   497.5 1803.93
   500.8 1804.29   542.7 1804.82   572.4 1806.18   603.2 1810.28   625.2 1812.38
#Mann= 7 ,-1 , 0
       0      .1       0   140.4    .045       0   166.9      .1       0
     220    .035       0     420     .04       0     520     .06       0
     620      .1       0
#XS Ineff= 2 , 0
                          292.37         1797.47
Permanent Ineff=
       F       F
Bank Sta=140.4,166.9
XS Rating Curve= 0 ,0
Exp/Cntr=0.3,0.1

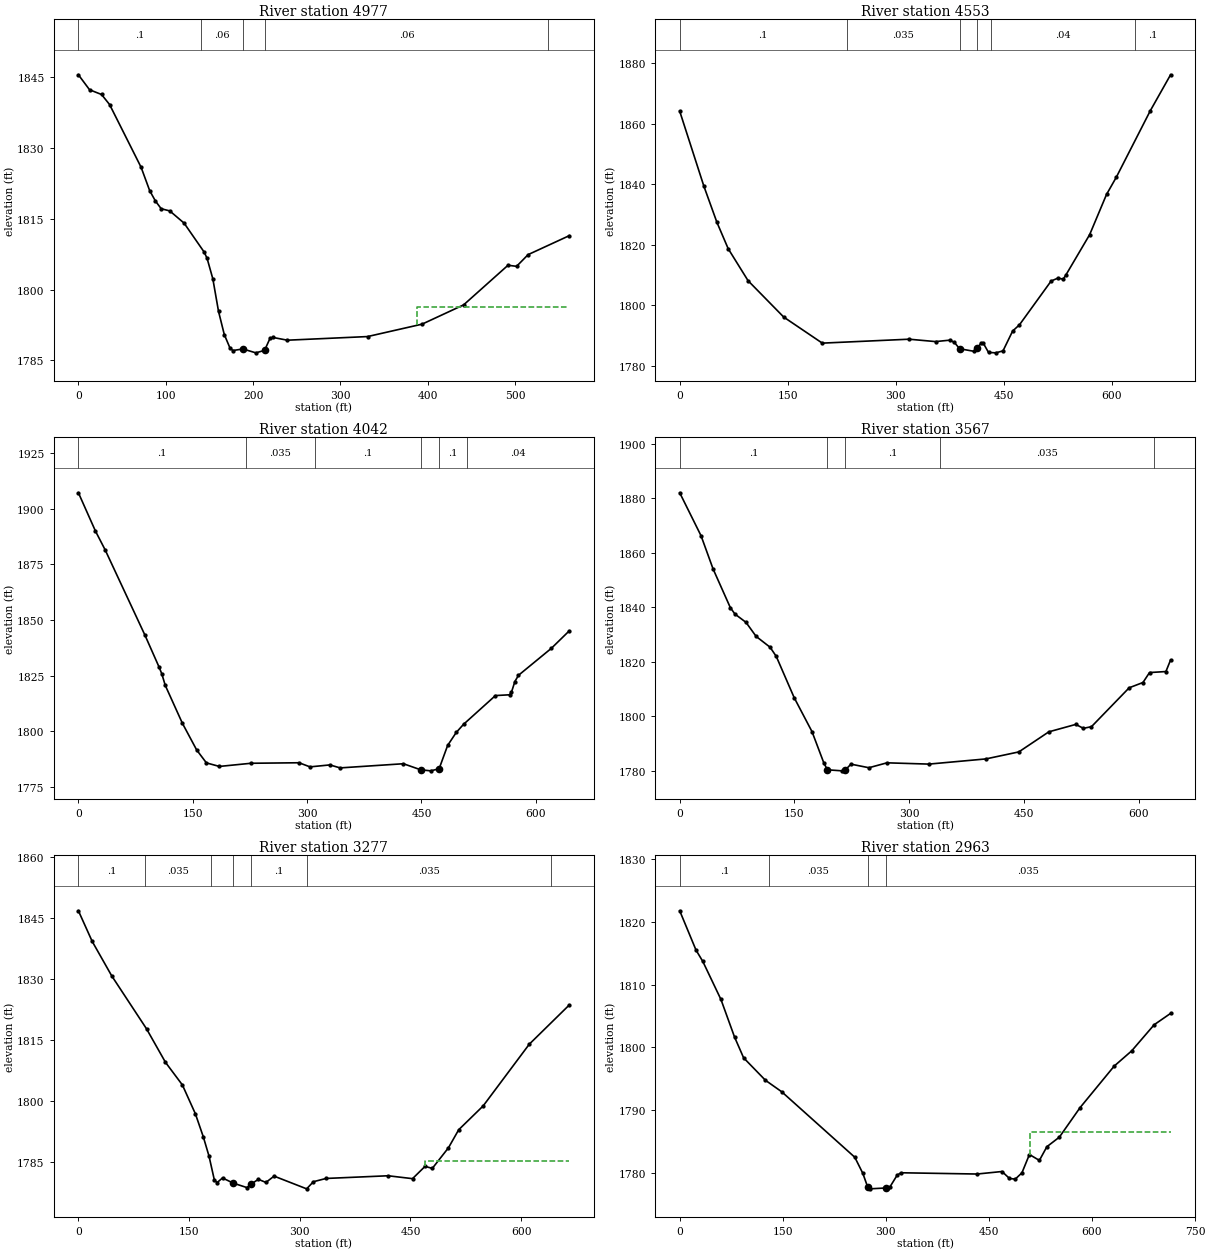
Type RM Length L Ch R = 1 ,4977    ,422.8,424.5,428.2
XS GIS Cut Line= 3
2094731.33457711200889.838885558     2094929.404      200887.905
     2095293.212      200891.893
#Sta/Elev= 30
       0 1845.57    12.8 1842.39    26.5 1841.39    35.7 1839.26    71.8 1825.95
    81.6 1821.01    88.2  1818.8    94.8 1817.17   104.6 1816.71     121 1814.12
     144 1807.97   147.3 1806.66   153.9 1802.31   160.4 1795.42     167  1790.5
   173.5 1787.65   176.8 1787.11   188.3 1787.44   203.1 1786.62   213.1 1787.14
   219.5 1789.75   222.8 1789.88   239.2  1789.3     331 1790.07   393.4  1792.7
     441 1796.79   491.8 1805.19   501.6 1804.96   514.8 1807.44   561.9 1811.46
#Mann= 5 ,-1 , 0
       0      .1       0     140     .06       0   188.3    .045       0
   213.1     .06       0  538.08      .1       0
#XS Ineff= 2 , 0
                          387.17         1796.34
Permanent Ineff=
       F       F
Bank Sta=188.3,213.1
XS Rating Curve= 0 ,0
Exp/Cntr=0.3,0.1

Type RM Length L Ch R = 1 ,4553    ,499.5,511.2,519.1
XS GIS Cut Line= 3
     2094651.299      201172.5522094770.84503382201227.440686124
2095310.30819859201333.400265609
#Sta/Elev= 30
       0 1864.18    33.5 1839.42    51.6 1827.46    67.3 1818.71    94.9 1808.13
   144.4  1796.1   197.9 1787.49   318.3 1788.79   355.1    1788   375.1 1788.48
   381.3 1787.71   388.5 1785.63   408.6 1784.78   412.9 1785.84   418.6 1787.57
   421.3  1787.5   428.6 1784.42   438.6 1784.28   448.7 1784.92   462.1 1791.49
   471.6 1793.56   515.5 1808.02   524.7 1808.97   532.3 1808.67   535.6 1809.86
     569 1823.37   592.4 1836.65     606 1842.36   653.2 1864.36   681.3 1876.23
#Mann= 6 ,-1 , 0
       0      .1       0  231.54    .035       0   388.5    .045       0
   412.9    .035       0  431.54     .04       0  631.54      .1       0
Bank Sta=388.5,412.9
XS Rating Curve= 0 ,0
Exp/Cntr=0.3,0.1

Type RM Length L Ch R = 1 ,4042    ,467.3,474.7,473.6
XS GIS Cut Line= 2
     2094519.913      201357.026     2094960.289      201826.645
#Sta/Elev= 30
       0 1907.21    22.4 1889.99    35.2 1881.49    87.4 1843.17     106 1828.78
   109.4 1825.88   113.9 1820.73   136.4 1803.68   155.1 1791.71   167.9 1785.89
   184.9  1784.3   226.4 1785.72   289.4 1785.95   303.8  1784.1   329.8 1784.98
   343.3 1783.64   426.3 1785.51     4491782.783     462 1782.32   473.11783.238
   484.3 1793.74   495.6 1799.57   505.2 1803.23     547 1816.13   565.6 1816.48
   567.9 1817.54   572.5 1822.44   577.2 1825.23   620.3 1837.34   643.8 1845.19
#Mann= 6 ,-1 , 0
       0      .1       0     220    .035       0     310      .1       0
     449    .045       0   473.1      .1       0     510     .04       0
Bank Sta=449,473.1
XS Rating Curve= 0 ,0
Exp/Cntr=0.3,0.1

Type RM Length L Ch R = 1 ,3567    ,287.2,289.8,290.5
XS GIS Cut Line= 2
     2094333.835      201492.233     2094685.114      202029.383
#Sta/Elev= 30
       0 1882.03    27.9 1866.27    43.6 1854.12    66.2 1839.91    72.2 1837.56
    86.7 1834.51    99.9 1829.37   118.1 1825.41   126.2 1822.06   149.7 1806.88
     173 1794.43   188.6 1782.85   193.21780.447   212.2 1780.07   216.1 1780.27
   223.9 1782.52   247.4 1781.21     271 1783.01   325.8 1782.54   400.3 1784.44
   443.4 1787.01   482.6 1794.37   517.9  1797.1   527.8 1795.65   538.4 1796.27
   587.7 1810.53   605.7 1812.46   614.3 1816.11   635.7 1816.48   641.8  1820.7
#Mann= 5 ,-1 , 0
       0      .1       0   193.2    .045       0   216.1      .1       0
     340    .035       0     620     .04       0
Bank Sta=193.2,216.1
XS Rating Curve= 0 ,0
Exp/Cntr=0.3,0.1

Type RM Length L Ch R = 1 ,3277    ,310.4,314.2,310.8
XS GIS Cut Line= 2
     2094099.641      201603.934     2094400.685      202197.062
#Sta/Elev= 30
       0 1846.76    18.7 1839.24    45.2 1830.77    92.3 1817.79     118 1809.56
   140.9 1804.01   158.5 1796.94   169.2 1791.31     177 1786.54   184.2 1780.71
   187.9 1780.02   195.3 1781.17     210 1779.89   228.2 1778.82   234.31779.692
   243.9 1780.84   254.1 1780.07   265.2 1781.62   309.3  1778.5   318.5 1780.25
   335.6 1781.05   419.7 1781.71   452.8    1781   469.8 1784.02   479.6 1783.52
   501.5 1788.58   515.4 1793.01   548.5 1798.85     611    1814   665.2 1823.63
#Mann= 7 ,-1 , 0
       0      .1       0      90    .035       0     180      .1       0
     210    .045       0   234.3      .1       0     310    .035       0
     640     .04       0
#XS Ineff= 2 , 0
                          470.28         1785.41
Permanent Ineff=
       F       F
Bank Sta=210,234.3
XS Rating Curve= 0 ,0
Exp/Cntr=0.3,0.1

Type RM Length L Ch R = 1 ,2963    ,972.1,989.9,975.3
XS GIS Cut Line= 3
     2093939.764      201656.112     2093915.521      201872.954
     2094127.897      202321.303
#Sta/Elev= 30
       0 1821.75    23.7 1815.49    33.6 1813.68      60 1807.62    79.8 1801.63
      93 1798.32   124.7 1794.75   148.5 1792.91   254.8 1782.48   266.5 1779.91
   273.71777.684   276.4 1777.45   299.81777.584     306 1777.77   316.5 1779.64
   322.1 1780.01   432.7 1779.81     469 1780.21   479.9  1779.1   488.3    1779
     498    1780   508.9 1782.92   523.4 1781.98   534.3 1784.16   552.5 1785.69
   582.6 1790.39   632.3 1797.01   657.7 1799.43   690.4 1803.59   714.3  1805.4
#Mann= 4 ,-1 , 0
       0      .1       0     130    .035       0   273.7    .045       0
   299.8    .035       0
#XS Ineff= 2 , 0
                          509.61         1786.44
Permanent Ineff=
       F       F
Bank Sta=273.7,299.8
XS Rating Curve= 0 ,0
Exp/Cntr=0.3,0.1

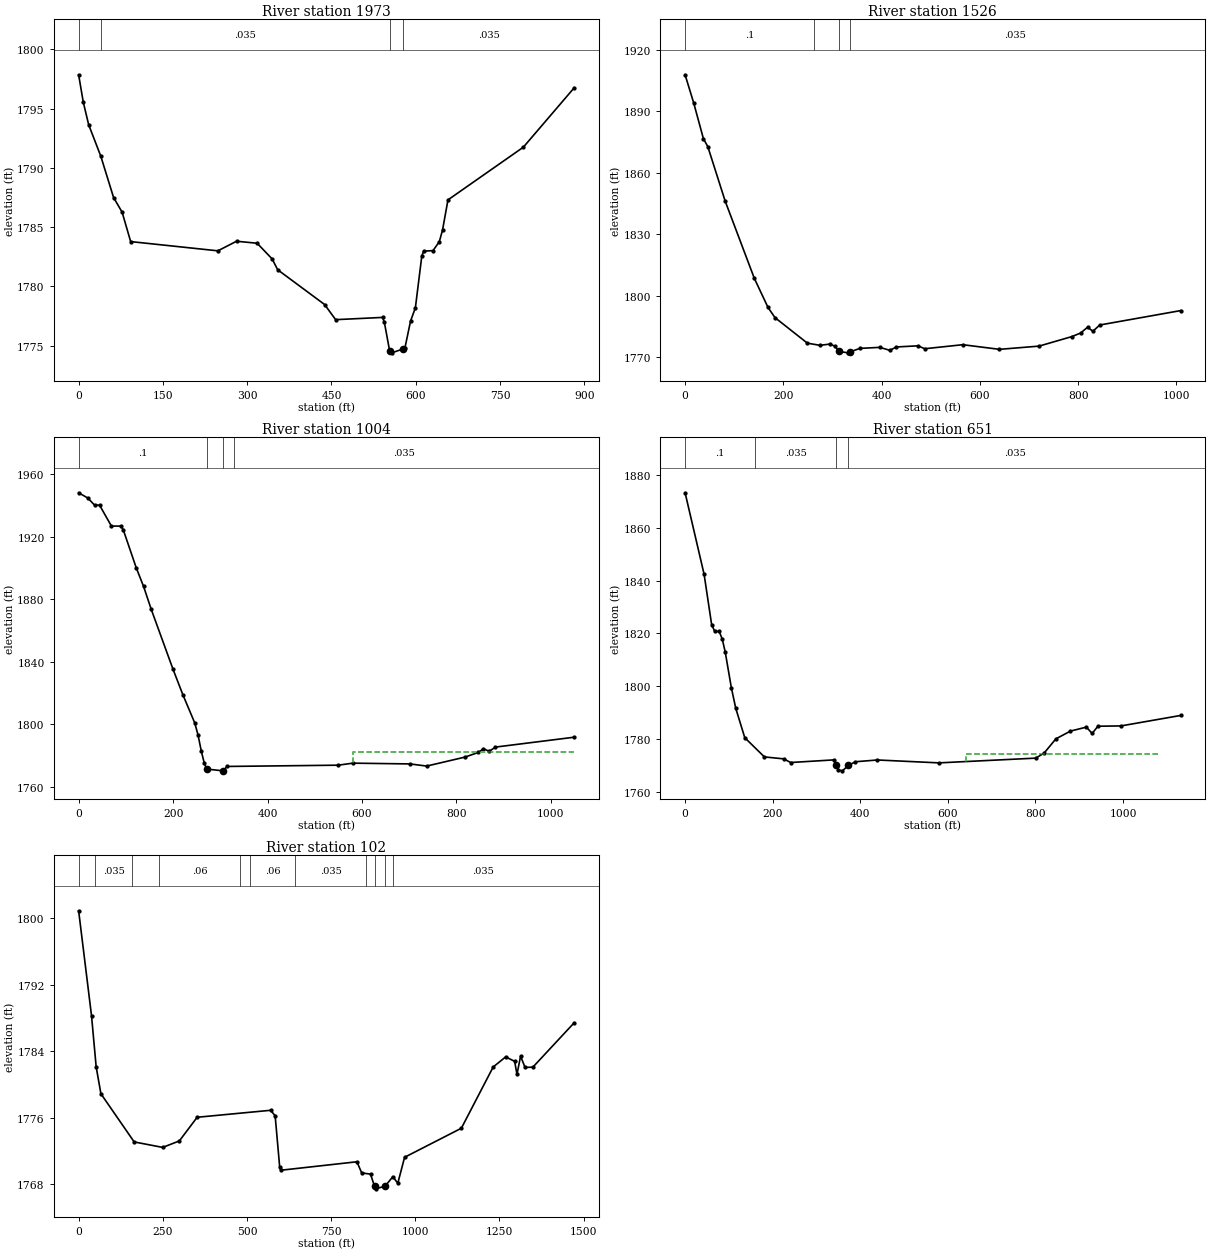
Type RM Length L Ch R = 1 ,1973    ,447.1,447.4,445.2
XS GIS Cut Line= 4
     2093358.358      201781.041        2093590.      201916.357
     2093659.444      202317.832     2093776.076      202487.862
#Sta/Elev= 30
       0 1797.86     8.3 1795.54    17.9 1793.64    39.5 1790.98    62.2  1787.5
    77.4 1786.26    92.6 1783.78   247.8    1783   281.1 1783.81   317.7 1783.64
   344.3 1782.32   354.3  1781.4   437.7 1778.47   457.4 1777.19   540.8 1777.38
   544.1 1776.97   553.51774.555   557.4 1774.39   578.1 1774.73   580.7  1774.8
   590.7 1777.07   599.3 1778.19   610.7 1782.55     614 1782.97   630.7 1783.02
   641.9 1783.77   647.6 1784.75   657.3  1787.3   791.5 1791.75   881.9 1796.76
#Mann= 4 ,-1 , 0
       0      .1       0      40    .035       0   553.5    .045       0
   578.1    .035       0
Bank Sta=553.5,578.1
XS Rating Curve= 0 ,0
Exp/Cntr=0.3,0.1

Type RM Length L Ch R = 1 ,1526    ,539.3,521.8,500.8
XS GIS Cut Line= 4
     2093020.495      201908.494     2093195.035      202029.204
     2093307.882      202478.423     2093617.663      202601.762
#Sta/Elev= 30
       0 1907.83    17.4 1894.17    37.3  1876.6    46.2 1872.77    81.6 1846.12
     141 1808.38   168.8 1794.21     183 1789.23     249 1776.76   274.6 1775.71
     295 1776.32   305.1 1775.25   313.3 1772.71   332.1 1772.04   336.21772.536
   355.8 1774.21   396.4 1774.72   416.8 1773.26   430.1 1774.91   474.2 1775.47
   487.7 1774.04   565.3 1776.01     640 1773.75   720.5 1775.32   787.3 1779.97
   805.2 1781.71   819.3 1784.55   830.2 1782.58   844.1 1785.63  1008.8 1792.67
#Mann= 4 ,-1 , 0
       0      .1       0  262.21    .035       0   313.3    .045       0
   336.2    .035       0
Bank Sta=313.3,336.2
XS Rating Curve= 0 ,0
Exp/Cntr=0.3,0.1

Type RM Length L Ch R = 1 ,1004    ,352.9,352.3,346.2
XS GIS Cut Line= 2
      2092596.73      202253.863     2093570.799      202643.853
#Sta/Elev= 30
       0 1948.15    19.5 1944.78    33.6  1940.3    44.3 1940.23    69.4 1926.85
    89.6 1926.82    94.6 1924.38     122  1900.1   137.5  1888.2   153.8 1873.48
   199.7 1835.31   220.8 1818.81   245.7 1800.96   252.8 1793.16   259.8 1782.69
   266.2 1774.93   271.3 1771.31   305.8 1770.18   306.51770.373   314.2 1772.99
   549.6  1773.8   580.8  1775.1   701.6  1774.6   736.9 1773.23   818.2 1778.99
   846.5 1781.98   857.1 1784.34   869.4 1782.69   882.5 1785.38  1049.2  1791.7
#Mann= 4 ,-1 , 0
       0      .1       0   271.3    .045       0   306.5      .1       0
     330    .035       0
#XS Ineff= 2 , 0
                          581.33         1782.04
Permanent Ineff=
       F       F
Bank Sta=271.3,306.5
XS Rating Curve= 0 ,0
Exp/Cntr=0.3,0.1

Type RM Length L Ch R = 1 ,651     ,543.1,549.2,495.6
XS GIS Cut Line= 4
2092530.31929788 202412.577722932092606.22005152202651.109516908
     2093236.267      202769.221      2093475.95      202753.522
#Sta/Elev= 30
       0 1873.38    43.4 1842.46    60.6 1823.38    67.5 1820.84    77.8 1820.77
    84.7 1817.98    91.6    1813   105.6 1799.44   115.7  1791.6   136.3 1780.46
   181.1 1773.18   224.7 1772.45   241.2 1771.06   339.2 1772.05   345.21770.142
   349.2 1768.26   359.2  1767.9   373.11769.984   388.9 1771.35   439.3 1772.02
   579.5 1770.92   800.4 1772.72   819.6  1774.6   846.6 1780.03     880 1782.98
   916.3 1784.49   929.4 1782.08   942.6 1784.82   995.3 1784.94  1131.5 1788.91
#Mann= 4 ,-1 , 0
       0      .1       0     160    .035       0   345.2    .045       0
   373.1    .035       0
#XS Ineff= 2 ,-1
       0  167.18 1774.33  641.49  1079.5 1774.33
Permanent Ineff=
       F       F
Bank Sta=345.2,373.1
XS Rating Curve= 0 ,0
Exp/Cntr=0.3,0.1

Type RM Length L Ch R = 1 ,102     ,,,
XS GIS Cut Line= 3
2092318.31518942 202517.043293482092526.03646079203040.694210755
     2093409.947      202829.838
#Sta/Elev= 30
       0  1800.9    38.3 1788.26    52.1  1782.1    66.2 1778.86     165 1773.06
   249.7  1772.4   299.2 1773.18   352.1 1776.03   570.3 1776.87   583.8 1776.21
   597.3 1770.02   600.7 1769.65   826.7 1770.67   840.9 1769.33   867.1 1769.18
     879 1767.72     884 1767.41     911 1767.76   933.5 1768.88   948.1 1768.07
   968.3 1771.21    1137 1774.71  1231.4 1782.08  1268.5  1783.3  1295.2 1782.77
  1302.2  1781.2  1312.9 1783.39  1326.2 1782.03  1349.5 1782.07  1472.1 1787.41
#Mann= 11 ,-1 , 0
       0      .1       0      50    .035       0     160     .04       0
     240     .06       0     480     .04       0     510     .06       0
  643.35    .035       0  853.35     .06       0     879    .045       0
     911     .06       0  933.35    .035       0
#XS Ineff= 2 , 0
           85.66 1777.67
Permanent Ineff=
       F       F
Bank Sta=879,911
XS Rating Curve= 0 ,0
Exp/Cntr=0.3,0.1
LCMann Table=0

Chan Stop Cuts=-1
Use User Specified Reach Order=0
Composite Channel Slope=5